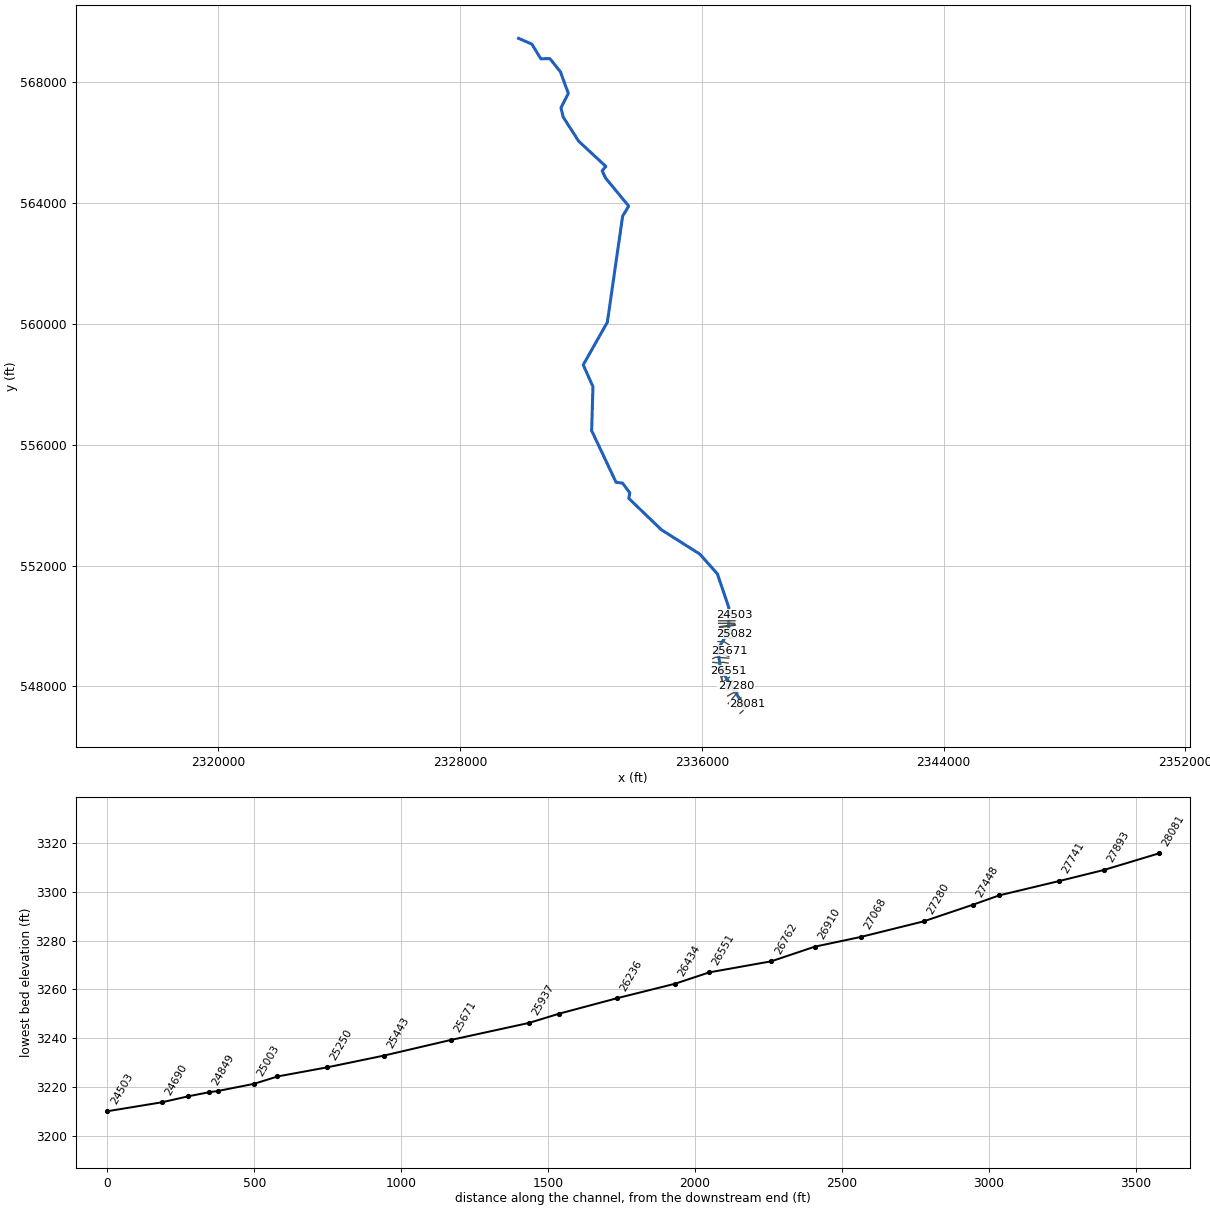
--- LTTLRV2.prj (project) ---

Proj Title=LTTLRV2
Current Plan=p01
Default Exp/Contr=0,0
English Units
Geom File=g01
Flow File=f01
Plan File=p01
Background Map Layer=Inundation Boundary (01pct Value_0)
Background Map Layer=Inundation Boundary (01pct Value_0)
BEGIN DESCRIPTION:
----------MODEL BY WOOD PLC 2021----------
Stream Name: Little River 2
Flood Zone: Enhanced Approximate
Pocahontas County, WV
HEC-RAS Version: RAS 6.1
Vertical Datum: NAVD88
Projection: NAD 1983 StatePlane West Virginia S FIPS 4702 (US Feet)
Terrain: 1-meter LIDAR (FEMA Region III 3DEP collected 2016-2018)
Land Use: 2019 NLCD
Hydrologic Method:
WV SIR2010-5033 regression equations
Model Notes:
Normal depth tie in, Ties in with
END DESCRIPTION:
DSS Export Rating Curves= 0
DSS Export Rating Curve Sorted= 0
DSS Export Volume Flow Curves= 0
DXF OffsetX= 0
DXF OffsetY= 0
DXF ScaleX= 0
DXF ScaleY= 0

--- LTTLRV2.p01 (plan) ---

Plan Title=Floodplain
Program Version=6.10
Short Identifier=Floodplain
Geom File=g01
Flow File=f01
Subcritical Flow
K Sum by GR= 0
Std Step Tol= 0.01
Critical Tol= 0.01
Num of Std Step Trials= 20
Max Error Tol= 0.3
Flow Tol Ratio= 0.001
Split Flow NTrial= 30
Split Flow Tol= 0.02
Split Flow Ratio= 0.02
Log Output Level= 0
Friction Slope Method= 1
Unsteady Friction Slope Method= 2
Unsteady Bridges Friction Slope Method= 1
Parabolic Critical Depth
Global Vel Dist= 0 , 0 , 0
Global Log Level= 0
CheckData=True
Encroach Param=-1 ,0,0, 0
Mapping Interval=1HOUR
Computation Time Step Use Courant=        0
Computation Time Step Use Time Series=    0
Computation Time Step Count To Double=0
Computation Time Step Max Doubling=0
Computation Time Step Max Halving=0
Computation Time Step Residence Courant=0
Run HTab= 0
Run UNet= 0
Run Sediment= 0
Run PostProcess= 0
Run WQNet= 0
Run RASMapper=-1
UNET Theta= 0
UNET Theta Warmup= 0
UNET ZTol= 0
UNET ZSATol= 0
UNET MxIter= 0
UNET Max Iter WO Improvement= 0
UNET MaxInSteps= 0
UNET DtIC= 0
UNET DtMin= 0
UNET MaxCRTS= 0
UNET WFStab= 0
UNET SFStab= 0
UNET WFX= 1
UNET SFX= 1
UNET Gravity=32.174
UNET 1D Methodology=Finite Difference
UNET DSS MLevel= 1
UNET Pardiso=0
UNET DZMax Abort= 0
UNET Use Existing IB Tables= 0
UNET Froude Reduction=False
UNET Froude Limit= 0
UNET Froude Power= 0
UNET D1 Cores= 0
UNET WindReference=Eulerian
UNET WindDragFormulation=Hsu (1988)
UNET D2 Coriolis=0
UNET D2 Cores= 0
UNET D2 Theta= 1
UNET D2 Theta Warmup= 1
UNET D2 Z Tol= 0.01
UNET D2 Volume Tol= 0.01
UNET D2 Max Iterations= 20
UNET D2 Equation= 0
UNET D2 RampUpFraction=0.1
UNET D2 TimeSlices= 1
UNET D2 Turbulence Formulation=Non-Conservative (original)
UNET D2 Eddy Viscosity=0.3
UNET D2 Transverse Eddy Viscosity=0.1
UNET D2 Smagorinsky Mixing=0
UNET D2 BCVolumeCheck=0
UNET D2 Cores=0
UNET D2 SolverType=PARDISO (Direct)
UNET D2 Minimum Iterations= 2147483647
UNET D2 Maximum Iterations= 2147483647
UNET D2 Restart Number= 10
UNET D2 Relaxation Coeff=1.3
UNET D2 SOR Precondition Iterations= 10
UNET D2 ILUT Maximum Fill= 8
UNET D2 ILUT Tolerance=1E-08
UNET D1D2 MaxIter= 0
UNET D1D2 ZTol=0.01
UNET D1D2 QTol=0.1
UNET D1D2 MinQTol=1
Write IC File= 0
Write IC File at Fixed DateTime=0
Write IC File at Sim End=0
Echo Input=False
Echo Parameters=False
Echo Output=False
Write Detailed= 0
HDF Write Warmup=0
HDF Write Time Slices=0
HDF Flush=0
HDF Compression= 1
HDF Chunk Size= 1
HDF Spatial Parts= 1
HDF Use Max Rows=0
HDF Fixed Rows= 1
Calibration Method= 0
Calibration Iterations= 20
Calibration Max Change=0.05
Calibration Tolerance=0.2
Calibration Maximum=1.5
Calibration Minimum=0.5
Calibration Optimization Method= 1
WQ AD Non Conservative
WQ ULTIMATE=-1
WQ Max Comp Step=1HOUR
WQ Output Interval=15MIN
WQ Output Selected Increments= 0
WQ Output face flow=0
WQ Output face velocity=0
WQ Output face area=0
WQ Output face dispersion=0
WQ Output cell volume=0
WQ Output cell surface area=0
WQ Output cell continuity=0
WQ Output cumulative cell continuity=0
WQ Output face conc=0
WQ Output face dconc_dx=0
WQ Output face courant=0
WQ Output face peclet=0
WQ Output face adv mass=0
WQ Output face disp mass=0
WQ Output cell mass=0
WQ Output cell source sink temp=0
WQ Output nsm pathways=0
WQ Output nsm derived pathways=0
WQ Create Restart=0
WQ Fixed Restart=0
WQ System Summary=0
WQ Write To DSS=0
Sorting and Armoring Iterations= 10
XS Update Threshold= 0.02
Bed Roughness Predictor= 0
Hydraulics Update Threshold= 0.02
Energy Slope Method= 1
Volume Change Method= 1
Sediment Retention Method= 0
Sediment TS Multiplier= 1
Warm Up Method= 0
XS Weighting Method= 0
Number of US Weighted Cross Sections= 1
Number of DS Weighted Cross Sections= 1
Upstream XS Weight=0
Main XS Weight=1
Downstream XS Weight=0
Number of DS XS's Weighted with US Boundary= 1
Upstream Boundary Weight= 1
Weight of XSs Associated with US Boundary= 0
Number of US XS's Weighted with DS Boundary= 1
Downstream Boundary Weight= 0.5
Weight of XSs Associated with DS Boundary= 0.5
Percentile Method= 0
Sediment Output Level= 3
Mass or Volume Output= 0
Output Increment Type= 1
Profile and TS Output Increment= 1
Transport Output Increment 1
XS Output Flag= 0
XS Output Increment= 10
Read HDF5 Sediment Hotstart= 0
Sediment Hotstart Type= 0
Write Gradation File= 0
Read Gradation Hotstart= 0
Write HDF5 File= 1
Write Binary Output= 1
Write DSS Sediment File= 0
DSS Sediment Output Type= 1
SV Curve= 0
Specific Gage Flag= 0
Subcell Erosion Methods= 0
Subcell Deposition Methods= 0
Advection Scheme= 1
Matrix Solver= 0
Implicit Weighting Factor= 1
Maximum Outer Loop Convergence Iterations= 5
Convergence Maximum Absolute= 0.001
Convergence RMSE= 0.0001
Grain Fractions Max Abs Error= 0.001
Max Subgrid Regions= 1
Max Subgrid Length Scale= 3.402823E+38
Initial Layer Thickness= 3.402823E+38
Min Layer Thickness= 3.402823E+38
Max Layer Thickness= 3.402823E+38
Number of Layers= 5

--- LTTLRV2.f01 (steady flow) ---

Flow Title=Flow
Program Version=6.10
Number of Profiles= 6
Profile Names=01pct,10pct,04pct,02pct,0_2pct,01plus
River Rch & RM=LTTLRV2,Main            ,28081
     538     283     377     455     752     795
River Rch & RM=LTTLRV2,Main            ,26434
     815     437     577     692    1130    1210
River Rch & RM=LTTLRV2,Main            ,23613
    1080     585     769     920    1490    1600
River Rch & RM=LTTLRV2,Main            ,20734
    1290     703     921    1100    1770    1910
River Rch & RM=LTTLRV2,Main            ,16815
    1520     833    1090    1300    2080    2250
River Rch & RM=LTTLRV2,Main            ,16127
    1730     953    1240    1480    2360    2560
River Rch & RM=LTTLRV2,Main            ,7750
    2840    1600    2060    2440    3850    4200
Boundary for River Rch & Prof#=LTTLRV2,Main            , 1
Up Type= 0
Dn Type= 3
Dn Slope=0.01056
Boundary for River Rch & Prof#=LTTLRV2,Main            , 2
Up Type= 0
Dn Type= 3
Dn Slope=0.01056
Boundary for River Rch & Prof#=LTTLRV2,Main            , 3
Up Type= 0
Dn Type= 3
Dn Slope=0.01056
Boundary for River Rch & Prof#=LTTLRV2,Main            , 4
Up Type= 0
Dn Type= 3
Dn Slope=0.01056
Boundary for River Rch & Prof#=LTTLRV2,Main            , 5
Up Type= 0
Dn Type= 3
Dn Slope=0.01056
Boundary for River Rch & Prof#=LTTLRV2,Main            , 6
Up Type= 0
Dn Type= 3
Dn Slope=0.01056
DSS Import GetInterval= 0
DSS Import GetPeak= 0
DSS Import FillOption= 0

--- LTTLRV2.g01 (geometry) ---

Geom Title=Geometry
Program Version=6.10

River Reach=LTTLRV2         ,Main
Reach XY= 30
 2337429.1247833547307.1422809342336616.70078429548581.735416327
     2336530.018      549228.445     2336889.326      549829.766
     2336892.869      550611.462     2336513.703      551724.875
     2335934.054      552377.487 2334658.1970254 553185.55237622
     2333584.037      554221.4132333616.58839858554402.009647029
2333378.51752071 554726.251957812333162.48519044554752.878192795
     2332353.823      556461.7372332396.98448321557921.096750581
     2332074.549      558639.305 2332873.1406413560051.176139042
2333378.46950573563560.075273823     2333579.214      563894.604
 2332819.6103809564817.398593418   2332699.85109565058.984566382
     2332822.286      565208.075     2331923.801      566042.786
2331412.71175717566838.257884021     2331336.699      567145.394
2331581.92483358 567623.785164162331321.53338202 568335.31236345
     2330971.777      568775.749     2330672.271      568767.528
     2330376.302       569252.58     2329936.326      569445.437

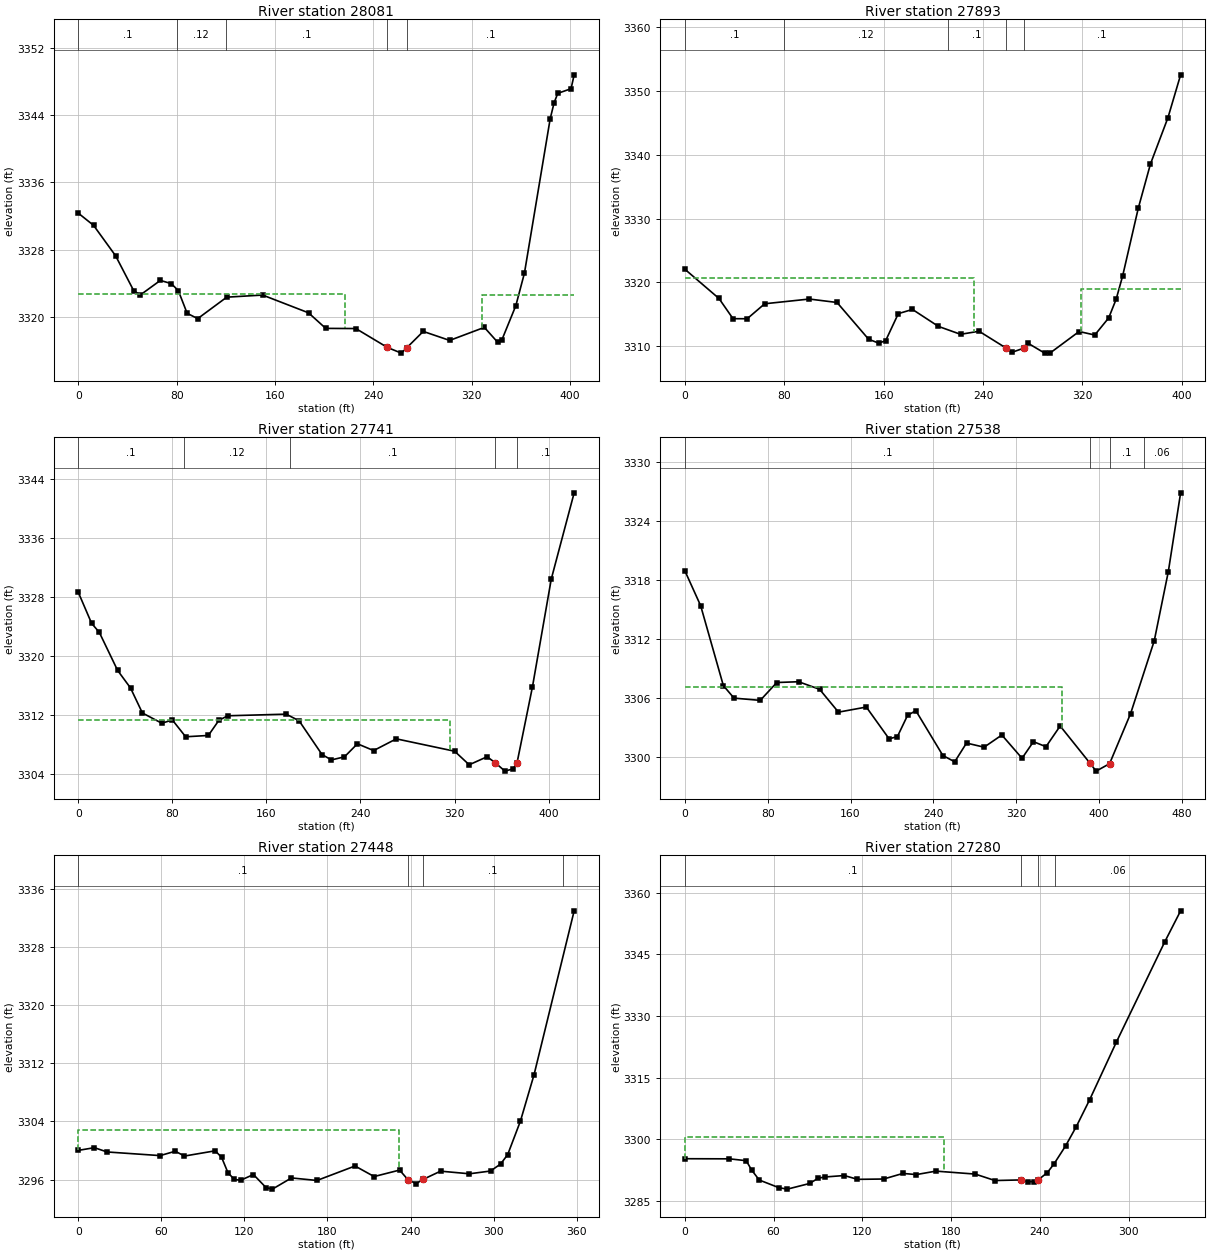
Type RM Length L Ch R = 1 ,28081   ,187.6,187.6,187.6
XS GIS Cut Line= 4
2337263.02151744547107.5073037622337364.73000745547200.921968411
2337431.08061038547338.4248626382337514.01886404547414.378842307
#Sta/Elev= 30
       0 3332.35    12.4  3330.9    30.3 3327.29      45 3323.15    50.4 3322.63
    66.7 3324.36    75.6 3323.98    81.3 3323.15    88.5 3320.45    97.1 3319.82
   120.7 3322.37   149.9 3322.62   187.2 3320.51   201.2 3318.66   225.7 3318.64
   251.4 3316.39   262.7 3315.72   267.2 3316.37   280.5  3318.3     302 3317.23
   330.2 3318.78   341.1    3317   344.5 3317.31   355.8 3321.36   362.8 3325.23
   383.7 3343.54   386.9 3345.46   389.9 3346.59   400.7 3347.14403.2341 3348.79
#Mann= 5 ,-1,0
       0      .1       0      80     .12       0     120      .1       0
   251.4    .045       0   267.2      .1       0
#XS Ineff= 2 , 0
          217.18 3322.74  328.17         3322.61
Permanent Ineff=
       F       F
Bank Sta=251.4,267.2
XS Rating Curve= 0 ,0
Exp/Cntr(USF)=0,0
Exp/Cntr=0.3,0.1

Type RM Length L Ch R = 1 ,27893   ,146.2,151.9,158.2
XS GIS Cut Line= 3
2337105.00231836547273.3838110832337231.59228447547403.465914193
2337425.84240489547501.245750088
#Sta/Elev= 30
       0 3322.07    27.5 3317.48    38.8 3314.31    50.2  3314.3    64.3 3316.65
   100.2 3317.39   122.5 3316.85   147.9 3311.09     156 3310.48   161.6 3310.85
   171.8  3315.1   183.2 3315.76   204.1  3313.1   221.9 3311.86   236.8 3312.34
   258.3 3309.73   263.6 3309.06   272.6 3309.68   276.2 3310.46   289.6 3308.91
   294.1 3308.95   317.3  3312.3   329.9 3311.75   341.1 3314.43   347.1 3317.36
   352.3 3320.99   364.9 3331.62   374.7 3338.56   388.8 3345.83398.9832 3352.54
#Mann= 5 ,-1,0
       0      .1       0      80     .12       0  211.51      .1       0
   258.3    .045       0   272.6      .1       0
#XS Ineff= 2 , 0
          232.79 3320.73  318.87         3318.99
Permanent Ineff=
       F       F
Bank Sta=258.3,272.6
XS Rating Curve= 0 ,0
Exp/Cntr(USF)=0,0
Exp/Cntr=0.3,0.1

Type RM Length L Ch R = 1 ,27741   ,201,203.4,206
XS GIS Cut Line= 2
 2336991.9443831547332.313622895 2337297.9428874547622.597510707
#Sta/Elev= 30
       0 3328.63    11.3 3324.43    17.8 3323.22    33.4 3318.05    44.4 3315.66
    54.5 3312.27      71 3310.88      80 3311.32    91.3 3309.04   110.6 3309.22
   119.6 3311.28   127.1 3311.89   176.8 3312.11   187.8 3311.21   207.3 3306.63
   215.3  3305.9   226.4 3306.32   237.4 3308.09   251.2 3307.17   270.5 3308.76
   320.1 3307.08   332.5 3305.24   347.7 3306.33   354.5 3305.54   362.9 3304.38
   369.7 3304.68   373.2 3305.51   386.3 3315.81   402.3 3330.43421.7817 3342.14
#Mann= 5 ,-1,0
       0      .1       0      90     .12       0     180      .1       0
   354.5    .045       0   373.2      .1       0
#XS Ineff= 2 , 0
          315.77 3311.37
Permanent Ineff=
       F       F
Bank Sta=354.5,373.2
XS Rating Curve= 0 ,0
Exp/Cntr(USF)=0,0
Exp/Cntr=0.3,0.1

Type RM Length L Ch R = 1 ,27538   ,96.1,89.9,83.8
XS GIS Cut Line= 3
 2336874.5212766547428.3473902922337141.66975682547756.171750813
2337190.55967476 547782.79929541
#Sta/Elev= 30
       0 3318.96    15.3 3315.39    37.2 3307.25    47.5 3305.97    72.8 3305.74
    88.8 3307.56   109.8 3307.64   130.1 3306.87   148.3 3304.54   175.2 3305.06
   197.2 3301.82   205.2 3302.05     215 3304.21     223 3304.69   249.1 3300.12
   260.5 3299.48   271.9 3301.39   288.9 3300.97     306 3302.21   325.5 3299.84
   336.5 3301.53   348.6 3301.02   362.3 3303.13   391.3 3299.31     397 3298.53
     410 3299.29   430.3  3304.4   453.1 3311.81   466.7 3318.87478.5623 3326.89
#Mann= 4 ,-1,0
       0      .1       0   391.3    .045       0     410      .1       0
  442.89     .06       0
#XS Ineff= 2 , 0
          364.51 3307.14
Permanent Ineff=
       F       F
Bank Sta=391.3,410
XS Rating Curve= 0 ,0
Exp/Cntr(USF)=0,0
Exp/Cntr=0.3,0.1

Type RM Length L Ch R = 1 ,27448   ,169,167.7,167
XS GIS Cut Line= 2
 2336854.0403003547682.8015453462337166.00932894547858.845488572
#Sta/Elev= 30
       0 3300.01    11.6 3300.38    20.8 3299.79    59.1 3299.29      70 3299.89
    76.7 3299.23    98.9 3299.95   103.5 3299.05   108.1 3296.94   112.7 3296.01
   117.3  3295.9   126.5 3296.69   135.6 3294.89   140.2 3294.68     154 3296.22
   172.4 3295.87   199.9 3297.86   213.7 3296.41   232.1  3297.3   238.2 3295.96
   244.1 3295.44     249 3296.01   261.7 3297.15   282.6 3296.79   297.8 3297.17
   305.1 3298.14   310.2 3299.43   319.4 3304.04   329.2 3310.39358.2124 3332.95
#Mann= 4 ,-1,0
       0      .1       0   238.2    .045       0     249      .1       0
     350     .06       0
#XS Ineff= 2 , 0
          231.89 3302.75
Permanent Ineff=
       F       F
Bank Sta=238.2,249
XS Rating Curve= 0 ,0
Exp/Cntr(USF)=0,0
Exp/Cntr=0.3,0.1

Type RM Length L Ch R = 1 ,27280   ,209.6,212.5,212.6
XS GIS Cut Line= 2
2336830.68753232547862.4382221072337133.67472712548005.548774594
#Sta/Elev= 30
       0 3295.26    30.2 3295.23    41.5 3294.78    45.2 3292.49    50.3 3290.08
    63.6 3288.21    69.3 3287.86    84.3 3289.23    90.1 3290.51    94.5 3290.81
   107.8 3291.17   116.7 3290.24   134.4 3290.32   147.4 3291.68   156.5  3291.4
   169.7 3292.24   196.3 3291.52   209.6 3289.95   227.3  3290.1   231.7 3289.68
   236.1  3289.7  238.75  3290.1     245 3291.87   249.6 3294.04   257.3 3298.35
   264.6 3303.09   273.6 3309.61   291.6 3323.59   324.3 3347.99335.0849 3355.58
#Mann= 4 ,-1,0
       0      .1       0   227.3    .045       0  238.75      .1       0
     250     .06       0
#XS Ineff= 2 , 0
           174.9  3300.6
Permanent Ineff=
       F       F
Bank Sta=227.3,238.75
XS Rating Curve= 0 ,0
Exp/Cntr(USF)=0,0
Exp/Cntr=0.3,0.1

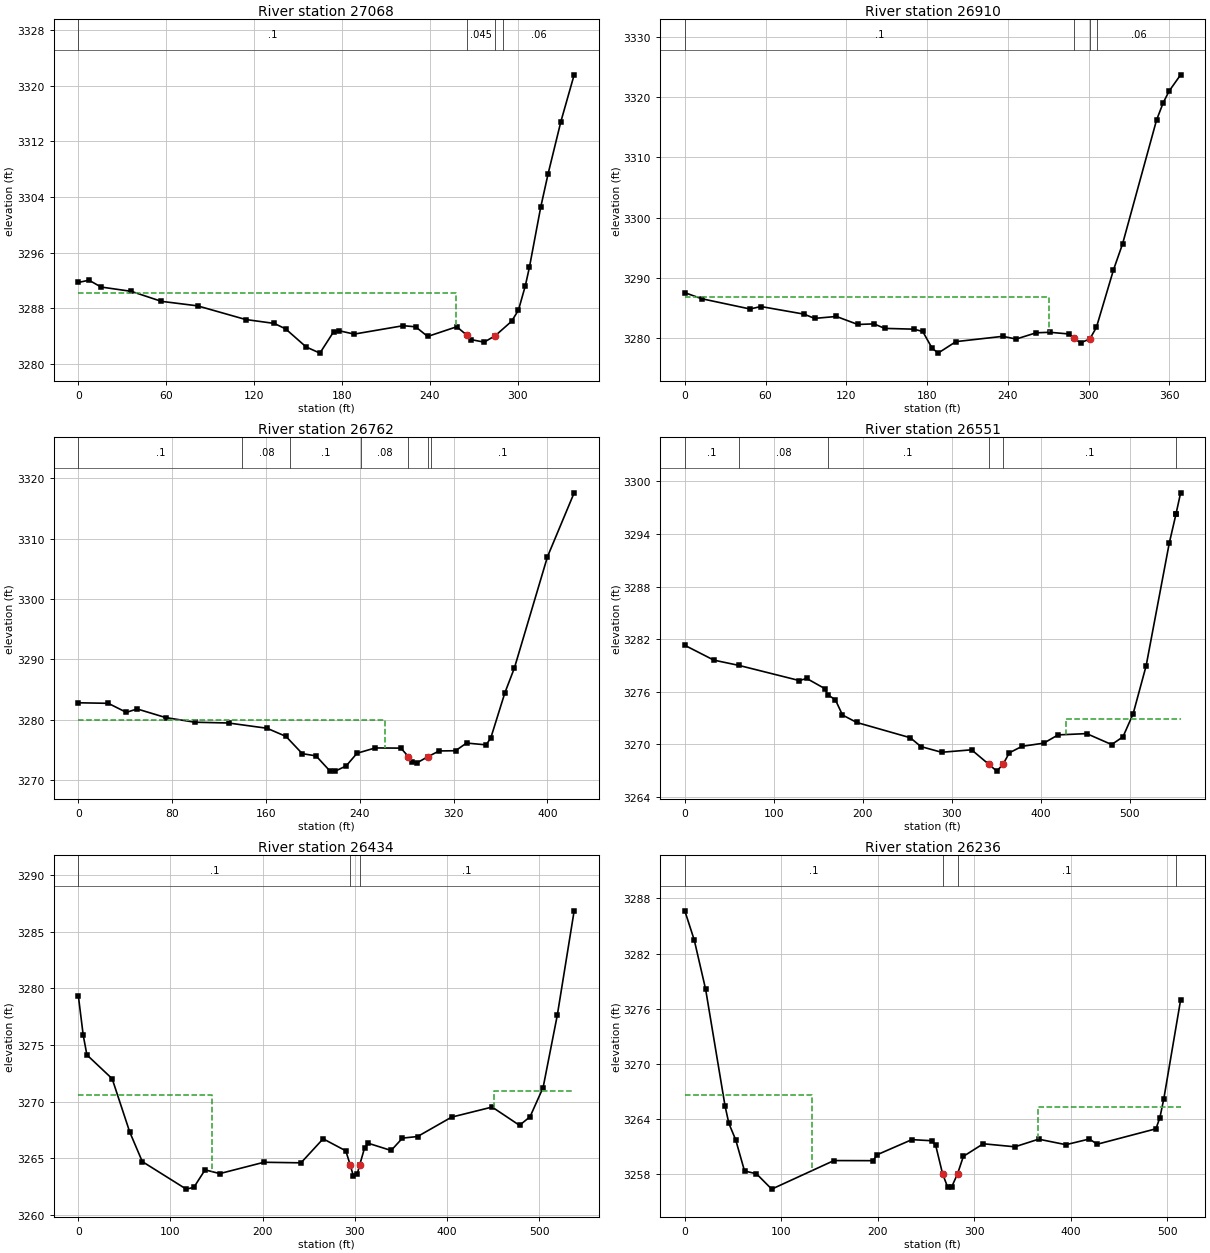
Type RM Length L Ch R = 1 ,27068   ,156.2,158,159.6
XS GIS Cut Line= 3
2336797.75414158547930.1013703542336830.68753232 548066.02645577
2337000.74358632548169.018150447
#Sta/Elev= 30
       0 3291.69     7.3 3292.01    15.5 3291.03    36.1 3290.41    56.7 3288.97
    81.4 3288.32   114.3 3286.35   133.8 3285.79   141.6    3285   155.6  3282.4
     165 3281.51   174.3 3284.56   178.2 3284.73   188.4 3284.25   221.9 3285.46
   230.4  3285.3   238.6 3283.91   258.5 3285.31   265.6 3284.05   268.5 3283.45
   277.2 3283.09   284.9 3284.04   295.9 3286.09   300.6 3287.69   305.3  3291.2
   308.1 3293.86   315.8  3302.5   320.9 3307.36   329.6 3314.86338.6703 3321.59
#Mann= 4 ,-1,0
       0      .1       0   265.6    .045       0   284.9      .1       0
  289.86     .06       0
#XS Ineff= 2 , 0
          258.11 3290.24
Permanent Ineff=
       F       F
Bank Sta=265.6,284.9
XS Rating Curve= 0 ,0
Exp/Cntr(USF)=0,0
Exp/Cntr=0.3,0.1

Type RM Length L Ch R = 1 ,26910   ,148.9,147.5,144.5
XS GIS Cut Line= 3
2336744.46192747548024.7100201152336743.86313855548180.993928897
2336914.51798147 548306.73960263
#Sta/Elev= 30
       0 3287.52    12.5 3286.52    48.5 3284.81    56.5 3285.22    88.5 3283.96
    96.4 3283.25   112.6 3283.57   128.5 3282.24   140.5 3282.34   148.5 3281.59
   170.1 3281.46   176.7 3281.08   183.6 3278.33   188.1 3277.48   201.4 3279.39
   236.2 3280.27   246.1 3279.82     261 3280.86   271.2 3280.94   285.4 3280.66
     289 3279.91     294  3279.2   300.8 3279.83   305.7 3281.75   318.4 3291.31
   325.2 3295.67   350.4 3316.21   355.4 3319.11   359.8 3321.04368.2639 3323.71
#Mann= 4 ,-1,0
       0      .1       0     289    .045       0   300.8      .1       0
  306.29     .06       0
#XS Ineff= 2 , 0
          270.42 3286.88
Permanent Ineff=
       F       F
Bank Sta=289,300.8
XS Rating Curve= 0 ,0
Exp/Cntr(USF)=0,0
Exp/Cntr=0.3,0.1

Type RM Length L Ch R = 1 ,26762   ,208.9,211.6,210.2
XS GIS Cut Line= 4
2336692.36729121548140.2762821652336654.64358909 548306.73960263
2336795.35898589548391.1688407082336882.78216858548401.947041314
#Sta/Elev= 30
       0 3282.82    25.5 3282.73      41 3281.23    50.1  3281.8    74.5 3280.37
    99.4  3279.6   128.1 3279.47   160.9  3278.6   177.1 3277.25     191 3274.39
   202.7 3274.03   214.4 3271.56   219.1  3271.5   228.4 3272.36   237.7 3274.46
   253.2 3275.34   275.1 3275.31   281.5  3273.9   284.4 3273.09   289.1  3272.9
   298.4 3273.92   307.7 3274.84   321.7 3274.88   331.1 3276.15   347.7 3275.85
   351.7 3276.95   363.8 3284.48   371.9 3288.58   400.1    3307422.8703 3317.59
#Mann= 7 ,-1,0
       0      .1       0     140     .08       0  180.68      .1       0
  240.68     .08       0   281.5    .045       0   298.4     .08       0
  300.68      .1       0
#XS Ineff= 2 , 0
          261.97 3280.05
Permanent Ineff=
       F       F
Bank Sta=281.5,298.4
XS Rating Curve= 0 ,0
Exp/Cntr(USF)=0,0
Exp/Cntr=0.3,0.1

Type RM Length L Ch R = 1 ,26551   ,127.3,116.2,103.3
XS GIS Cut Line= 5
2336669.01452323548189.9757627352336628.89566542548324.104481384
2336620.51262051548482.7835458562336690.57092444548526.495137201
2336865.41728982548512.722991983
#Sta/Elev= 30
       0  3281.3    32.6 3279.61    61.1    3279   128.6 3277.28   136.9 3277.52
   157.1 3276.37   160.7 3275.65   169.1 3275.09   177.1 3273.35   193.1  3272.5
   253.2 3270.76   265.2 3269.75   288.4  3269.1   322.1 3269.38   341.2 3267.75
   350.4 3266.95  357.47 3267.74   364.5 3269.04   378.8 3269.78   403.1 3270.14
   419.2 3271.08   451.3 3271.23   479.4 3269.98   492.1 3270.86   503.5 3273.48
   518.1 3278.95   544.1 3292.95   551.6 3296.24   551.6 3296.25556.8648 3298.69
#Mann= 6 ,-1,0
       0      .1       0    61.1     .08       0   160.7      .1       0
   341.2    .045       0  357.47      .1       0   551.6     .06       0
#XS Ineff= 2 , 0
                           428.1         3272.91
Permanent Ineff=
       F       F
Bank Sta=341.2,357.47
XS Rating Curve= 0 ,0
Exp/Cntr(USF)=0,0
Exp/Cntr=0.3,0.1

Type RM Length L Ch R = 1 ,26434   ,187.1,198,203.2
XS GIS Cut Line= 3
2336318.85618053548630.1523085242336584.16308894548618.220441014
2336850.05426233548558.709542626
#Sta/Elev= 30
       0 3279.35     5.3 3275.87     9.3 3274.13    36.7 3272.03    55.8 3267.32
    69.4 3264.72   117.1 3262.29   125.4 3262.45   137.5 3263.99   153.5 3263.66
   201.4 3264.66   241.6 3264.61   265.6 3266.73   290.2 3265.67  294.993264.427
   298.4 3263.46   302.5 3263.59  305.273264.415   310.7 3265.96   314.8 3266.33
   339.4  3265.7   351.7 3266.79   368.1 3266.93     405 3268.64     449 3269.53
   478.7 3267.92   490.1 3268.67   504.3 3271.25   519.7 3277.63     538 3286.84
#Mann= 3 ,-1,0
       0      .1       0  294.99    .045       0  305.27      .1       0
#XS Ineff= 2 , 0
          145.51 3270.61  450.93         3270.93
Permanent Ineff=
       F       F
Bank Sta=294.99,305.27
XS Rating Curve= 0 ,0
Exp/Cntr=0.3,0.1

Type RM Length L Ch R = 1 ,26236   ,202.2,195.9,191.3
XS GIS Cut Line= 4
2336362.78548838548798.6766252582336583.76642478548771.054008207
2336707.44041476 548799.932198762336869.40939655 548772.30958171
#Sta/Elev= 30
       0 3286.65     9.8 3283.47    21.6  3278.1    41.7 3265.41    45.7 3263.49
    52.8  3261.7    61.9 3258.32    74.3 3258.01    90.1 3256.34   154.6 3259.45
   194.9 3259.44   199.7  3260.1   235.4 3261.73     256 3261.61   260.1  3261.1
   267.2 3258.02   272.4 3256.58   276.5 3256.54   282.83258.023   288.8 3259.91
   309.4 3261.28   342.2 3260.95   366.8 3261.78   395.1 3261.18   419.4  3261.8
   427.5 3261.23   488.4 3262.91   492.5 3264.13   496.5 3266.14     514 3276.95
#Mann= 4 ,-1,0
       0      .1       0   267.2    .045       0   282.8      .1       0
   509.7     .06       0
#XS Ineff= 2 , 0
          131.56 3266.61  366.08         3265.33
Permanent Ineff=
       F       F
Bank Sta=267.2,282.8
XS Rating Curve= 0 ,0
Exp/Cntr(USF)=0,0
Exp/Cntr=0.3,0.1

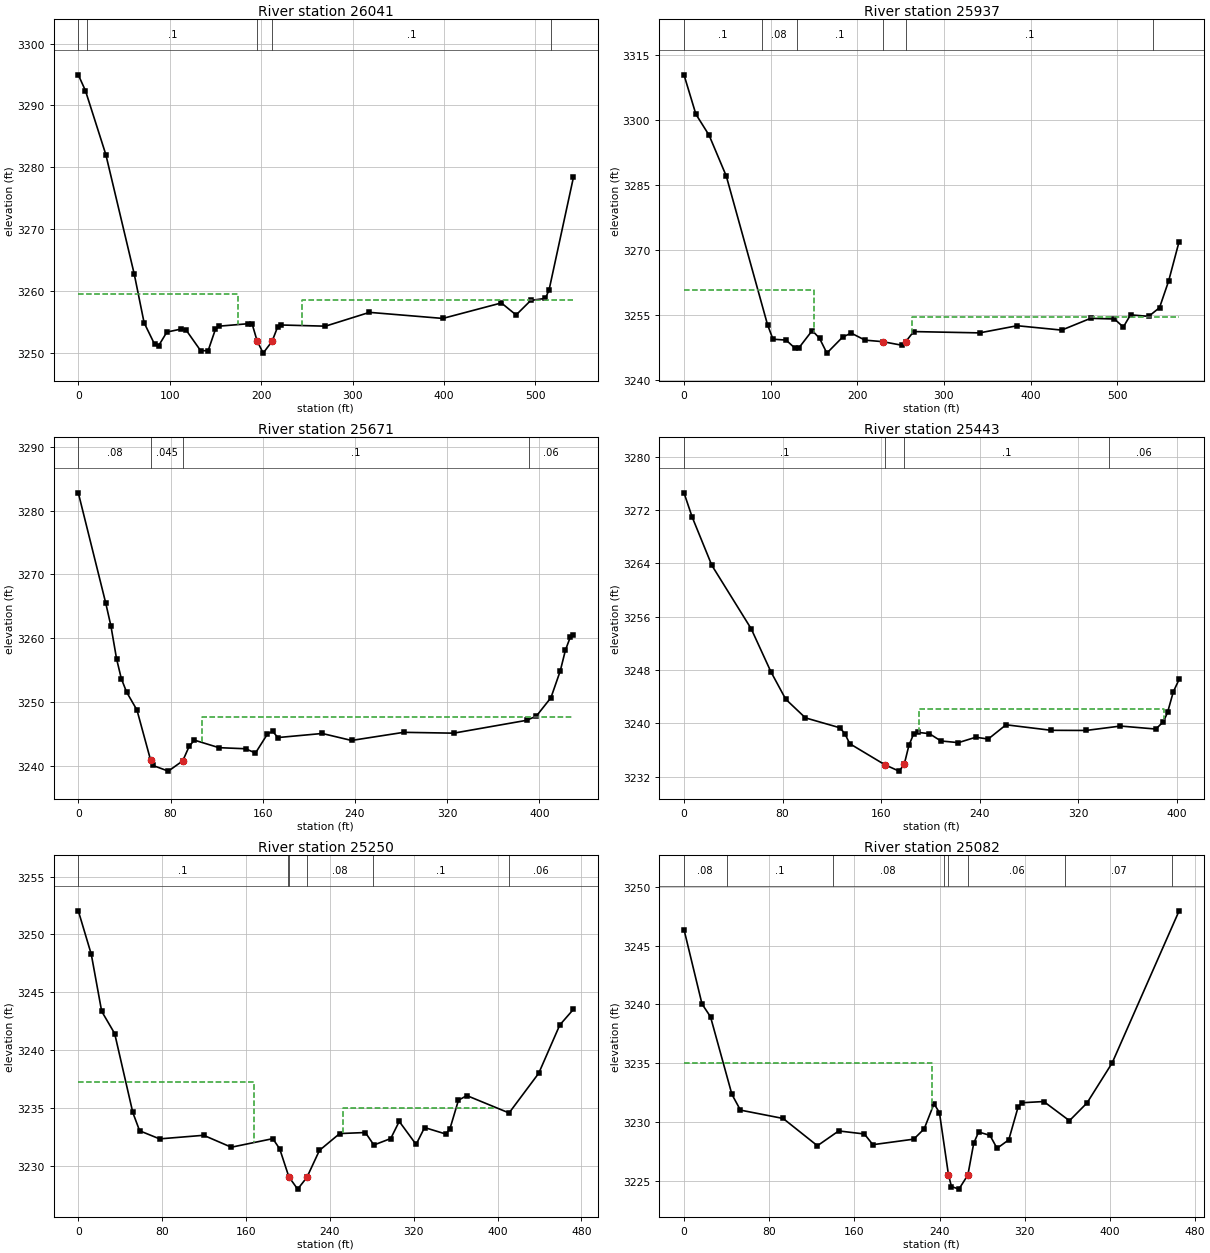
Type RM Length L Ch R = 1 ,26041   ,101.1,103.4,104.4
XS GIS Cut Line= 3
2336361.18565078548919.8337237352336457.28914011548966.943085613
2336890.75414609548935.534137008
#Sta/Elev= 30
       0 3294.95     7.8  3292.4    30.1 3282.09    61.2 3262.79      72 3254.93
    83.5 3251.45      88 3251.26    96.9 3253.43   112.6 3253.92   117.9 3253.76
   133.8 3250.43     142 3250.41     150 3253.88     154 3254.38   186.1 3254.78
   190.1 3254.76195.60453252.006   202.2 3250.03     212 3251.94   218.2 3254.32
   222.2 3254.57   270.3 3254.38   318.5 3256.61   398.7 3255.63   462.8 3258.13
   478.9 3256.19   494.9 3258.53     511 3258.87     515 3260.26   541.6  3278.4
#Mann= 5 ,-1,0
       0     .08       0      10      .1       0195.6045    .045       0
     212      .1       0  517.03     .06       0
#XS Ineff= 2 , 0
          174.42 3259.51  245.18         3258.66
Permanent Ineff=
       F       F
Bank Sta=195.6045,212
XS Rating Curve= 0 ,0
Exp/Cntr(USF)=0,0
Exp/Cntr=0.3,0.1

Type RM Length L Ch R = 1 ,25937   ,272.2,266.2,250.5
XS GIS Cut Line= 4
2336366.58577202549178.7813289882336519.09959404549062.294095938
2336698.69839245549055.9029783832336889.76906395548997.644868475
#Sta/Elev= 30
       0 3310.41    13.7 3301.34      29 3296.46    48.8 3287.06    96.4 3252.78
   102.7 3249.43   117.8 3249.23   127.8 3247.41   132.9 3247.51     148 3251.43
   156.4 3249.65   164.9 3246.22   183.2 3249.94     193 3250.83     209 3249.21
   229.2 3248.87     252 3248.02   255.9 3248.86     265 3251.19   341.1 3250.89
   384.6 3252.54   435.9 3251.53   469.3 3254.25   496.8 3254.09     507 3252.23
   515.3 3255.05   536.3  3254.7   548.8 3256.71   559.3 3262.85   571.4 3271.96
#Mann= 6 ,-1,0
       0      .1       0      90     .08       0     130      .1       0
   229.2    .045       0   255.9      .1       0  541.62     .06       0
#XS Ineff= 2 , 0
           150.5 3260.88  263.05         3254.66
Permanent Ineff=
       F       F
Bank Sta=229.2,255.9
XS Rating Curve= 0 ,0
Exp/Cntr=0.3,0.1

Type RM Length L Ch R = 1 ,25671   ,221,228.1,234.4
XS GIS Cut Line= 3
2336507.17644114 549341.084378252336667.26206268549256.333166845
2336902.68209437549177.232036201
#Sta/Elev= 30
       0 3282.77    23.8 3265.52    28.3 3261.94    33.2  3256.8    37.3 3253.71
    41.9  3251.6    50.9 3248.78    62.8  3240.9    64.5 3240.13    78.1 3239.23
   90.613240.841    96.2 3243.12   100.7 3244.08     122  3242.9   145.1 3242.73
   153.7 3242.06   164.1 3245.04   168.6 3245.46   173.1 3244.48   211.6 3245.12
     237 3244.03   282.3  3245.3   325.6 3245.17   388.9 3247.18   397.3 3247.83
     410 3250.72   418.1 3254.92   422.6 3258.18   426.8  3260.2   429.5 3260.55
#Mann= 4 ,-1,0
       0     .08       0    62.8    .045       0   90.61      .1       0
  391.14     .06       0
#XS Ineff= 2 , 0
                          107.04         3247.64
Permanent Ineff=
       F       F
Bank Sta=62.8,90.61
XS Rating Curve= 0 ,0
Exp/Cntr(USF)=0,0
Exp/Cntr=0.3,0.1

Type RM Length L Ch R = 1 ,25443   ,203.5,193.1,180.9
XS GIS Cut Line= 3
2336537.61506701549483.4047372352336732.65282125549481.254232019
 2336908.1776791549371.598721947
#Sta/Elev= 30
       0 3274.61     6.6 3270.99    22.6 3263.72    54.6 3254.18    70.6 3247.72
    82.6 3243.61    98.6 3240.81   126.6 3239.32   130.6 3238.43   134.6 3236.93
     163 3233.78   174.6 3232.81   178.8 3233.81   182.6 3236.67   186.4 3238.37
   190.4 3238.62   199.2 3238.44   208.6 3237.34   222.8 3237.09   236.9  3237.9
     247 3237.63   261.5 3239.77   298.2 3238.94   326.5 3238.92   354.4 3239.58
   383.1 3239.13   389.3 3240.25   392.6 3241.62   397.3 3244.73     402 3246.59
#Mann= 4 ,-1,0
       0      .1       0     163    .045       0   178.8      .1       0
  345.05     .06       0
#XS Ineff= 1 ,-1
   191.1   389.7 3242.19
Permanent Ineff=
       F
Bank Sta=163,178.8
XS Rating Curve= 0 ,0
Exp/Cntr=0.3,0.1

Type RM Length L Ch R = 1 ,25250   ,170.6,168.2,165.7
XS GIS Cut Line= 3
2336602.14350539549779.609174679 2336821.0295254549620.207965658
2337020.99765246549594.806164502
#Sta/Elev= 30
       0 3252.04    12.4 3248.28    22.3 3243.36    34.7 3241.44      52 3234.62
    58.5 3233.04    77.6 3232.34   119.6 3232.65     146 3231.62   185.6 3232.36
   192.2 3231.47200.89753229.061   209.3    3228218.09733229.013   230.1 3231.35
   249.4  3232.8   273.9 3232.89     282 3231.81   298.1 3232.37   306.2 3233.85
   322.3 3231.86   330.4 3233.32   350.6 3232.76   354.6 3233.22   362.7 3235.68
   370.7 3236.08     411 3234.58   439.3 3238.01   459.4 3242.18   472.4 3243.53
#Mann= 6 ,-1,0
       0      .1       0     200     .08       0200.8975    .045       0
218.0973     .08       0  280.78      .1       0  410.78     .06       0
#XS Ineff= 2 ,-1
       0  167.74 3237.27  252.39   396.2 3235.03
Permanent Ineff=
       F       F
Bank Sta=200.8975,218.0973
XS Rating Curve= 0 ,0
Exp/Cntr(USF)=0,0
Exp/Cntr=0.3,0.1

Type RM Length L Ch R = 1 ,25082   ,65.8,78.9,93.8
XS GIS Cut Line= 4
2336623.36128794549825.6609553052336856.26356855549805.934259406
2336910.35289601549755.0266570872337066.89377314549742.936101536
#Sta/Elev= 30
       0 3246.36    16.9 3240.03    24.9 3238.94      45 3232.34      53    3231
    93.1 3230.29   125.3 3227.97   145.3 3229.23   169.4 3228.97   177.4 3228.06
   215.8 3228.53   225.6 3229.41   234.8 3231.54   239.9 3230.79   248.4 3225.49
   251.2  3224.5   258.2 3224.28   266.6 3225.48   272.1 3228.18   276.7 3229.14
   287.4 3228.85     294 3227.75     305 3228.47   313.9  3231.3   317.9 3231.63
   337.9 3231.73     362  3230.1   378.5 3231.61   402.1 3235.01     465 3247.95
#Mann= 8 ,-1,0
       0     .08       0      40      .1       0     140     .08       0
  243.74     .06       0   248.4    .045       0   266.6     .06       0
  358.01     .07       0  458.01     .03       0
#XS Ineff= 2 , 0
          232.56    3235
Permanent Ineff=
       F       F
Bank Sta=248.4,266.6
XS Rating Curve= 0 ,0
Exp/Cntr(USF)=0,0
Exp/Cntr=0.3,0.1

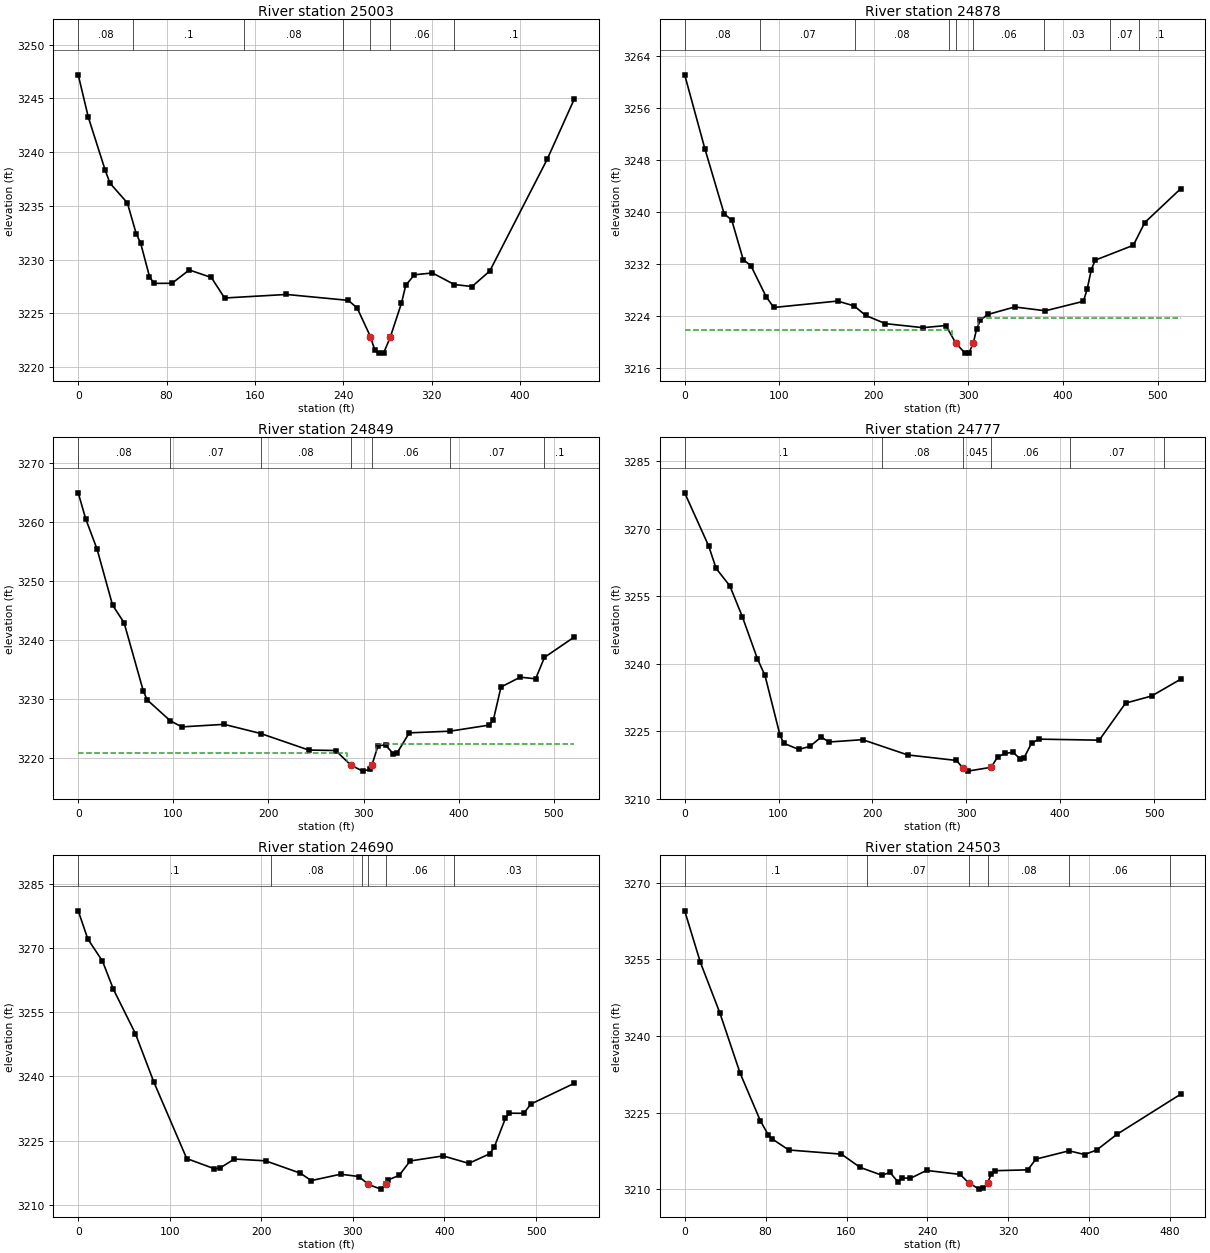
Type RM Length L Ch R = 1 ,25003   ,122.4,124.8,128.5
BEGIN DESCRIPTION:
structure xs 4
END DESCRIPTION:
XS GIS Cut Line= 2
2336619.72153443549870.010466844 2337068.5890615549863.104812582
#Sta/Elev= 30
       0 3247.19     9.1 3243.26    24.5 3238.29    28.8  3237.1    44.5 3235.27
    52.5  3232.4    56.5 3231.53    64.5 3228.42    68.5 3227.78    84.9 3227.79
   100.5 3229.03   120.5 3228.33   132.5 3226.42   188.5 3226.75   244.5  3226.2
   252.5 3225.49   264.5 3222.83   268.5 3221.55   272.5 3221.29   276.5 3221.32
   282.43222.756   292.5 3225.91   296.5 3227.61   304.3 3228.58   320.6 3228.75
   340.5 3227.67   356.5 3227.49   372.5 3228.93   424.5 3239.33   448.9 3244.91
#Mann= 7 ,-1,0
       0     .08       0      50      .1       0     150     .08       0
     240     .06       0   264.5    .045       0   282.4     .06       0
     340      .1       0
Bank Sta=264.5,282.4
XS Rating Curve= 0 ,0
Exp/Cntr(USF)=0,0
Exp/Cntr=0.5,0.3

Type RM Length L Ch R = 1 ,24878   ,29.9,29.2,29.2
BEGIN DESCRIPTION:
structure xs 3
END DESCRIPTION:
XS GIS Cut Line= 2
2336590.97022167549946.6050433462337109.58082847550024.109580525
#Sta/Elev= 30
       0 3261.16    21.4 3249.75    41.7 3239.77    49.8 3238.77    61.9  3232.7
      70 3231.77    86.2 3226.98    94.2 3225.33   161.7 3226.32   179.2 3225.57
   191.3 3224.11   212.3 3222.84     252 3222.22   276.2 3222.55  286.88 3219.79
   296.5  3218.3   300.5  3218.3  305.15 3219.84   308.6 3221.95   312.6 3223.38
   320.7 3224.26     349 3225.41   381.4 3224.82   421.6 3226.28   425.6 3228.16
   429.9 3231.12     434 3232.61   474.4 3234.91   486.5 3238.41   524.4 3243.61
#Mann= 9 ,-1,0
       0     .08       0      80     .07       0     180     .08       0
     280     .06       0  286.88    .045       0  305.15     .06       0
     380     .03       0     450     .07       0     480      .1       0
#XS Ineff= 2 , 0
             283 3221.89     310         3223.67
Permanent Ineff=
       F       F
Bank Sta=286.88,305.15
XS Rating Curve= 0 ,0
Exp/Cntr(USF)=0,0
Exp/Cntr=0.5,0.3

Type RM Length L Ch R = 1 ,24849   ,74.5,71.8,67.4
BEGIN DESCRIPTION:
structure xs 2
END DESCRIPTION:
XS GIS Cut Line= 2
2336580.44491415549975.3104274862337096.18498254550050.901272389
#Sta/Elev= 30
       0 3264.94     7.8 3260.57    19.9 3255.36    36.1 3245.93    48.2 3242.95
    68.5 3231.35    72.5 3229.88    96.8 3226.34   108.9 3225.31   153.4 3225.74
   191.8 3224.19   242.3 3221.39   270.6 3221.31   286.4 3218.86   298.9 3217.82
     307 3218.13  308.81  3218.9   315.2 3222.14   323.1 3222.23   331.2 3220.76
   335.3 3220.94     348  3224.3   390.6 3224.58   432.3 3225.62   436.3 3226.45
   444.4 3232.06   464.6 3233.73   480.8 3233.45   490.1 3237.08   521.3 3240.51
#Mann= 7 ,-1,0
       0     .08       0    96.8     .07       0   191.8     .08       0
   286.4    .045       0  308.81     .06       0   390.6     .07       0
   490.1      .1       0
#XS Ineff= 2 , 0
             283 3220.83     313          3222.4
Permanent Ineff=
       F       F
Bank Sta=286.4,308.81
XS Rating Curve= 0 ,0
Exp/Cntr(USF)=0,0
Exp/Cntr=0.5,0.3

Type RM Length L Ch R = 1 ,24777   ,86.9,87.4,84.6
XS GIS Cut Line= 2
 2336554.6399962550086.2861047252337082.79975127550089.639499995
#Sta/Elev= 30
       0 3277.97    25.5 3266.18    33.5 3261.16    48.1 3257.29    61.5 3250.39
    77.5 3241.07    85.5  3237.4   101.5 3224.13   105.5 3222.32   121.5 3220.93
   133.5 3221.64   145.5  3223.7   153.5 3222.59   189.5 3223.11   237.5 3219.72
   289.5 3218.49  295.95  3216.9   301.5 3216.12   326.4 3216.97   333.5 3219.32
   341.5 3220.07   349.5 3220.31   357.5 3218.85   361.5  3219.1   369.5 3222.36
   377.5 3223.23   441.5    3223   469.6 3231.24   497.3 3232.81   528.2 3236.54
#Mann= 6 ,-1,0
       0      .1       0     210     .08       0  295.95    .045       0
   326.4     .06       0     410     .07       0     510      .1       0
Bank Sta=295.95,326.4
XS Rating Curve= 0 ,0
Exp/Cntr(USF)=0,0
Exp/Cntr=0.3,0.1

Type RM Length L Ch R = 1 ,24690   ,185.7,186.7,187.5
XS GIS Cut Line= 2
2336553.65322229 550170.50703964 2337095.2281364550172.420731916
#Sta/Elev= 30
       0 3278.64    10.5 3272.06    26.5 3266.91    38.5  3260.3    62.5 3249.98
    82.5 3238.74   118.5 3220.85   148.4  3218.5   154.5  3218.6   170.5 3220.74
   204.6 3220.32   242.5 3217.45   254.5 3215.71   286.5  3217.2   306.5 3216.66
     317  3214.8   330.5 3213.72     336 3214.81   338.5 3215.87   350.5 3216.92
   362.5 3220.29   398.5 3221.47   426.5 3219.73   449.4 3221.96   454.5  3223.6
   466.5 3230.22   470.5 3231.44   486.5  3231.4   494.5 3233.58   541.6 3238.39
#Mann= 6 ,-1,0
       0      .1       0     210     .08       0     310     .06       0
     317    .045       0     336     .06       0     410     .03       0
Bank Sta=317,336
XS Rating Curve= 0 ,0
Exp/Cntr(USF)=0,0
Exp/Cntr=0.3,0.1

Type RM Length L Ch R = 1 ,24503   ,150.3,148.2,147.7
XS GIS Cut Line= 2
2336581.46715836550341.1441452652337071.06286782550367.971307427
#Sta/Elev= 30
       0 3264.49    15.5 3254.42    34.8  3244.5    54.8 3232.72    74.8 3223.41
    82.8 3220.59    86.8 3219.81   102.9 3217.69   154.9 3216.88   173.5 3214.28
     195 3212.75     203 3213.29     211 3211.41     215 3212.25     223 3212.13
   239.1 3213.69   272.3 3212.91  280.61 3211.29   291.1 3210.03   295.3 3210.19
   299.5 3211.31   303.2 3213.01   307.2 3213.64   339.2  3213.8   347.2  3215.9
     380 3217.53   395.3  3216.8   407.3 3217.68   427.3 3220.75   490.3  3228.6
#Mann= 6 ,-1,0
       0      .1       0     180     .07       0  280.61    .045       0
   299.5     .08       0     380     .06       0     480      .1       0
Bank Sta=280.61,299.5
XS Rating Curve= 0 ,0
Exp/Cntr(USF)=0,0
Exp/Cntr=0.3,0.1