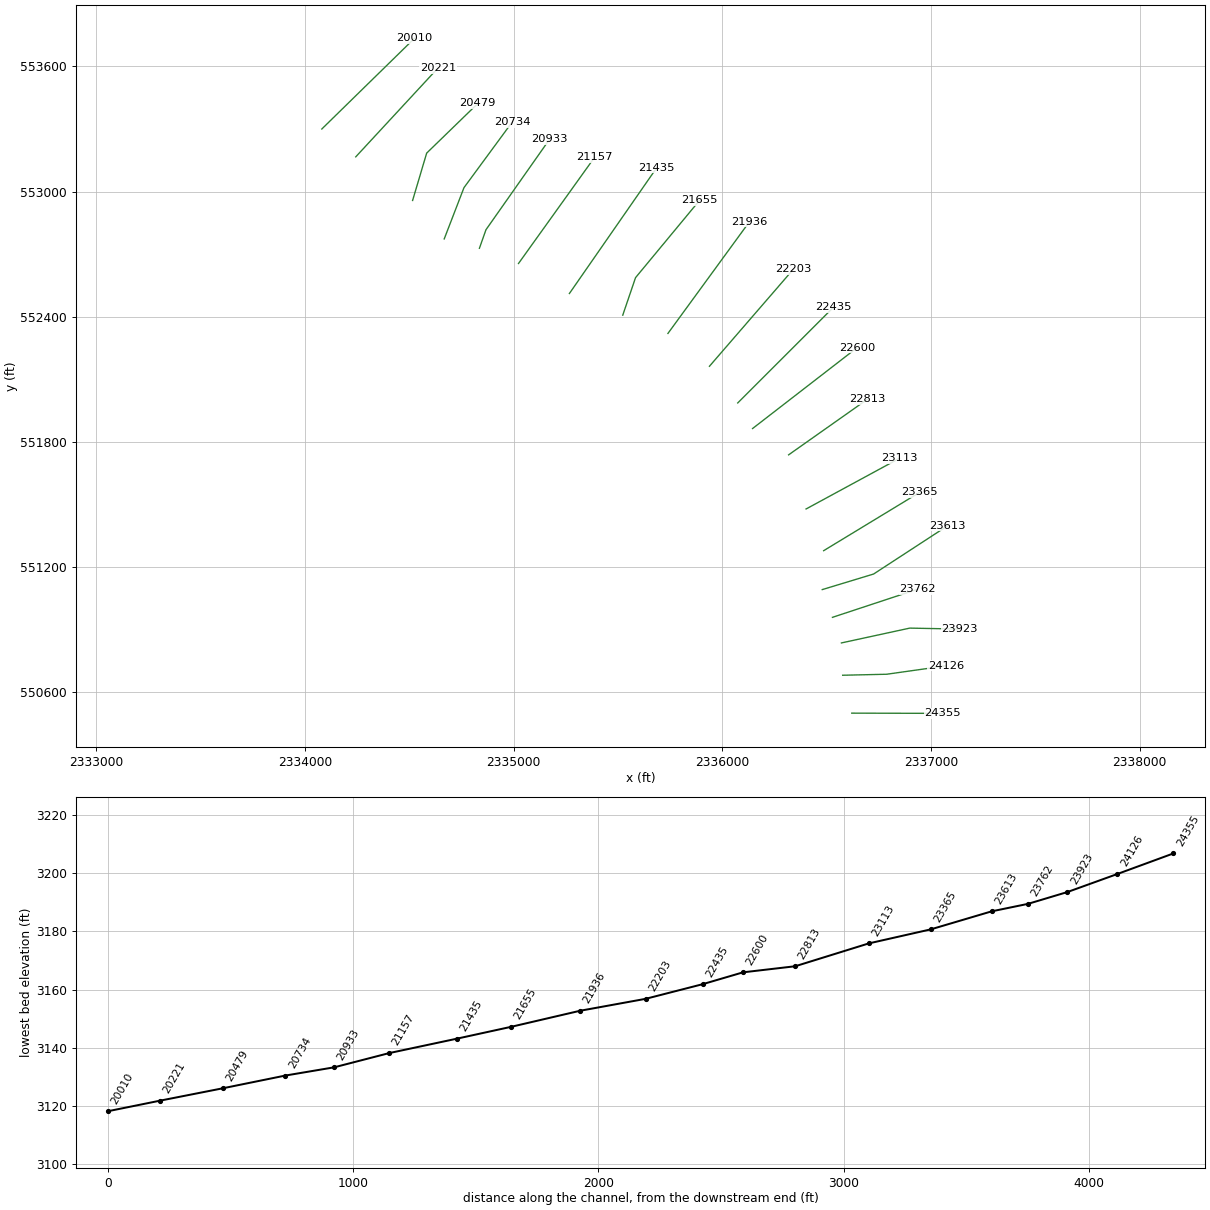
HEC-RAS study LTTLRV2.prj: LTTLRV2

--- LTTLRV2.g01 (geometry) --- (continued)

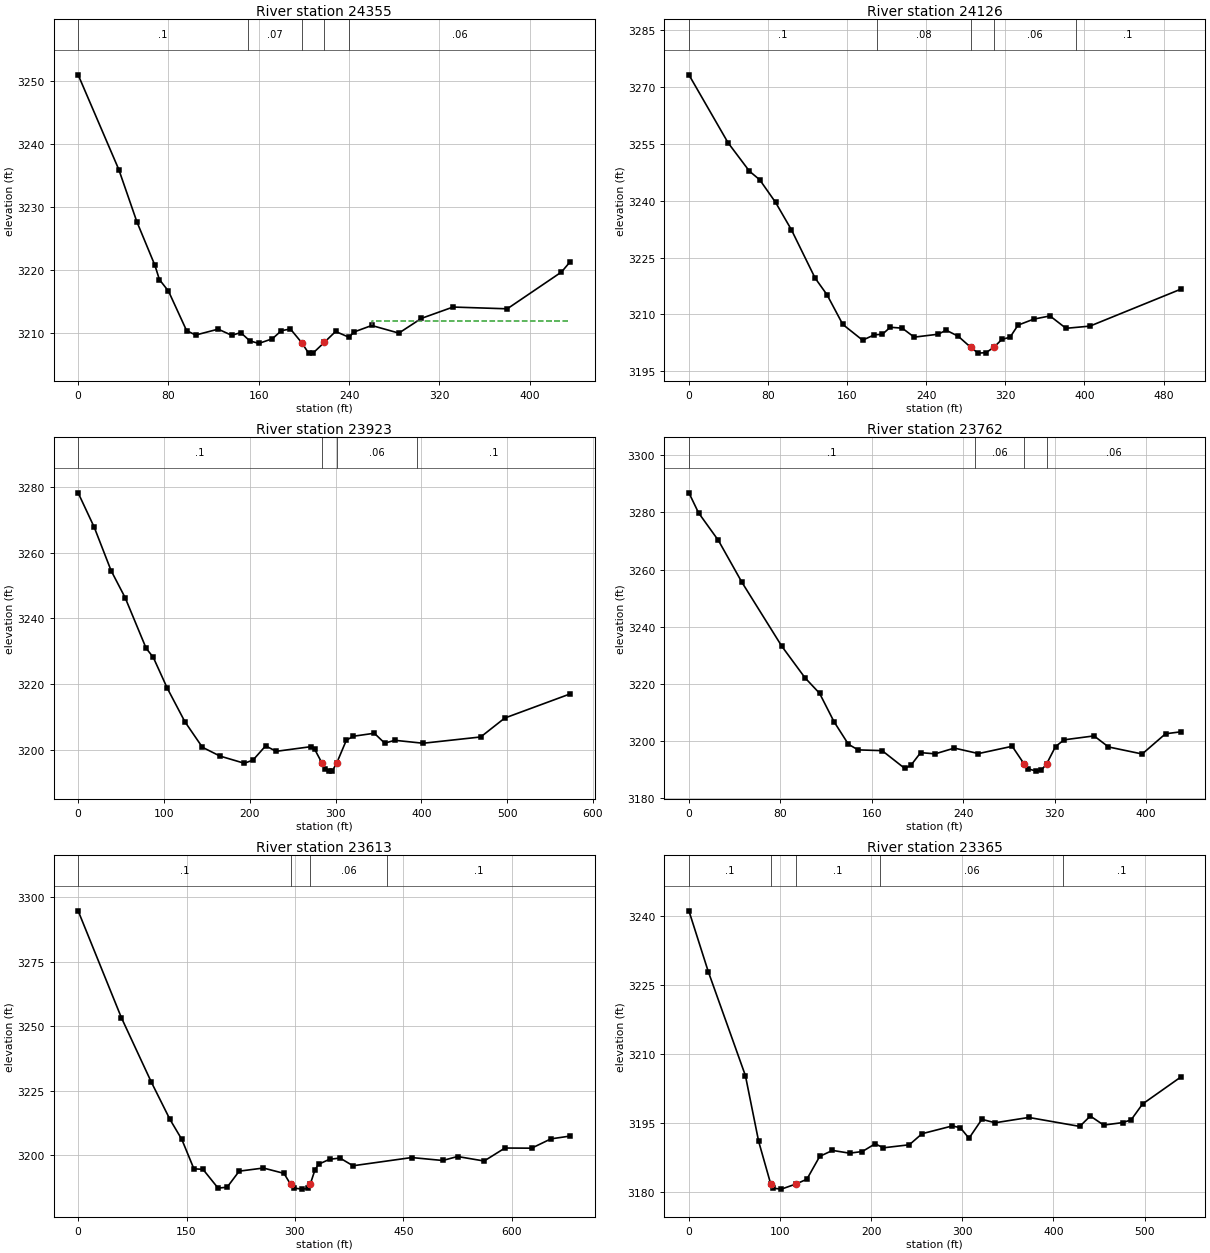
Type RM Length L Ch R = 1 ,24355   ,224.3,228.4,231.5
XS GIS Cut Line= 2
2336620.20907353550499.7294580862337055.83161195550498.633691041
#Sta/Elev= 30
       0 3251.05      36 3236.01      52 3227.71      68 3220.78      72 3218.51
      80 3216.69      96 3210.43     104 3209.71     124 3210.65     136 3209.67
     144  3210.1     152 3208.79     160 3208.38     172 3209.12     180 3210.41
     188 3210.67   197.9 3208.52     204 3206.87     208 3206.84     218 3208.55
     228 3210.28     240 3209.35     244 3210.18     260 3211.23     284 3210.02
     304 3212.36     332 3214.16     380 3213.88     428 3219.72   435.6 3221.33
#Mann= 5 ,-1,0
       0      .1       0     150     .07       0   197.9    .045       0
     218     .07       0     240     .06       0
#XS Ineff= 2 , 0
                          260.01         3211.99
Permanent Ineff=
       F       F
Bank Sta=197.9,218
XS Rating Curve= 0 ,0
Exp/Cntr=0.3,0.1

Type RM Length L Ch R = 1 ,24126   ,202.3,203.6,204.4
XS GIS Cut Line= 3
 2336576.6175296550681.4628773382336787.56669973550686.247108029
2337071.12499082550726.404313802
#Sta/Elev= 30
       0 3273.23    39.6 3255.29    61.2 3247.79    71.6 3245.53    87.6 3239.57
   103.6 3232.35   127.6 3219.58   139.6  3215.2   155.6 3207.34   175.6 3203.19
   187.6 3204.61   195.6 3204.74   203.6  3206.6   215.7 3206.36   227.8 3203.99
     252 3204.76   260.1 3205.82   272.2 3204.25   284.9 3201.32   292.4 3199.77
   300.5  3199.9   308.6 3201.36   316.5 3203.41   324.7 3203.96   332.8 3207.16
   348.6 3208.74   365.1 3209.59   381.3 3206.32   405.5  3206.9   497.4 3216.65
#Mann= 5 ,-1,0
       0      .1       0     190     .08       0   284.9    .045       0
   308.6     .06       0     391      .1       0
Bank Sta=284.9,308.6
XS Rating Curve= 0 ,0
Exp/Cntr(USF)=0,0
Exp/Cntr=0.3,0.1

Type RM Length L Ch R = 1 ,23923   ,159,160.9,163.1
XS GIS Cut Line= 3
2336570.63830505550836.3671532442336897.96894671550907.399893999
 2337136.3173104550902.849078475
#Sta/Elev= 30
       0  3278.2    18.8 3267.71    38.4 3254.55    54.8 3246.31    79.3  3230.9
    87.5 3228.21   103.9 3218.78   124.4  3208.6   144.8 3200.83   165.3 3198.15
   193.7 3195.96   203.8 3196.93   218.5 3201.25   230.8 3199.59   271.7 3201.02
   275.8 3200.16   284.23196.012   288.1 3194.13   292.2 3193.57   296.3 3193.67
  301.373196.032   312.6 3202.97   320.8 3204.18   345.2 3205.09   357.2 3202.09
   369.2 3202.94   402.1 3202.05   469.2 3203.96   497.2 3209.71   573.3 3217.04
#Mann= 4 ,-1,0
       0      .1       0   284.2    .045       0  301.37     .06       0
  394.95      .1       0
Bank Sta=284.2,301.37
XS Rating Curve= 0 ,0
Exp/Cntr=0.3,0.1

Type RM Length L Ch R = 1 ,23762   ,142.8,148.5,155
XS GIS Cut Line= 2
 2336527.6694913550959.0695854522336936.24279223551093.984890912
#Sta/Elev= 30
       0 3286.84     8.4 3279.86    25.8 3270.18    46.4 3255.52    81.2 3233.21
   101.6 3222.12   114.3 3216.72   126.9 3206.81   139.5  3198.9     148 3196.93
     169 3196.67   188.9 3190.42   194.3 3191.59   202.7 3195.97   215.4 3195.54
   232.2 3197.56   253.3 3195.64   282.8 3198.19   293.1 3192.08   296.6 3190.32
   303.8  3189.5     308 3189.72   312.9 3192.02   320.7  3198.1   328.2 3200.45
   354.4 3201.82     367 3197.96   396.5 3195.49   416.9 3202.56   430.3 3203.25
#Mann= 4 ,-1,0
       0      .1       0     250     .06       0   293.1    .045       0
   312.9     .06       0
Bank Sta=293.1,312.9
XS Rating Curve= 0 ,0
Exp/Cntr(USF)=0,0
Exp/Cntr=0.3,0.1

Type RM Length L Ch R = 1 ,23613   ,248.3,248,246.2
XS GIS Cut Line= 3
2336478.87033826551092.0711986362336724.77979573  551166.7051974
2337079.76971294551398.261962799
#Sta/Elev= 30
       0 3294.71    59.9  3253.3   101.3 3228.37     127 3213.96   143.5 3206.17
   160.2 3194.79   172.8 3194.58   193.7 3187.31   206.2 3187.66   222.9 3193.88
   256.4 3195.09   284.9 3193.02  294.02 3188.78   299.2 3187.29   310.4 3186.92
   318.3 3187.21  321.26 3188.83   327.7 3194.32   332.7 3196.55   347.9 3198.47
   362.4 3198.96   380.4 3195.97   461.6 3199.15   504.6 3198.01   525.1 3199.55
   561.9 3197.81   590.7 3202.84   627.6 3202.78   654.3 3206.38   680.8 3207.47
#Mann= 4 ,-1,0
       0      .1       0  294.02    .045       0  321.26     .06       0
  426.99      .1       0
Bank Sta=294.02,321.26
XS Rating Curve= 0 ,0
Exp/Cntr(USF)=0,0
Exp/Cntr=0.3,0.1

Type RM Length L Ch R = 1 ,23365   ,252.9,252.8,247.1
XS GIS Cut Line= 2
2336485.56826123551278.6561955482336946.76809975551559.012113985
#Sta/Elev= 30
       0 3241.03    21.2 3227.88      62 3205.31    76.5 3191.08    89.63181.949
      92 3180.94   101.4 3180.73   117.3 3181.83   129.4 3182.87   143.5 3187.82
   157.5 3189.12   176.2 3188.52   190.3 3188.88   204.3 3190.55   213.3 3189.68
   241.8 3190.34   255.8 3192.74     289 3194.42   297.8 3194.03   307.3 3191.75
   321.4 3195.85     336 3195.11   372.9 3196.26   428.8 3194.32   440.4 3196.57
     455 3194.61   475.8 3195.14   485.2 3195.74   497.7 3199.17   539.7 3205.02
#Mann= 5 ,-1,0
       0      .1       0    89.6    .045       0   117.3      .1       0
     210     .06       0     410      .1       0
Bank Sta=89.6,117.3
XS Rating Curve= 0 ,0
Exp/Cntr(USF)=0,0
Exp/Cntr=0.3,0.1

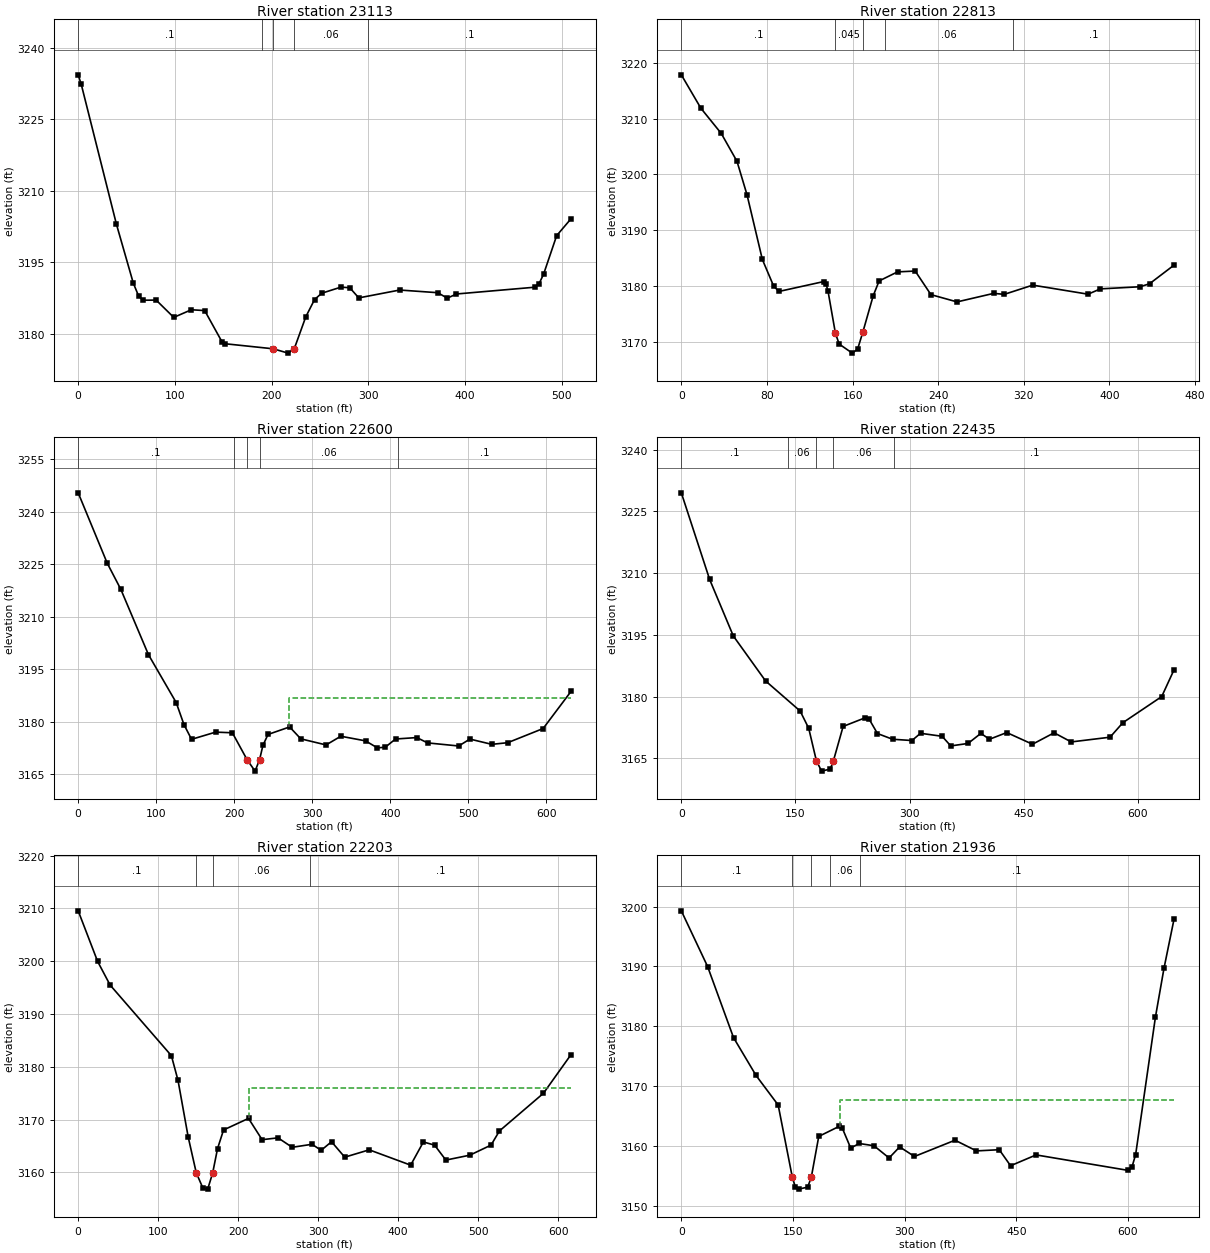
Type RM Length L Ch R = 1 ,23113   ,295.5,299.9,301.5
XS GIS Cut Line= 2
2336401.36580109551478.6370383922336849.16979367551721.675957447
#Sta/Elev= 30
       0  3234.3     3.2 3232.28    39.6 3202.91      57 3190.58    62.4 3187.93
    66.9    3187    80.6 3187.03    98.8  3183.4     117    3185   130.8 3184.83
   148.5 3178.34   151.4 3177.88   201.6 3176.81   217.1  3175.9   223.4 3176.82
   235.3 3183.51   244.4 3187.15   251.8 3188.47   271.7 3189.75   280.8 3189.62
   290.1 3187.49   332.4 3189.14   371.8 3188.58   381.6 3187.43   391.1 3188.31
     472 3189.73   476.5 3190.48   481.1 3192.42   494.7 3200.56   509.5 3204.09
#Mann= 5 ,-1,0
       0      .1       0     190     .06       0   201.6    .045       0
   223.4     .06       0     300      .1       0
Bank Sta=201.6,223.4
XS Rating Curve= 0 ,0
Exp/Cntr(USF)=0,0
Exp/Cntr=0.3,0.1

Type RM Length L Ch R = 1 ,22813   ,212,212.6,213.5
XS GIS Cut Line= 2
2336317.67276519551738.1456893942336693.81054191552003.557460763
#Sta/Elev= 30
       0 3217.82    18.3 3211.84    37.3 3207.34      52 3202.36    61.4 3196.35
    75.7  3184.8    86.3 3180.02    91.2 3179.08   133.1 3180.85   135.2 3180.45
   137.1 3179.08     144 3171.57   147.5 3169.67   159.7 3168.05   164.7 3168.77
   169.5 3171.75   179.3 3178.33   184.8 3180.96     202 3182.58   218.5 3182.73
   233.2 3178.51   257.6 3177.21   291.9 3178.74   301.7 3178.56   328.3 3180.21
     380 3178.59   391.5 3179.54   428.5 3179.92   437.4 3180.45   460.4  3183.8
#Mann= 5 ,-1,0
       0      .1       0     144    .045       0   169.5      .1       0
     190     .06       0     310      .1       0
Bank Sta=144,169.5
XS Rating Curve= 0 ,0
Exp/Cntr=0.3,0.1

Type RM Length L Ch R = 1 ,22600   ,163.3,165.4,168
XS GIS Cut Line= 2
 2336144.9310361551864.2460320112336644.40472014552250.811871768
#Sta/Elev= 30
       0 3245.33    37.2 3225.28    54.7 3217.78    90.1 3199.16   125.6 3185.52
   135.6 3179.22   145.3 3175.03   176.1 3177.08   197.6  3176.9   216.5 3169.21
   226.7 3165.96  232.54 3169.27   236.8 3173.32   243.3 3176.42     271 3178.56
   285.3 3175.17   317.7 3173.43   336.6 3175.91   368.3 3174.59   383.5 3172.59
   393.6 3172.78   406.7 3175.12     434 3175.53   447.8 3174.01   487.7 3173.13
     502  3175.1   530.1  3173.6   550.5 3174.07   595.9 3178.11   631.6 3188.68
#Mann= 5 ,-1,0
       0      .1       0     200     .06       0   216.5    .045       0
  232.54     .06       0     410      .1       0
#XS Ineff= 2 , 0
                          269.75         3186.88
Permanent Ineff=
       F       F
Bank Sta=216.5,232.54
XS Rating Curve= 0 ,0
Exp/Cntr(USF)=0,0
Exp/Cntr=0.3,0.1

Type RM Length L Ch R = 1 ,22435   ,230.3,231.9,233.3
XS GIS Cut Line= 2
2336073.81215077551986.957150774     2336531.686      552444.762
#Sta/Elev= 30
       0 3229.54    37.2 3208.48    68.3 3194.74   110.7  3183.8   156.1 3176.49
   167.4 3172.28  177.46 3164.39   184.3 3161.87   195.7 3162.37  199.86 3164.39
   212.6 3172.74   240.7 3174.78   246.6 3174.57   257.7 3171.01   277.6 3169.62
     303 3169.31   314.3 3171.07   342.7 3170.34     354    3168   376.7  3168.6
   393.6 3171.05   404.9 3169.62   427.6 3171.25   461.4 3168.41   489.8 3171.19
   512.3 3168.97   563.3 3170.12   580.2 3173.65   631.2    3180   647.5 3186.56
#Mann= 5 ,-1,0
       0      .1       0     140     .06       0  177.46    .045       0
  199.86     .06       0     280      .1       0
Bank Sta=177.46,199.86
XS Rating Curve= 0 ,0
Exp/Cntr=0.3,0.1

Type RM Length L Ch R = 1 ,22203   ,265.2,267.1,268.8
XS GIS Cut Line= 2
2335938.25227029552162.7820270712336341.08449439552628.766096282
#Sta/Elev= 30
       0 3209.54    24.3 3199.96    39.9 3195.49   116.5 3182.12   124.8 3177.43
   137.5 3166.73   147.6 3159.94   155.8 3157.08   161.9 3156.85   168.1  3159.9
   174.2 3164.52   181.7 3168.05   212.9 3170.24   229.9 3166.21   249.8 3166.56
   267.5 3164.77   292.3 3165.34   303.7  3164.2   316.7 3165.82   333.2  3162.9
   363.8 3164.29   415.6 3161.39   431.5 3165.78   445.5 3165.18   459.6 3162.35
   489.6 3163.28   516.1 3165.19   526.6 3167.87   581.6    3175     616 3182.31
#Mann= 4 ,-1,0
       0      .1       0   147.6    .045       0   168.1     .06       0
     290      .1       0
#XS Ineff= 2 , 0
                          212.96         3176.08
Permanent Ineff=
       F       F
Bank Sta=147.6,168.1
XS Rating Curve= 0 ,0
Exp/Cntr(USF)=0,0
Exp/Cntr=0.3,0.1

Type RM Length L Ch R = 1 ,21936   ,282.3,281.1,279.5
XS GIS Cut Line= 2
 2335739.3674587552320.0699960892336129.38584573552854.961307106
#Sta/Elev= 30
       0 3199.28    35.3 3189.97    70.1 3178.09   100.4 3171.75   130.1 3166.81
  149.16 3154.71   153.1 3153.15   157.5 3152.75   169.7 3153.08   174.6 3154.73
   184.6 3161.56   211.8 3163.23   216.1 3162.99   227.5 3159.62     239 3160.38
   258.8    3160   279.1 3157.96   293.3 3159.81   313.2 3158.21   367.7 3160.93
   396.5 3159.14   427.1 3159.34   442.3 3156.66   476.6 3158.47   600.4 3155.88
   605.3 3156.42   610.3 3158.52   636.9 3181.52   648.4 3189.68     662 3197.96
#Mann= 5 ,-1,0
       0      .1       0  149.16    .045       0   174.6      .1       0
     200     .06       0     240      .1       0
#XS Ineff= 2 , 0
                          212.56         3167.65
Permanent Ineff=
       F       F
Bank Sta=149.16,174.6
XS Rating Curve= 0 ,0
Exp/Cntr=0.3,0.1

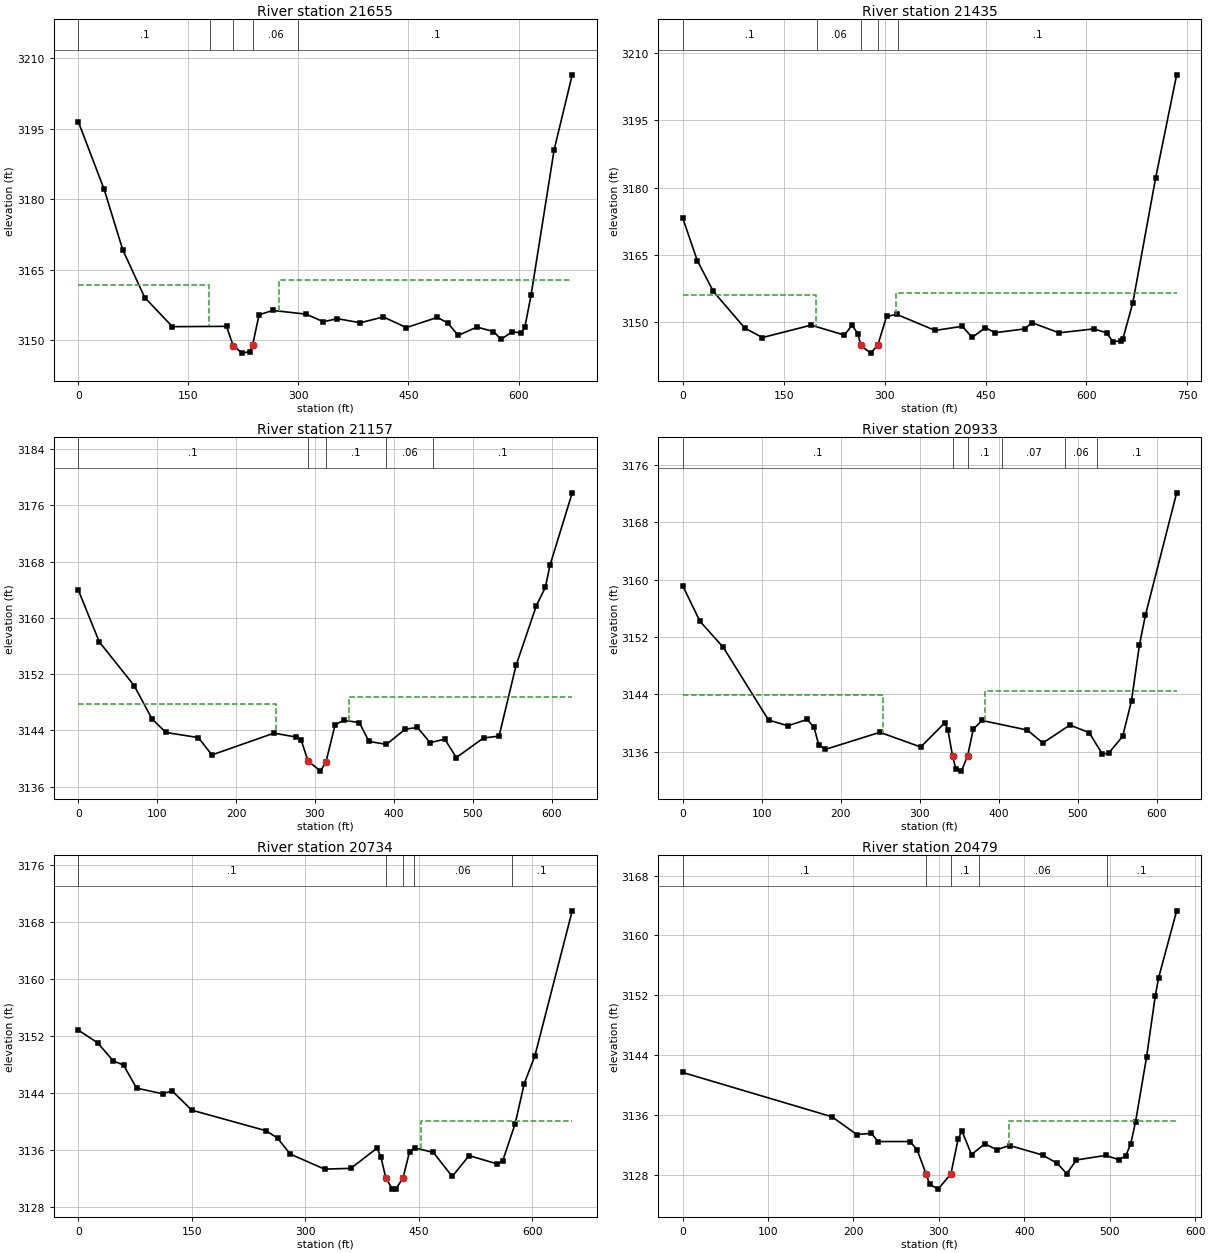
Type RM Length L Ch R = 1 ,21655   ,218,219.8,221.9
XS GIS Cut Line= 3
2335522.98104639552407.7346384022335584.21919922552587.621712348
2335892.32365566552959.834860034
#Sta/Elev= 30
       0 3196.51    35.3 3182.07    60.7 3169.19    90.6 3159.06   128.3 3152.86
   202.1 3152.93     211 3148.85   223.2 3147.23   233.6 3147.55  237.553148.863
   246.4 3155.38     265 3156.31   310.4 3155.53   334.2  3153.9     353 3154.56
   384.4 3153.69   415.8 3154.93   447.2 3152.66   489.4 3154.84   503.6 3153.63
   517.8 3151.01   543.4 3152.77   565.9 3151.83   576.3 3150.19   591.4 3151.77
     604 3151.53   608.7 3152.81   617.2 3159.64   648.5 3190.45   673.2 3206.44
#Mann= 5 ,-1,0
       0      .1       0     180     .06       0     211    .045       0
  237.55     .06       0  300.02      .1       0
#XS Ineff= 2 , 0
          178.65 3161.81   273.3         3162.69
Permanent Ineff=
       F       F
Bank Sta=211,237.55
XS Rating Curve= 0 ,0
Exp/Cntr(USF)=0,0
Exp/Cntr=0.3,0.1

Type RM Length L Ch R = 1 ,21435   ,278.3,277.9,277.6
XS GIS Cut Line= 2
2335267.42584449 552511.74076684     2335685.883      553114.797
#Sta/Elev= 30
       0 3173.29    21.7 3163.79    45.6 3156.91    92.5 3148.73   118.6 3146.65
   190.8 3149.41   240.3  3147.2   251.6 3149.38   260.3 3147.52   264.7 3144.89
   279.3 3143.18  290.02 3144.98     303 3151.36   318.2 3151.79   375.2 3148.23
   415.5 3149.15   430.2 3146.66   449.7 3148.86   464.3 3147.72   508.1 3148.58
   518.9 3149.96   559.2  3147.7   610.9 3148.57   629.8 3147.71   639.5 3145.69
   651.1 3145.96   654.2 3146.41   668.8 3154.34   702.8 3182.19     734 3205.13
#Mann= 5 ,-1,0
       0      .1       0     200     .06       0   264.7    .045       0
  290.02     .06       0     320      .1       0
#XS Ineff= 2 , 0
          198.31 3156.09  316.39         3156.53
Permanent Ineff=
       F       F
Bank Sta=264.7,290.02
XS Rating Curve= 0 ,0
Exp/Cntr=0.3,0.1

Type RM Length L Ch R = 1 ,21157   ,223.5,223.7,223.9
XS GIS Cut Line= 2
2335023.50736235552655.5577881462335388.06574093553164.599933569
#Sta/Elev= 30
       0 3163.98    26.6 3156.59    70.9 3150.35    93.4 3145.63   111.1 3143.69
   152.3 3142.96   169.3 3140.49     248 3143.59   275.9 3143.05   282.4 3142.65
   291.2 3139.65     307 3138.19   314.1 3139.54   325.6  3144.8   336.6 3145.42
   356.2  3145.1   368.6 3142.41   390.7    3142   414.5 3144.16     430  3144.4
     446 3142.23   464.5 3142.75   479.2 3140.12   513.7 3142.91   533.4 3143.17
   554.9 3153.22   580.7 3161.74     592 3164.32   597.9 3167.47   626.1 3177.78
#Mann= 5 ,-1,0
       0      .1       0   291.2    .045       0   314.1      .1       0
     390     .06       0     450      .1       0
#XS Ineff= 2 , 0
          250.03 3147.78   343.1         3148.78
Permanent Ineff=
       F       F
Bank Sta=291.2,314.1
XS Rating Curve= 0 ,0
Exp/Cntr(USF)=0,0
Exp/Cntr=0.3,0.1

Type RM Length L Ch R = 1 ,20933   ,199.4,199,198.6
XS GIS Cut Line= 3
2334836.25822946552728.5738449032334867.54144185 552817.26478547
2335172.77535988553251.672932128
#Sta/Elev= 30
       0 3159.16    21.8  3154.2    51.5 3150.54   108.6 3140.43   133.1 3139.63
   157.5 3140.51   166.2 3139.42   172.2 3136.95   180.6 3136.34   249.5 3138.72
   301.2 3136.67   331.7 3140.05   335.6 3139.06   341.4 3135.44   345.6 3133.65
   352.6 3133.31  360.473135.414   367.7 3139.16   378.7 3140.37   436.2 3139.03
   455.7 3137.23   489.9 3139.73   514.4 3138.67   530.9 3135.69   538.8  3135.8
   556.7 3138.15   567.9 3143.13   577.9 3150.89   585.4    3155     625 3172.09
#Mann= 6 ,-1,0
       0      .1       0   341.4    .045       0  360.47      .1       0
  404.05     .07       0  484.05     .06       0  524.05      .1       0
#XS Ineff= 2 , 0
          253.58 3143.94  382.54         3144.45
Permanent Ineff=
       F       F
Bank Sta=341.4,360.47
XS Rating Curve= 0 ,0
Exp/Cntr=0.3,0.1

Type RM Length L Ch R = 1 ,20734   ,256.5,255.2,246.3
XS GIS Cut Line= 3
2334667.56059901552773.2498631222334762.28836667553019.159320591
2334992.88828593553333.004853859
#Sta/Elev= 30
       0 3152.84    25.6 3151.04    46.2 3148.51    59.9 3147.91    77.1 3144.67
   111.4 3143.89   124.2 3144.28     150 3141.58   248.5 3138.68   263.5 3137.64
   280.2 3135.41   325.6 3133.29   360.3  3133.4   395.1 3136.25     400 3135.03
   406.5 3132.09   415.1  3130.5   419.9 3130.48   429.4 3132.08     438 3135.75
   444.7 3136.28   469.4 3135.64   494.4 3132.26   516.7 3135.19   553.9 3134.02
     561 3134.41   577.5 3139.65   589.6 3145.32   603.6 3149.19     653 3169.59
#Mann= 5 ,-1,0
       0      .1       0   406.5    .045       0   429.4      .1       0
  443.52     .06       0  573.52      .1       0
#XS Ineff= 2 , 0
                          452.73          3140.1
Permanent Ineff=
       F       F
Bank Sta=406.5,429.4
XS Rating Curve= 0 ,0
Exp/Cntr(USF)=0,0
Exp/Cntr=0.3,0.1

Type RM Length L Ch R = 1 ,20479   ,255.1,257.5,256.5
XS GIS Cut Line= 3
2334516.09136424552957.6278457042334583.52031158553184.716139638
2334828.43464907553422.655068778
#Sta/Elev= 30
       0 3141.69   174.8 3135.77     204 3133.39   220.7 3133.56     229 3132.46
   266.3 3132.46   274.5 3131.36  284.993128.131   289.2 3126.73   299.1  3126.1
   314.1 3128.14   322.5 3132.78     327 3133.87   338.2 3130.72   353.7 3132.15
   367.8 3131.37   382.8 3131.93   421.5 3130.65   438.5 3129.56   449.7 3128.16
   461.1    3130   495.1  3130.6   511.1 3130.03   518.8 3130.55   524.6 3132.13
   530.3 3135.11   543.2 3143.76   553.3 3151.86   557.3 3154.36   578.4 3163.29
#Mann= 5 ,-1,0
       0      .1       0  284.99    .045       0   314.1      .1       0
  346.89     .06       0  496.89      .1       0
#XS Ineff= 2 , 0
                          382.65          3135.2
Permanent Ineff=
       F       F
Bank Sta=284.99,314.1
XS Rating Curve= 0 ,0
Exp/Cntr(USF)=0,0
Exp/Cntr=0.3,0.1

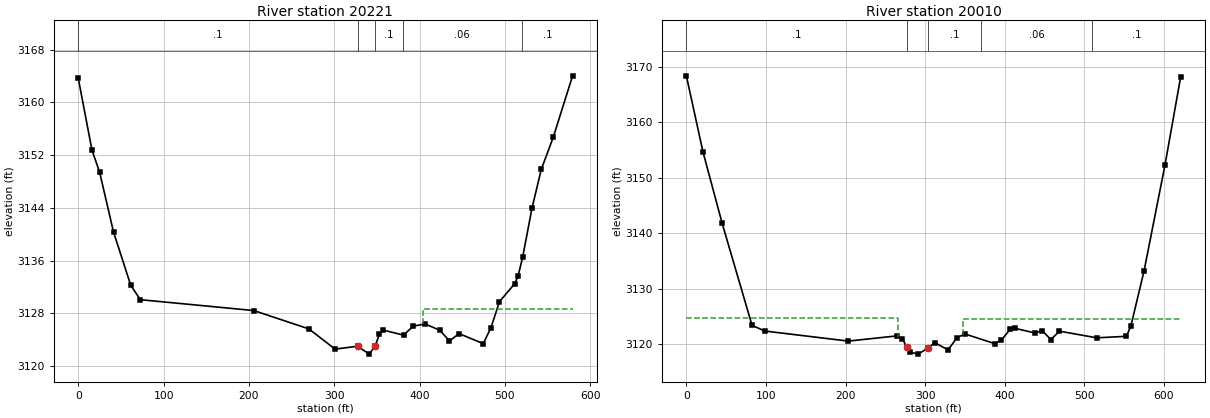
Type RM Length L Ch R = 1 ,20221   ,211.2,211.1,206.4
XS GIS Cut Line= 2
2334243.80083184553166.849223401 2334637.1709108553592.114173628
#Sta/Elev= 30
       0 3163.67    16.1 3152.75      25 3149.44    41.3 3140.36    61.4  3132.3
    72.7 3130.08   205.7 3128.43   270.2 3125.65     301 3122.58   327.4 3123.02
     341 3121.82   348.1 3123.07   352.9 3124.87   357.3 3125.47   381.2  3124.7
   392.5 3126.06   406.4  3126.4   423.7 3125.44     435 3123.82   446.3 3124.93
   474.6 3123.41   483.6 3125.82   493.6 3129.78   511.4  3132.5   515.4 3133.67
   520.8 3136.54   531.7 3143.96   542.6 3149.84   556.7 3154.75   579.3 3164.04
#Mann= 5 ,-1,0
       0      .1       0   327.4    .045       0   348.1      .1       0
     380     .06       0     520      .1       0
#XS Ineff= 2 , 0
                          404.42         3128.68
Permanent Ineff=
       F       F
Bank Sta=327.4,348.1
XS Rating Curve= 0 ,0
Exp/Cntr(USF)=0,0
Exp/Cntr=0.3,0.1

Type RM Length L Ch R = 1 ,20010   ,203.3,202,199.7
XS GIS Cut Line= 2
2334081.25406813553300.3942375572334525.03733555553734.994602966
#Sta/Elev= 30
       0 3168.39    20.9 3154.66      45 3141.78    82.5 3123.41    98.3 3122.38
   203.4 3120.56   264.1 3121.49   271.3 3121.02     277 3119.42   281.3 3118.56
   291.1 3118.21   304.1 3119.34     312  3120.3   328.8 3118.96     340 3121.17
   349.9 3121.85   387.3 3120.11   395.8 3120.72     407 3122.74   412.7 3122.87
   438.2 3122.02     447 3122.45     458 3120.84   468.8 3122.35   515.6 3121.15
   552.8 3121.42   558.4 3123.22   575.1 3133.24   601.4 3152.34   621.1 3168.23
#Mann= 5 ,-1,0
       0      .1       0     277    .045       0   304.1      .1       0
     370     .06       0     510      .1       0
#XS Ineff= 2 , 0
           266.2 3124.77  347.04         3124.55
Permanent Ineff=
       F       F
Bank Sta=277,304.1
XS Rating Curve= 0 ,0
Exp/Cntr=0.3,0.1