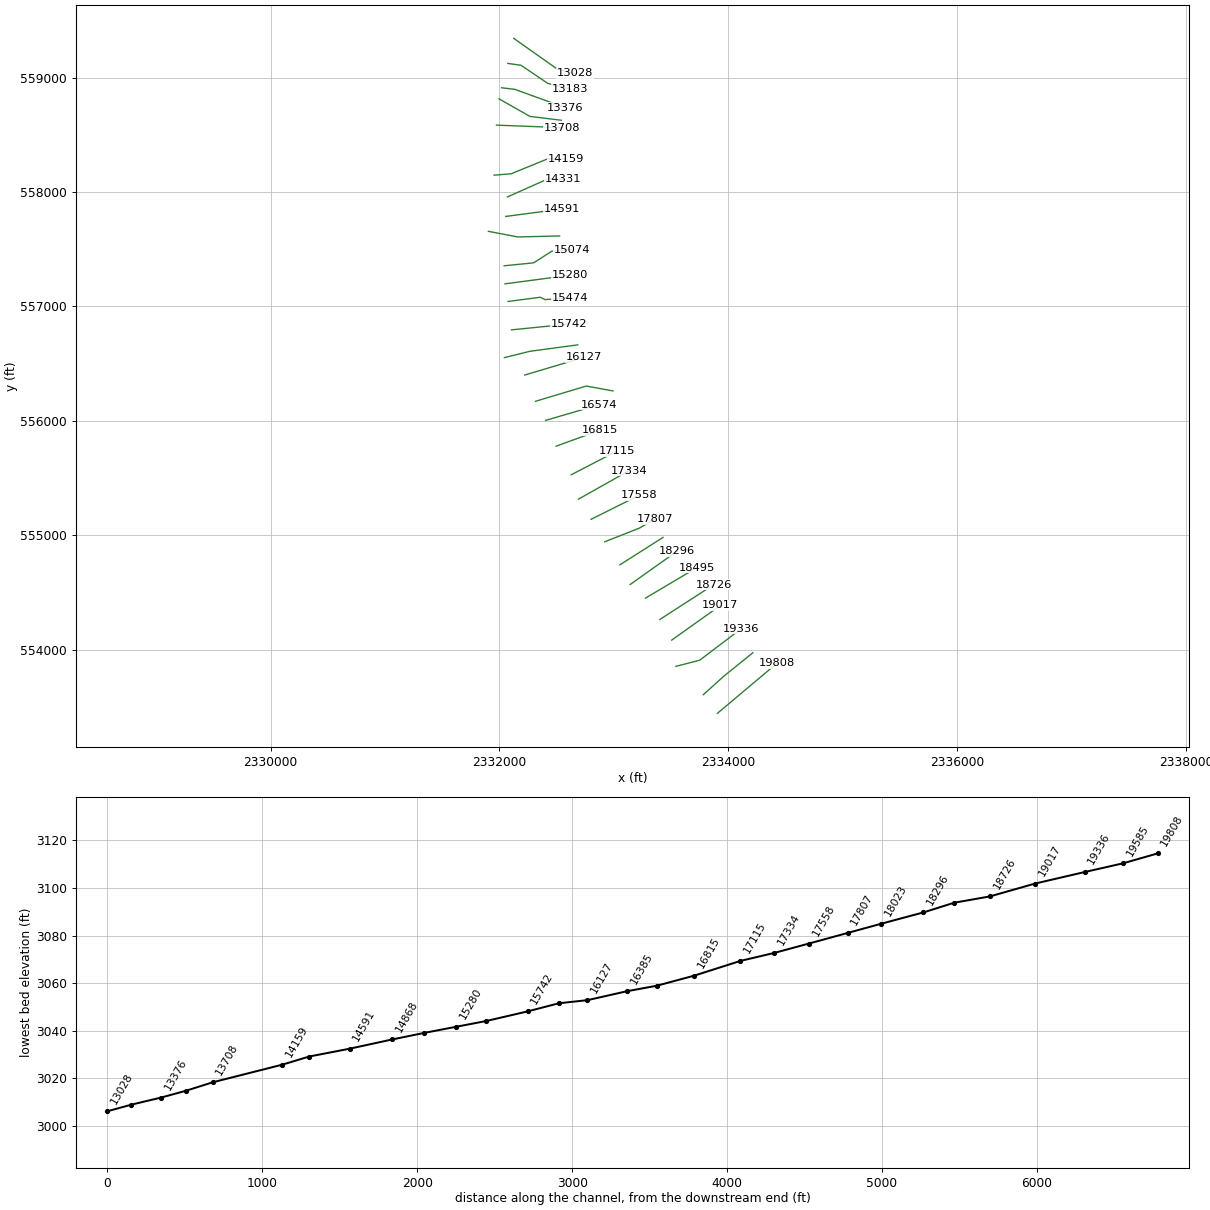
HEC-RAS study LTTLRV2.prj: LTTLRV2

--- LTTLRV2.g01 (geometry) --- (continued)

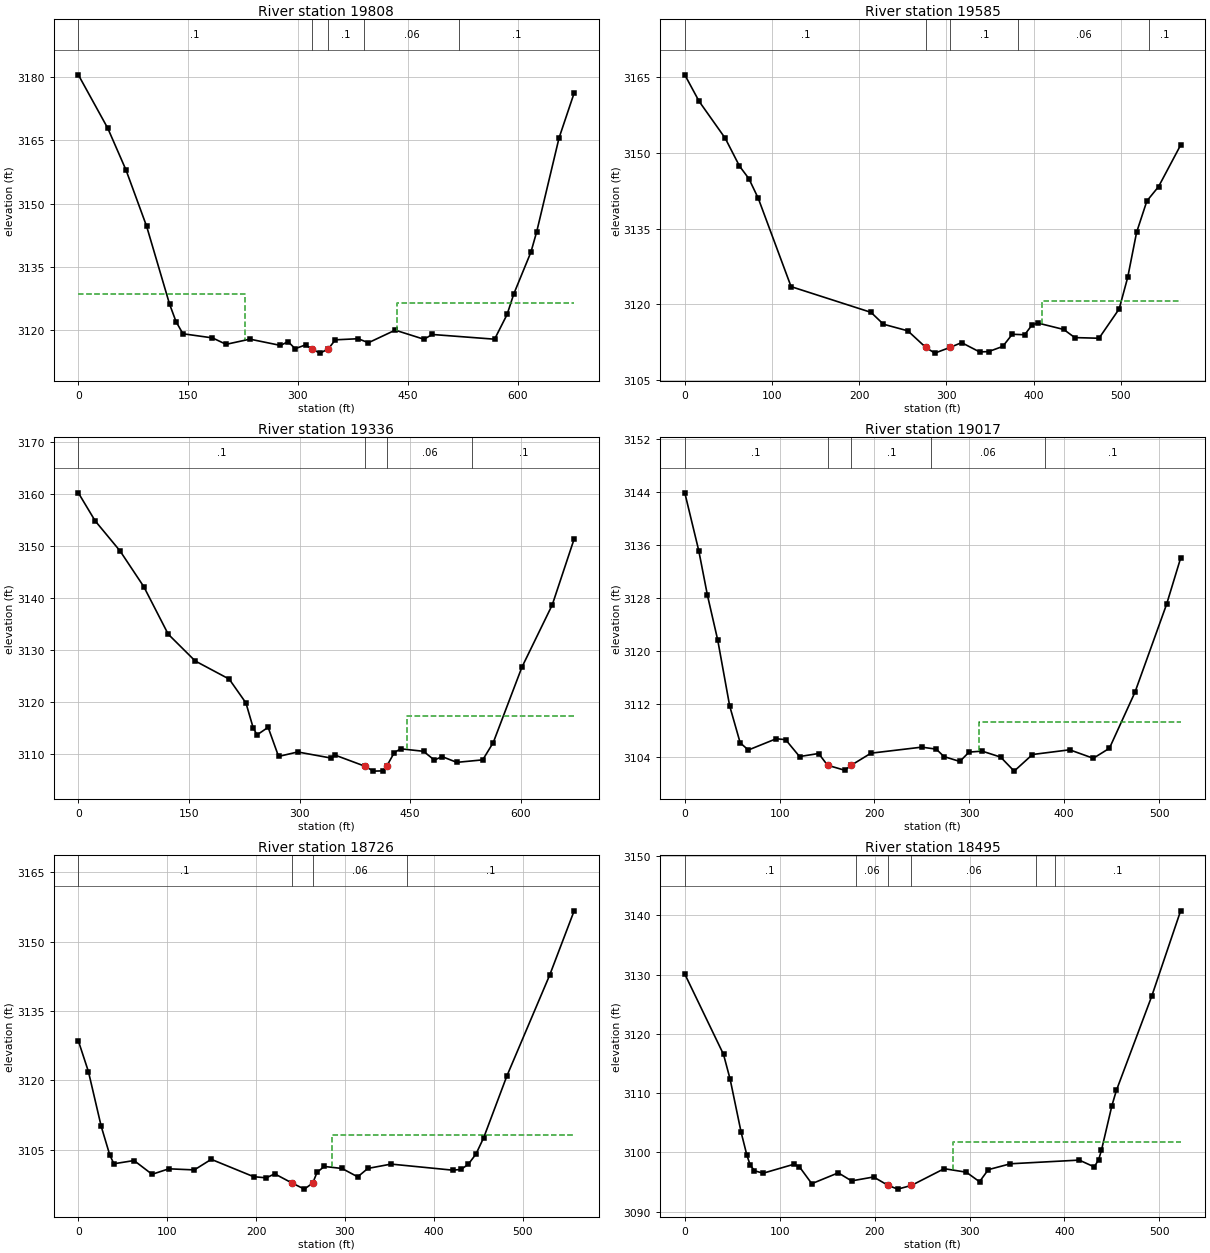
Type RM Length L Ch R = 1 ,19808   ,221.4,223.6,218.6
XS GIS Cut Line= 2
2333904.77016319553443.2714410492334423.35714416553879.168015032
#Sta/Elev= 30
       0 3180.58    40.3 3167.86    65.1 3157.98    93.3  3144.6   124.6 3126.13
   133.5 3121.94   142.9 3119.07   183.2 3118.09   201.9 3116.56   234.4 3117.79
   276.2  3116.3   286.6  3117.2   296.2 3115.52   310.4 3116.43   318.9 3115.42
   330.3 3114.47   341.6 3115.49   351.1 3117.63   382.2 3117.89   396.3 3116.94
   432.9 3119.93   472.2 3117.77   483.6  3118.9   568.7 3117.78   585.8 3123.66
   594.9 3128.53   618.4  3138.5   626.3 3143.36   656.7 3165.55   677.4 3176.27
#Mann= 5 ,-1,0
       0      .1       0   318.9    .045       0   341.6      .1       0
     390     .06       0     520      .1       0
#XS Ineff= 2 , 0
          227.96 3128.42  435.77         3126.28
Permanent Ineff=
       F       F
Bank Sta=318.9,341.6
XS Rating Curve= 0 ,0
Exp/Cntr(USF)=0,0
Exp/Cntr=0.3,0.1

Type RM Length L Ch R = 1 ,19585   ,245.8,248.4,244.4
XS GIS Cut Line= 3
2333781.51420511553606.1833557322333961.88696985553768.332766583
2334215.38746297553973.554625702
#Sta/Elev= 30
       0 3165.47    16.4 3160.22    46.4 3152.89    62.7 3147.39    73.5 3144.89
    84.3 3140.98   121.9 3123.49   213.6 3118.39   227.8 3116.04   255.8 3114.73
   276.4 3111.44   286.7 3110.31   304.5 3111.46   317.5 3112.39   338.1 3110.55
   348.4 3110.61   364.7 3111.64   375.6 3114.05   389.8 3113.95   398.3  3115.9
     405 3116.27   434.6    3115   447.3 3113.39   475.1 3113.26   498.2 3119.07
     508 3125.32   518.2 3134.25     530 3140.47   543.4 3143.31   568.7 3151.54
#Mann= 5 ,-1,0
       0      .1       0   276.4    .045       0   304.5      .1       0
  382.54     .06       0  532.54      .1       0
#XS Ineff= 2 , 0
                          409.35         3120.55
Permanent Ineff=
       F       F
Bank Sta=276.4,304.5
XS Rating Curve= 0 ,0
Exp/Cntr(USF)=0,0
Exp/Cntr=0.3,0.1

Type RM Length L Ch R = 1 ,19336   ,317.7,319.6,318.9
XS GIS Cut Line= 3
2333542.11366396553854.3608929352333750.02097296553907.519011714
2334115.04005524554183.941229362
#Sta/Elev= 30
       0 3160.25    22.8 3154.85    56.6 3149.05    88.8 3142.17   121.9 3133.02
   158.5 3127.86   204.6 3124.37   227.3 3119.78   237.2 3114.96   242.4 3113.62
   257.4 3115.08   271.6 3109.47   297.6 3110.33   342.7 3109.16   348.7  3109.7
   388.6 3107.59   400.1 3106.64     413 3106.69  418.17 3107.58   428.6 3110.21
   437.2 3110.94   468.2 3110.46   482.9 3108.76   493.3 3109.44   513.3 3108.33
   548.5 3108.81   562.8 3112.15   601.6 3126.65   642.8 3138.67   672.5 3151.37
#Mann= 4 ,-1,0
       0      .1       0   388.6    .045       0  418.17     .06       0
   534.6      .1       0
#XS Ineff= 2 , 0
                          445.63         3117.24
Permanent Ineff=
       F       F
Bank Sta=388.6,418.17
XS Rating Curve= 0 ,0
Exp/Cntr(USF)=0,0
Exp/Cntr=0.3,0.1

Type RM Length L Ch R = 1 ,19017   ,288,291.1,288.1
XS GIS Cut Line= 2
2333505.62306109554083.2948795892333931.41959251 554386.61510534
#Sta/Elev= 30
       0 3143.83    14.7 3135.11    23.9 3128.34    34.7 3121.61    47.3 3111.66
    58.4 3106.08      67    3105    96.4  3106.7   106.3 3106.56     121 3104.01
   141.1 3104.47   150.5  3102.7   168.7 3101.94   175.6 3102.71   196.3 3104.52
   249.8 3105.43   265.2 3105.13   273.2 3104.01     290 3103.27   299.7 3104.68
   313.5 3104.83     333 3103.93   347.3 3101.81   366.6 3104.32   405.8 3105.03
   430.7 3103.75   447.7 3105.26   474.6  3113.7     508    3127   522.8 3133.97
#Mann= 5 ,-1,0
       0      .1       0   150.5    .045       0   175.6      .1       0
     260     .06       0     380      .1       0
#XS Ineff= 2 , 0
                          310.31          3109.3
Permanent Ineff=
       F       F
Bank Sta=150.5,175.6
XS Rating Curve= 0 ,0
Exp/Cntr(USF)=0,0
Exp/Cntr=0.3,0.1

Type RM Length L Ch R = 1 ,18726   ,229.3,230.3,228.6
XS GIS Cut Line= 2
2333402.57163335554264.0275448042333871.15060629554566.963194534
#Sta/Elev= 30
       0 3128.54    11.4 3121.84    25.7 3110.05    35.3 3103.86      40 3101.91
    62.7 3102.61      83 3099.63   101.9 3100.82   130.5 3100.58   149.6 3102.87
   197.2 3099.12   211.5 3098.86     221 3099.73   240.1 3097.78   254.4 3096.42
   263.9 3097.76   268.6 3100.05   276.8 3101.33   296.8 3100.89   314.4 3099.08
   325.8  3100.9     352 3101.84   421.1 3100.53   430.6 3100.67   438.8 3101.79
   447.5 3104.01   456.2 3107.56   482.2 3120.88   530.6 3142.83     558 3156.68
#Mann= 4 ,-1,0
       0      .1       0   240.1    .045       0   263.9     .06       0
     370      .1       0
#XS Ineff= 2 , 0
                           285.3          3108.2
Permanent Ineff=
       F       F
Bank Sta=240.1,263.9
XS Rating Curve= 0 ,0
Exp/Cntr(USF)=0,0
Exp/Cntr=0.3,0.1

Type RM Length L Ch R = 1 ,18495   ,197.8,199.4,198.5
XS GIS Cut Line= 2
2333277.08777692554450.7762984332333726.39520873554717.205862298
#Sta/Elev= 30
       0 3130.09    40.8 3116.52    47.8  3112.3    59.4 3103.34    65.3 3099.58
    68.7 3097.92    73.3 3096.88    82.6 3096.47   115.2 3097.99   120.8 3097.54
   133.8  3094.7   161.7 3096.53   175.7 3095.17   198.9 3095.83   214.2 3094.41
   224.3 3093.78   238.7  3094.4   273.3 3097.23   296.6 3096.64   310.5 3095.03
   319.8 3097.07   343.1 3098.06   415.6 3098.68   431.4 3097.53   436.1 3098.78
     439 3100.35     450 3107.88   454.7 3110.43   491.9 3126.32   522.4 3140.76
#Mann= 6 ,-1,0
       0      .1       0     180     .06       0   214.2    .045       0
   238.7     .06       0     370     .03       0     390      .1       0
#XS Ineff= 2 , 0
                          282.59         3101.68
Permanent Ineff=
       F       F
Bank Sta=214.2,238.7
XS Rating Curve= 0 ,0
Exp/Cntr=0.3,0.1

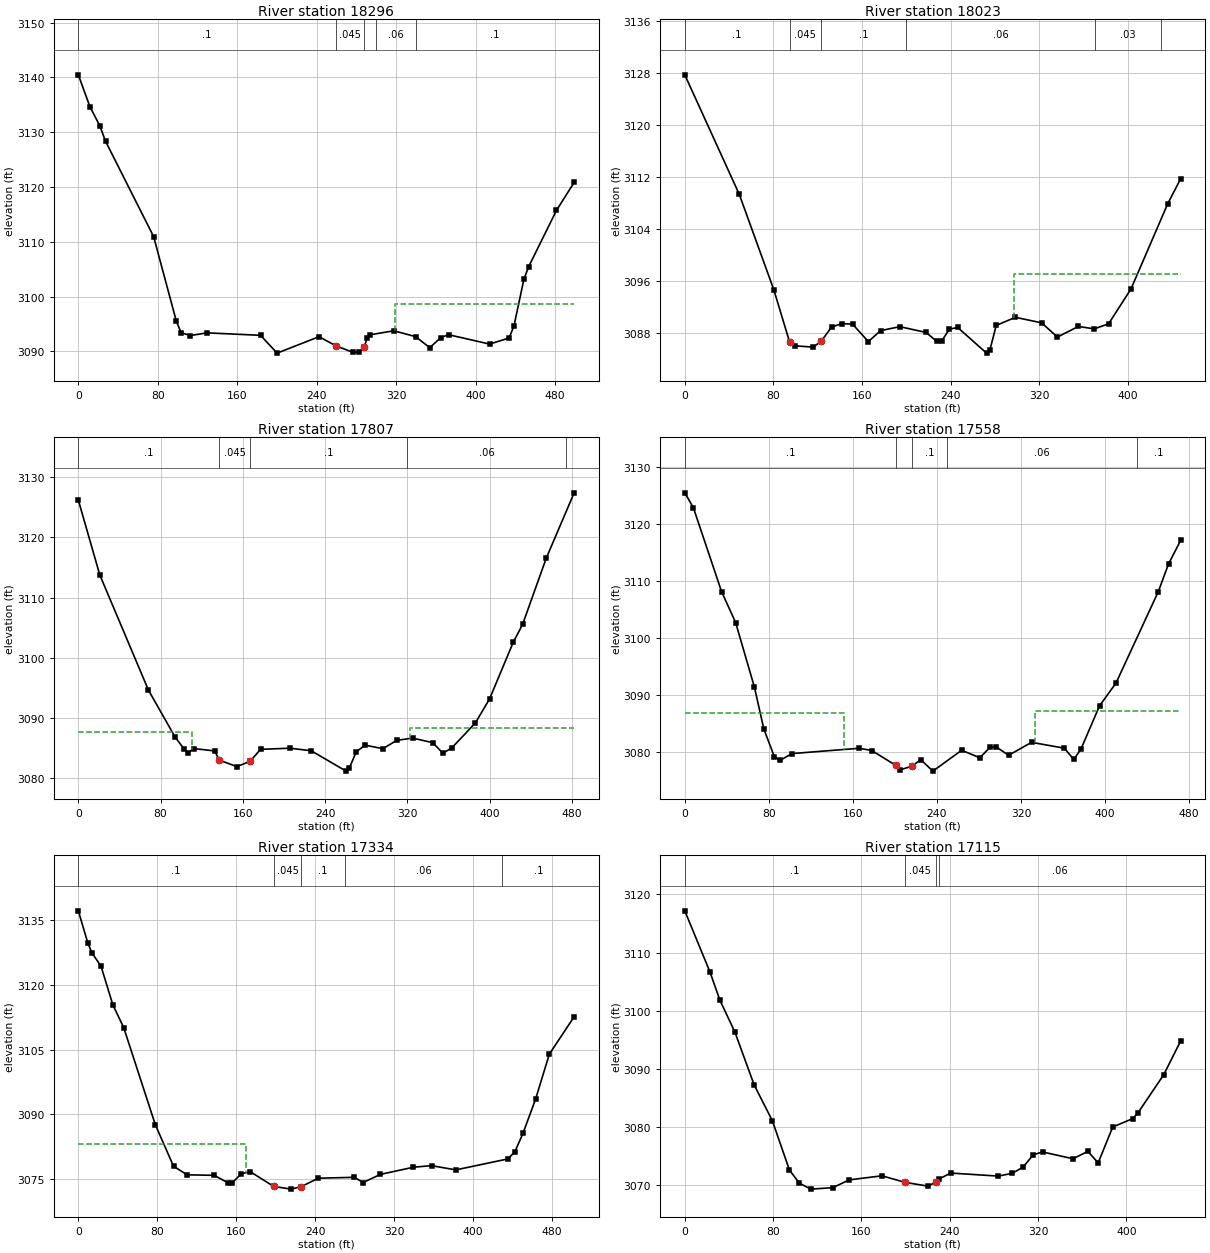
Type RM Length L Ch R = 1 ,18296   ,269.8,273.6,267.7
XS GIS Cut Line= 2
2333142.67886488554569.2901191722333549.57768507 554858.38204285
#Sta/Elev= 30
       0 3140.48    11.6 3134.69    21.5 3131.22    27.4 3128.36    75.8 3110.96
    98.5 3095.63   103.4 3093.42   112.9 3092.91   129.4  3093.4   183.4 3092.95
   200.1  3089.7   242.3  3092.7   259.2 3091.04   276.1 3089.87     283  3089.9
   287.9  3090.9   290.7 3092.43   293.6 3093.04   317.5 3093.78   339.5 3092.71
   353.8 3090.69   364.9 3092.55   372.7 3093.06     414 3091.35   433.6 3092.46
   438.5 3094.65   448.5 3103.17   453.3 3105.47   481.3 3115.75   499.1 3120.85
#Mann= 5 ,-1,0
       0      .1       0   259.2    .045       0   287.9      .1       0
     300     .06       0     340      .1       0
#XS Ineff= 2 , 0
                          319.15         3098.64
Permanent Ineff=
       F       F
Bank Sta=259.2,287.9
XS Rating Curve= 0 ,0
Exp/Cntr(USF)=0,0
Exp/Cntr=0.3,0.1

Type RM Length L Ch R = 1 ,18023   ,220.2,215.6,210.8
XS GIS Cut Line= 2
2333052.38473496554741.1216100172333430.00574441554981.049923652
#Sta/Elev= 30
       0 3127.75    49.2 3109.34    80.3 3094.69    94.5 3086.68    99.3 3086.05
   115.8 3085.86     123 3086.73   132.4 3088.94   141.8 3089.47   151.4 3089.39
   165.6 3086.71   176.7 3088.39     194    3089   217.8 3088.11   227.2 3086.75
   231.7 3086.78   238.8 3088.62   246.2 3088.88   272.3 3084.93   275.2 3085.35
     281 3089.19   298.3 3090.44     322 3089.59   336.2  3087.4   355.2 3089.04
   369.4 3088.66   382.4 3089.44   402.6  3094.8   435.7 3107.89   447.4 3111.75
#Mann= 6 ,-1,0
       0      .1       0    94.5    .045       0     123      .1       0
     200     .06       0     370     .03       0     430      .1       0
#XS Ineff= 2 , 0
                          297.34         3097.07
Permanent Ineff=
       F       F
Bank Sta=94.5,123
XS Rating Curve= 0 ,0
Exp/Cntr=0.3,0.1

Type RM Length L Ch R = 1 ,17807   ,247.5,249.2,250.5
XS GIS Cut Line= 3
2332920.69253716554942.8311943532333222.63065183555061.905380418
2333359.77859828555139.516233835
#Sta/Elev= 30
       0 3126.22    20.9 3113.75    68.2 3094.57      94 3086.78   102.6 3084.82
   106.9 3084.16   112.4 3084.84   132.7 3084.44     137 3082.92   154.2 3081.83
   167.1 3082.72   177.2 3084.71   205.8  3084.9   226.5 3084.47   260.4 3081.08
   263.5 3081.57   270.3  3084.3   278.9 3085.41   296.1 3084.82   309.8 3086.21
   325.2 3086.58   344.7 3085.82   354.5 3084.07   363.1 3084.93   386.1  3089.1
   399.9  3093.1   422.9 3102.52   432.1 3105.54     455 3116.53   482.2 3127.44
#Mann= 5 ,-1,0
       0      .1       0     137    .045       0   167.1      .1       0
     320     .06       0  474.57      .1       0
#XS Ineff= 2 , 0
          110.42  3087.6  322.25         3088.23
Permanent Ineff=
       F       F
Bank Sta=137,167.1
XS Rating Curve= 0 ,0
Exp/Cntr(USF)=0,0
Exp/Cntr=0.3,0.1

Type RM Length L Ch R = 1 ,17558   ,223.3,223.4,223.7
XS GIS Cut Line= 2
2332800.84069688555139.1723920372333223.24559217555349.622241672
#Sta/Elev= 30
       0 3125.48     8.2 3122.85      35 3108.14    48.4 3102.71    66.3 3091.35
    75.2 3084.04    85.2 3079.19    90.5 3078.51     102 3079.72     166 3080.65
     178 3080.26   200.9 3077.63   204.8 3076.85   215.8  3077.5   224.7 3078.63
   236.1 3076.64   263.5  3080.3   280.8 3078.98   290.3 3080.79   296.3  3080.9
   308.2 3079.42     330 3081.69   361.2 3080.67   370.2 3078.69     377 3080.49
   394.7 3088.09   410.4  3092.1   450.6 3108.12   460.4    3113   471.9 3117.12
#Mann= 5 ,-1,0
       0      .1       0   200.9    .045       0   215.8      .1       0
     250     .06       0     430      .1       0
#XS Ineff= 2 , 0
          151.16 3086.83  333.52         3087.11
Permanent Ineff=
       F       F
Bank Sta=200.9,215.8
XS Rating Curve= 0 ,0
Exp/Cntr=0.3,0.1

Type RM Length L Ch R = 1 ,17334   ,219.5,219.2,218
XS GIS Cut Line= 2
2332692.11262641555316.0011881812333130.13552515555562.654859316
#Sta/Elev= 30
       0 3137.07     9.7 3129.57    13.8 3127.35      23 3124.26      35 3115.33
      46 3110.07    78.1 3087.58    96.5 3078.02   110.2 3076.02   137.8  3075.9
   151.6 3074.17   156.2 3074.22   165.3 3076.28   174.5 3076.72   198.1 3073.33
   215.8 3072.71  226.15 3073.31   243.4 3075.24   279.9 3075.44   288.7 3074.24
   306.3 3076.12   339.8 3077.78   358.1 3078.14   382.7 3077.16   435.6  3079.7
   442.6 3081.37   450.8  3085.6   463.7  3093.6   477.5 3103.91   502.7 3112.59
#Mann= 5 ,-1,0
       0      .1       0   198.1    .045       0  226.15      .1       0
     270     .06       0     430      .1       0
#XS Ineff= 2 , 0
          170.43 3083.15
Permanent Ineff=
       F       F
Bank Sta=198.1,226.15
XS Rating Curve= 0 ,0
Exp/Cntr(USF)=0,0
Exp/Cntr=0.3,0.1

Type RM Length L Ch R = 1 ,17115   ,300.3,299.9,295.2
XS GIS Cut Line= 2
2332627.97369688555528.7001860652333026.79748918555735.266362509
#Sta/Elev= 30
       0 3117.17    22.8 3106.66    31.8 3101.81    45.3 3096.37    62.8 3087.27
    79.3  3081.1    94.8 3072.62   103.8 3070.37   114.1 3069.35     134  3069.6
   148.9 3070.94   178.6 3071.64   199.3 3070.52   220.1 3069.87   227.2 3070.53
     230 3071.07   240.9 3072.11     284 3071.59   296.8 3072.08   306.5 3073.15
   315.6 3075.25     324 3075.74   351.6 3074.57   365.1 3075.84   374.4 3073.86
   387.6 3080.02   405.6 3081.46   410.2 3082.38   433.8 3089.01   449.1  3094.8
#Mann= 4 ,-1,0
       0      .1       0   199.3    .045       0   227.2      .1       0
     230     .06       0
Bank Sta=199.3,227.2
XS Rating Curve= 0 ,0
Exp/Cntr=0.3,0.1

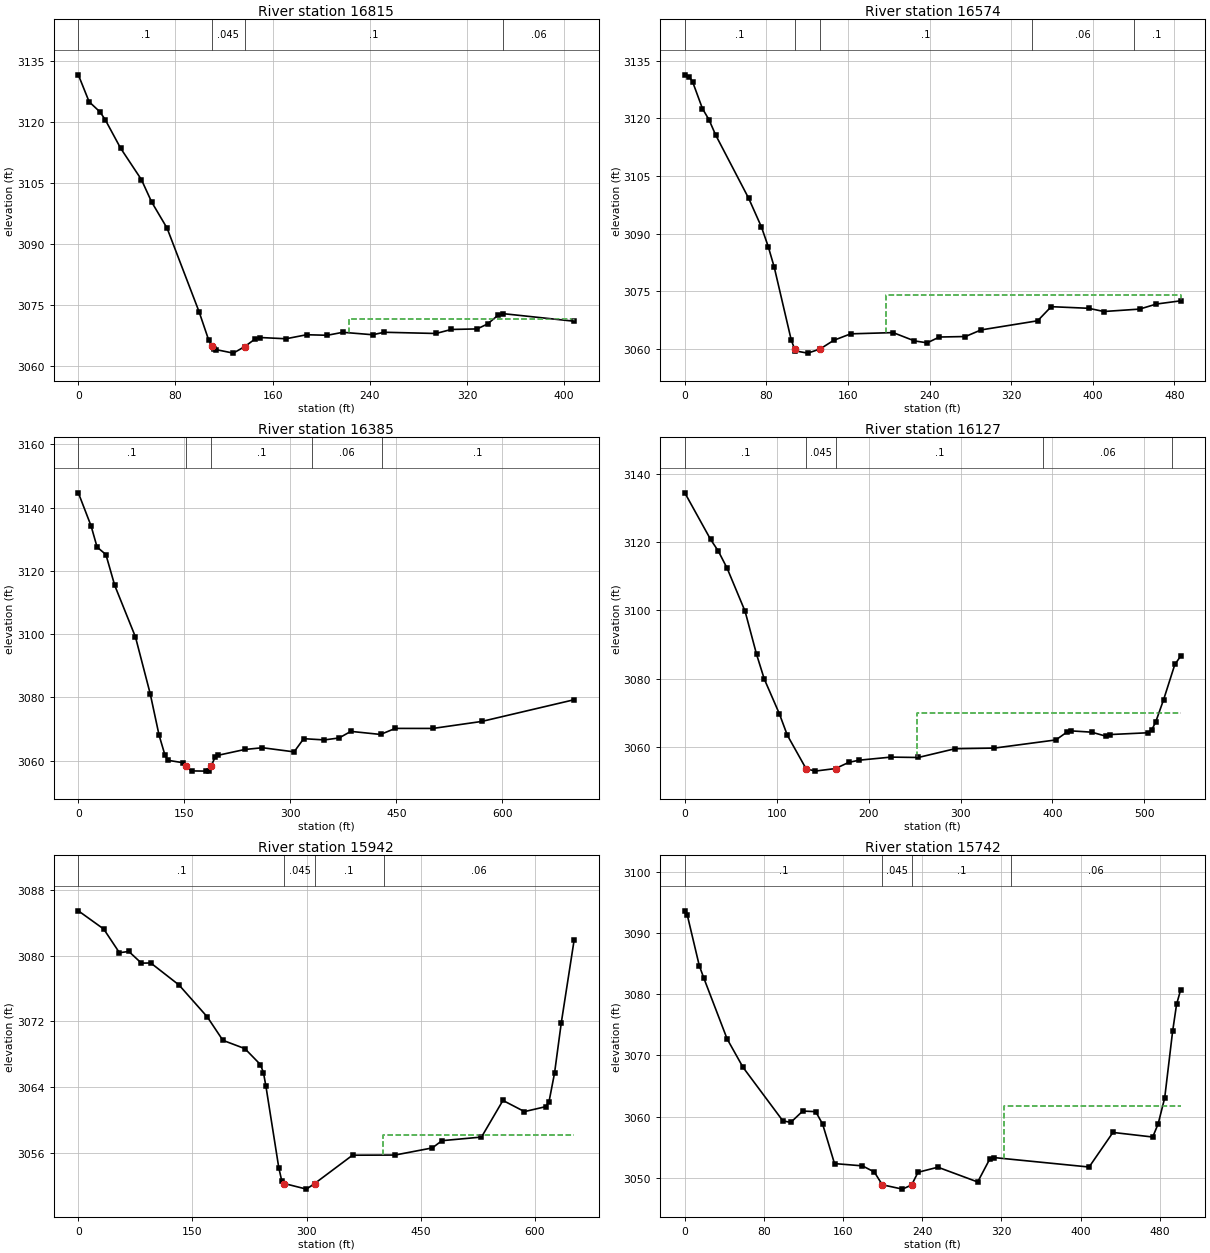
Type RM Length L Ch R = 1 ,16815   ,240.6,241.3,237.9
XS GIS Cut Line= 2
2332495.42758693555778.4768215592332879.22920452555917.751092759
#Sta/Elev= 30
       0 3131.55     8.9 3124.92    17.8 3122.44    22.1 3120.54    34.8 3113.52
    51.9 3105.81    60.4 3100.27    73.1 3093.84    99.5 3073.25   107.2 3066.46
   110.3 3064.81   111.4 3064.21   113.5 3063.99   127.6 3063.13   136.9 3064.71
   145.5 3066.59   149.7 3066.97     171 3066.66     188 3067.65     205 3067.52
   217.8 3068.25   242.4 3067.65   251.9 3068.26   294.4 3067.96   307.2 3068.95
   328.4 3069.08     337  3070.3   345.5 3072.42   349.7 3072.84   408.3 3070.97
#Mann= 4 ,-1,0
       0      .1       0   110.3    .045       0   136.9      .1       0
     350     .06       0
#XS Ineff= 2 , 0
                          223.21         3071.42
Permanent Ineff=
       F       F
Bank Sta=110.3,136.9
XS Rating Curve= 0 ,0
Exp/Cntr(USF)=0,0
Exp/Cntr=0.3,0.1

Type RM Length L Ch R = 1 ,16574   ,187.9,189.4,189.1
XS GIS Cut Line= 2
2332403.99562263556003.8672451812332870.72390551556139.952029255
#Sta/Elev= 30
       0 3131.34     4.4 3130.82     7.7  3129.5    17.3 3122.55    23.8 3119.62
    30.2 3115.71    62.7 3099.17    75.2 3091.71    81.9 3086.57    87.7 3081.28
   104.4 3062.29   107.7 3059.99   108.5 3059.48   120.6 3058.91   132.7 3059.99
     146 3062.24   162.7 3063.93   204.3 3064.25   225.2 3062.09   237.7 3061.59
   249.6  3063.1   275.2 3063.23   290.5 3064.95     346 3067.33   359.3    3071
     396 3070.58   410.9 3069.74     446 3070.37   462.5 3071.69   486.2 3072.52
#Mann= 5 ,-1,0
       0      .1       0   107.7    .045       0   132.7      .1       0
     340     .06       0     440      .1       0
#XS Ineff= 2 , 0
                          197.75         3073.97
Permanent Ineff=
       F       F
Bank Sta=107.7,132.7
XS Rating Curve= 0 ,0
Exp/Cntr(USF)=0,0
Exp/Cntr=0.3,0.1

Type RM Length L Ch R = 1 ,16385   ,256.8,257.9,257.1
XS GIS Cut Line= 3
2332314.80275997556170.5416764862332759.13627162556303.771975898
2332992.81245122556261.221984986
#Sta/Elev= 30
       0 3144.66    18.1 3134.15    26.5 3127.51      39 3125.14    51.5 3115.37
    80.8 3099.08   101.7 3081.11   114.2 3068.04   122.5 3061.75   126.7 3060.08
   147.6 3059.32   151.8 3058.14   160.1 3056.72     181 3056.65   185.2 3056.84
  187.63 3058.16   193.5 3061.06   197.7 3061.66   235.3 3063.49   260.5 3064.05
   305.2 3062.74   318.8 3066.91     348 3066.52   368.9 3067.14   385.5 3069.22
   427.5 3068.25   448.3 3070.16   501.5 3070.15   570.6 3072.36   701.4 3079.23
#Mann= 5 ,-1,0
       0      .1       0   151.8    .045       0  187.63      .1       0
     330     .06       0     430      .1       0
Bank Sta=151.8,187.63
XS Rating Curve= 0 ,0
Exp/Cntr(USF)=0,0
Exp/Cntr=0.3,0.1

Type RM Length L Ch R = 1 ,16127   ,186.3,184.3,178
XS GIS Cut Line= 2
2332221.33228813556400.0326110752332738.21004659556554.189135526
#Sta/Elev= 30
       0 3134.46      28 3120.82    36.4  3117.4      46 3112.38    65.6 3099.71
    78.1 3087.08    86.4  3079.9   102.9 3069.66   111.5 3063.41   131.8 3053.63
   141.5 3052.86     164 3053.62   178.3 3055.42   189.7 3056.07   224.2 3056.97
     254 3056.86     294 3059.43   336.9 3059.62   403.7 3062.01   416.2  3064.4
   420.4 3064.66   442.7 3064.28   457.9 3063.12     463 3063.59   503.9 3064.11
     508 3064.96   512.2 3067.21   520.9 3073.82   533.1 3084.14   539.4 3086.55
#Mann= 5 ,-1,0
       0      .1       0   131.8    .045       0     164      .1       0
     390     .06       0     530      .1       0
#XS Ineff= 2 , 0
                          252.53         3070.02
Permanent Ineff=
       F       F
Bank Sta=131.8,164
XS Rating Curve= 0 ,0
Exp/Cntr(USF)=0,0
Exp/Cntr=0.3,0.1

Type RM Length L Ch R = 1 ,15942   ,202.5,200.8,199.9
XS GIS Cut Line= 3
2332043.71701447556552.3874083462332268.06752405556607.899779791
2332684.96257898556663.793306708
#Sta/Elev= 30
       0 3085.45    33.4 3083.23      54 3080.35    66.4  3080.5    82.9 3079.08
    95.2  3079.1   132.3 3076.42   169.5 3072.53     190 3069.68   218.9 3068.67
   239.3 3066.73   243.3 3065.76   246.6 3064.07   263.5 3054.15   267.5 3052.52
   270.8 3052.24   299.8 3051.56   310.6 3052.24   360.4 3055.69   416.2 3055.71
   465.3 3056.58   477.9 3057.46   529.9  3057.9   558.1 3062.36   586.4    3061
   614.6 3061.61   618.7 3062.23   625.9 3065.68   634.8 3071.83   651.7 3081.91
#Mann= 4 ,-1,0
       0      .1       0   270.8    .045       0   310.6      .1       0
  401.12     .06       0
#XS Ineff= 2 , 0
                          400.83         3058.17
Permanent Ineff=
       F       F
Bank Sta=270.8,310.6
XS Rating Curve= 0 ,0
Exp/Cntr=0.3,0.1

Type RM Length L Ch R = 1 ,15742   ,280.3,267.2,254.7
XS GIS Cut Line= 2
2332105.60079089556794.9354512372332604.21331342556844.882819641
#Sta/Elev= 30
       0 3093.61     2.6 3092.86    14.6 3084.68      19 3082.72    42.8 3072.68
    58.9 3068.04    99.1 3059.31   107.1 3059.06   119.2 3060.91   132.3 3060.81
   139.3 3058.78   151.3 3052.33   179.5 3051.96   191.5 3050.96   199.6 3048.87
     220 3048.16  229.23 3048.84   235.7 3050.91   255.8 3051.74     296 3049.33
   308.1 3053.04   312.1 3053.32   408.6 3051.77   432.7 3057.42   472.9 3056.67
   478.4 3058.83     485 3063.05     493 3073.92     497 3078.33   501.1  3080.7
#Mann= 4 ,-1,0
       0      .1       0   199.6    .045       0  229.23      .1       0
     330     .06       0
#XS Ineff= 2 , 0
                          322.48         3061.71
Permanent Ineff=
       F       F
Bank Sta=199.6,229.23
XS Rating Curve= 0 ,0
Exp/Cntr(USF)=0,0
Exp/Cntr=0.3,0.1

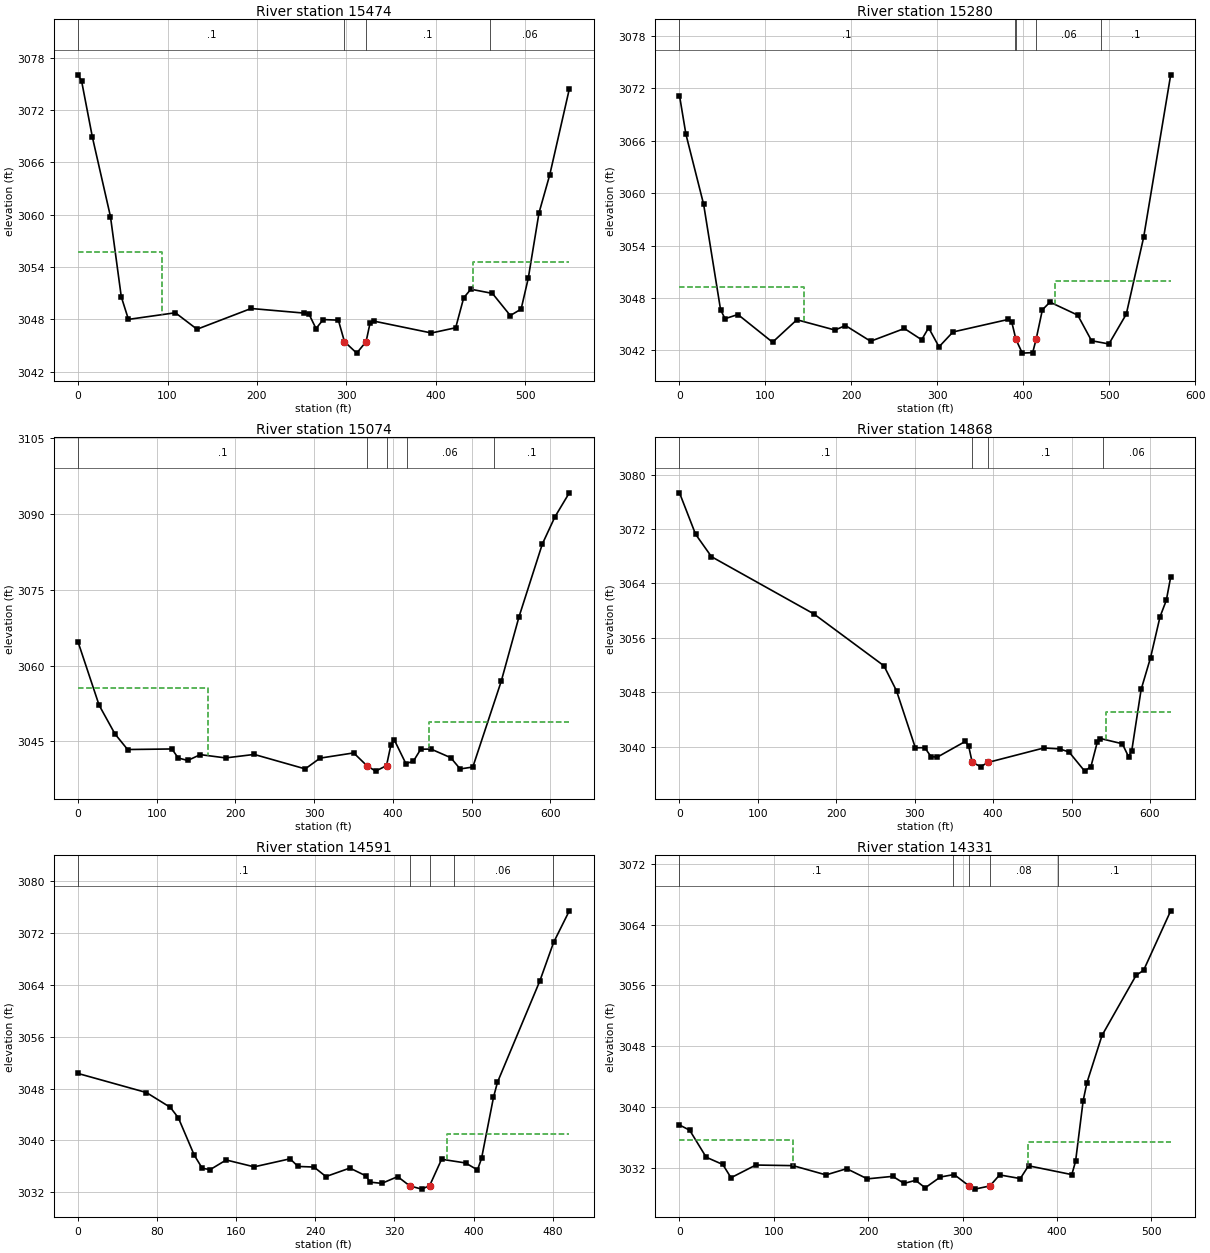
Type RM Length L Ch R = 1 ,15474   ,183.1,194.9,207.5
XS GIS Cut Line= 4
2332076.32129907557042.9499702122332357.05995597557079.979915753
2332400.11803218557059.3120391722332617.99189781557075.674108132
#Sta/Elev= 30
       0 3076.04     3.9 3075.33      16 3068.88    36.2 3059.78    48.3 3050.58
    56.3 3047.99   108.8 3048.75     133 3046.86   193.5 3049.24   252.9 3048.71
   258.1 3048.62   266.1 3046.94   274.2 3047.97   291.1  3047.9  297.89 3045.44
   311.6 3044.12   322.1 3045.43   326.6  3047.6   330.9 3047.79   395.2 3046.43
   422.3 3047.03   431.3 3050.47   439.3 3051.45   463.4 3050.97   483.4 3048.43
   495.5 3049.17   503.5 3052.71   515.5 3060.21   527.5 3064.56   549.4 3074.41
#Mann= 4 ,-1,0
       0      .1       0  297.89    .045       0   322.1      .1       0
  460.93     .06       0
#XS Ineff= 2 , 0
           94.01 3055.69  442.14         3054.62
Permanent Ineff=
       F       F
Bank Sta=297.89,322.1
XS Rating Curve= 0 ,0
Exp/Cntr(USF)=0,0
Exp/Cntr=0.3,0.1

Type RM Length L Ch R = 1 ,15280   ,195.5,205.3,214.7
XS GIS Cut Line= 2
 2332048.7641303557197.0978830472332615.40841323557272.018935654
#Sta/Elev= 30
       0 3071.18     7.5 3066.74    28.1 3058.72    47.8 3046.66      53 3045.63
      68 3046.11   108.3 3042.94   136.6 3045.51     181 3044.33   193.1 3044.85
   222.4 3043.05   261.7 3044.51   281.8 3043.22   289.9 3044.59     302 3042.41
   318.2 3044.11   382.7 3045.55   386.7 3045.23   391.5 3043.26   398.9 3041.69
     411 3041.75     415 3043.28   422.3 3046.65   431.1 3047.53   463.4 3046.04
   479.5 3043.11   499.7 3042.74   519.9 3046.15   540.1 3054.94   571.6 3073.55
#Mann= 5 ,-1,0
       0      .1       0     390     .06       0   391.5    .045       0
     415     .06       0     490      .1       0
#XS Ineff= 2 , 0
           144.7 3049.28  437.07         3049.89
Permanent Ineff=
       F       F
Bank Sta=391.5,415
XS Rating Curve= 0 ,0
Exp/Cntr(USF)=0,0
Exp/Cntr=0.3,0.1

Type RM Length L Ch R = 1 ,15074   ,217.7,206.4,196.5
XS GIS Cut Line= 4
2332041.60861339557354.9023611542332298.34947732557380.453379359
2332458.67701582557482.1423475642332634.40130315557497.022486424
#Sta/Elev= 30
       0 3064.63    26.7 3052.16    46.8 3046.49    62.9  3043.4   119.2 3043.51
   127.2 3041.73   139.3 3041.24   155.3 3042.39   187.5 3041.74   223.8 3042.43
   288.6 3039.57   307.5  3041.7   350.2 3042.73   367.1 3040.18   378.1 3039.13
  391.91 3040.22   397.5 3044.31   401.9 3045.27   416.5 3040.62     426 3041.08
   435.4 3043.46   448.4 3043.49   473.5 3041.79   485.5 3039.56   501.6 3039.94
   537.7  3056.9   560.2 3069.59   589.9 3084.01   605.9 3089.37   624.2 3094.13
#Mann= 5 ,-1,0
       0      .1       0   367.1    .045       0  391.91      .1       0
  418.01     .06       0  527.87      .1       0
#XS Ineff= 2 , 0
          164.52 3055.52  445.63         3048.91
Permanent Ineff=
       F       F
Bank Sta=367.1,391.91
XS Rating Curve= 0 ,0
Exp/Cntr=0.3,0.1

Type RM Length L Ch R = 1 ,14868   ,274.6,276.4,278.9
XS GIS Cut Line= 3
2331904.08899423557656.0969754562332159.85396692557607.010768575
2332525.84761471557615.622383818
#Sta/Elev= 30
       0 3077.34    20.5 3071.25    40.8 3067.94   171.2 3059.53   260.8 3051.88
   276.8  3048.2   300.8 3039.82   312.8 3039.83   320.8 3038.52   328.8 3038.44
   364.5 3040.75   368.8 3040.07   373.3 3037.69     384 3037.04   393.8 3037.67
   464.8 3039.79   484.8 3039.65   496.8  3039.2   516.8 3036.38   524.8 3037.06
   532.8 3040.62   536.8 3041.18   564.8 3040.41   572.8 3038.49   576.8 3039.36
   588.8  3048.4   600.8 3053.08   612.9  3059.1   620.9 3061.52   626.5 3064.95
#Mann= 4 ,-1,0
       0      .1       0   373.3    .045       0   393.8      .1       0
  540.43     .06       0
#XS Ineff= 2 , 0
                          544.23         3045.08
Permanent Ineff=
       F       F
Bank Sta=373.3,393.8
XS Rating Curve= 0 ,0
Exp/Cntr(USF)=0,0
Exp/Cntr=0.3,0.1

Type RM Length L Ch R = 1 ,14591   ,256.1,260.2,267.7
XS GIS Cut Line= 2
2332055.65342249557786.1323656132332548.23781434557851.580641454
#Sta/Elev= 30
       0 3050.33    69.1 3047.39    93.3  3045.1   101.4 3043.49   117.5 3037.72
   125.6 3035.69   133.7  3035.5   149.8 3036.98   178.1 3035.92   214.4 3037.16
   222.5 3035.98   238.6 3035.89   250.7 3034.42   274.9 3035.73   291.1 3034.53
   295.3 3033.56   307.2 3033.37   323.3 3034.41   335.4 3032.99   347.5 3032.48
   355.6 3033.01   367.7 3037.09   391.9 3036.52     404 3035.45   408.1 3037.21
   420.2 3046.65   424.2 3048.97   467.1 3064.62     481 3070.56   496.9 3075.44
#Mann= 5 ,-1,0
       0      .1       0   335.4    .045       0   355.6      .1       0
     380     .06       0     480      .1       0
#XS Ineff= 2 , 0
                          372.96         3041.06
Permanent Ineff=
       F       F
Bank Sta=335.4,355.6
XS Rating Curve= 0 ,0
Exp/Cntr(USF)=0,0
Exp/Cntr=0.3,0.1

Type RM Length L Ch R = 1 ,14331   ,174.9,172.5,175.4
XS GIS Cut Line= 3
 2332070.2931684557956.6423474082332427.67520095558115.957229389
2332556.84942959558110.790260244
#Sta/Elev= 30
       0 3037.65    10.8 3036.96    28.3 3033.41    45.9 3032.45    54.6 3030.71
    80.9 3032.38   120.3  3032.3   155.3 3031.08   177.2  3031.9   199.1 3030.56
     226 3030.89   238.1 3029.96   250.2 3030.37   260.4 3029.38   276.4  3030.8
   291.1 3031.13     3073029.622     313 3029.21     329 3029.63   339.3 3031.08
   361.2  3030.6   369.9 3032.28   415.8 3031.12   419.8 3032.88   427.8 3040.83
   431.8  3043.2   447.8 3049.43   483.9 3057.33   491.9    3058   520.6 3065.82
#Mann= 5 ,-1,0
       0      .1       0     290     .06       0     307    .045       0
     329     .08       0  401.28      .1       0
#XS Ineff= 2 , 0
             120 3035.63  369.46         3035.46
Permanent Ineff=
       F       F
Bank Sta=307,329
XS Rating Curve= 0 ,0
Exp/Cntr(USF)=0,0
Exp/Cntr=0.3,0.1

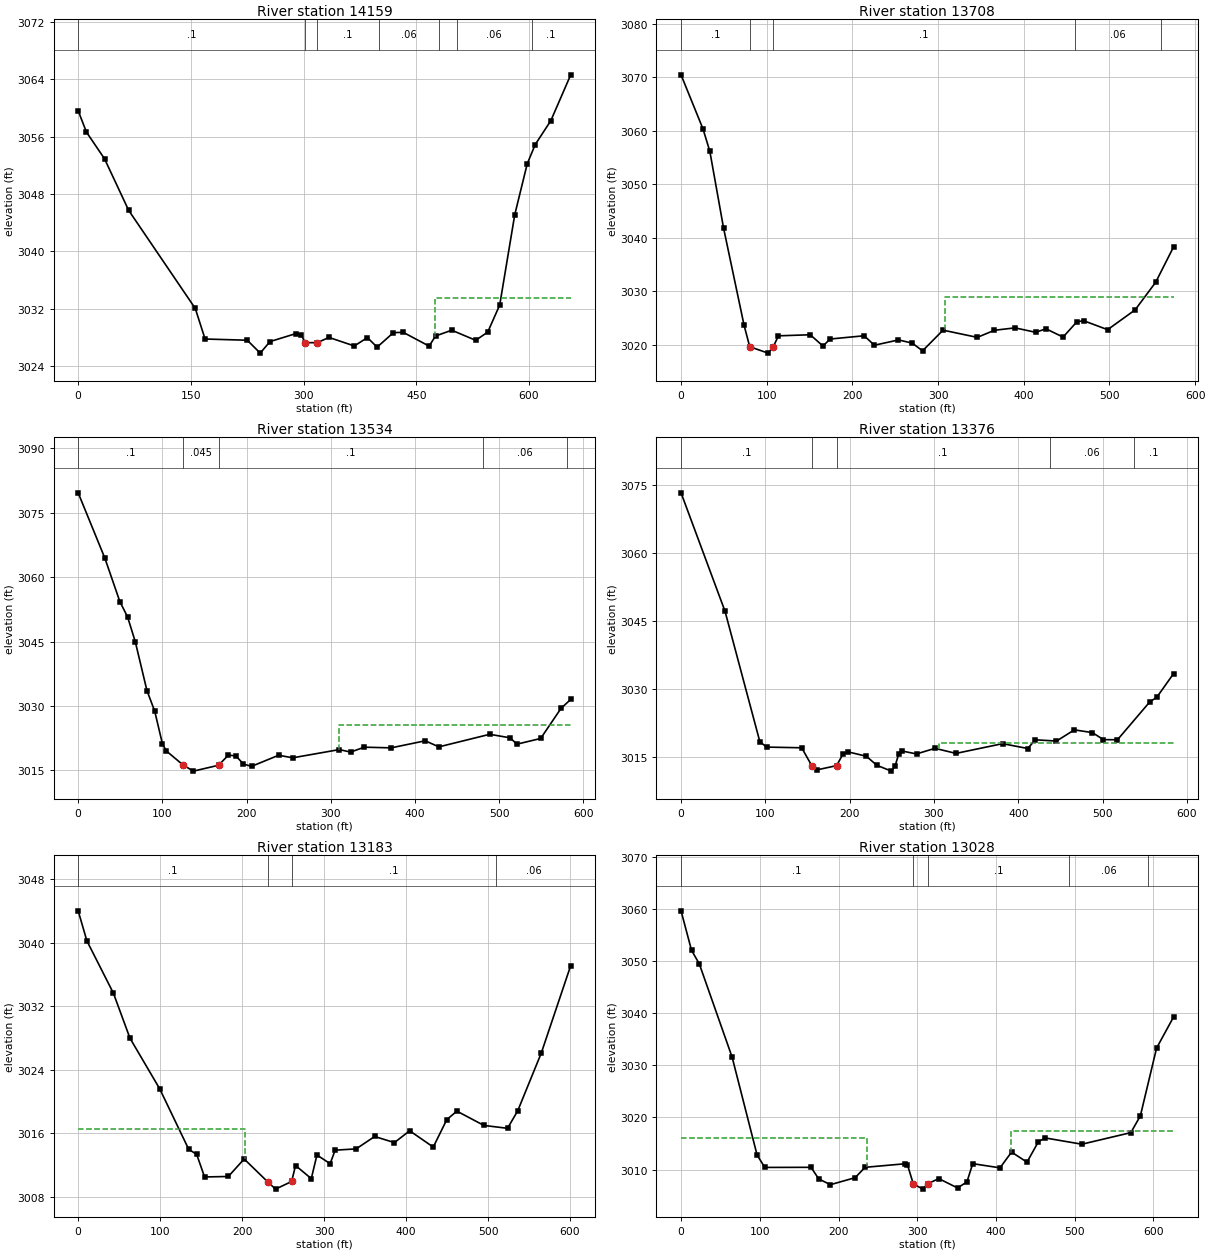
Type RM Length L Ch R = 1 ,14159   ,459.4,450.5,439.3
XS GIS Cut Line= 4
2331953.17520111558146.9590442612332103.01730632  558159.0153056
2332420.78590876558289.0506957572332582.68427531558288.189534233
#Sta/Elev= 30
       0 3059.64      11 3056.66    35.1 3052.93    67.2 3045.74   155.9 3032.04
   168.9 3027.78   225.1 3027.61   242.3 3025.81   255.3 3027.42   289.9 3028.54
     297 3028.37   302.1 3027.26   318.5 3027.28   333.8    3028   367.6 3026.81
     385 3027.98   397.9 3026.64   419.5 3028.66   432.5 3028.72   467.1 3026.79
   475.7  3028.2   497.2 3029.01   529.1  3027.6   545.1 3028.74   561.1 3032.53
   581.1 3045.13   597.7 3052.23   608.3 3054.91   629.1 3058.25   655.6 3064.65
#Mann= 7 ,-1,0
       0      .1       0   302.1    .045       0   318.5      .1       0
  400.33     .06       0  480.33      .1       0  503.67     .06       0
  603.67      .1       0
#XS Ineff= 2 , 0
                          474.82         3033.57
Permanent Ineff=
       F       F
Bank Sta=302.1,318.5
XS Rating Curve= 0 ,0
Exp/Cntr(USF)=0,0
Exp/Cntr=0.3,0.1

Type RM Length L Ch R = 1 ,13708   ,185.5,174,160.6
XS GIS Cut Line= 2
2331974.60204968558584.011743032 2332549.0977399558562.178084696
#Sta/Elev= 30
       0  3070.5    25.6 3060.38    33.6 3056.19    49.6 3041.84    73.6 3023.59
   80.17 3019.59   101.6 3018.39  107.73 3019.61   113.7 3021.63   150.8 3021.83
   165.7 3019.71   173.9 3021.03   213.7 3021.64   225.7 3019.87   253.8 3020.86
   269.8 3020.27   281.9 3018.82   305.8 3022.69   345.8 3021.34   365.8 3022.67
   389.9 3023.12   413.9 3022.29   425.9 3022.95   445.9 3021.39   461.9 3024.24
   469.9 3024.46   497.9 3022.78     530 3026.49     554 3031.66   574.9 3038.29
#Mann= 5 ,-1,0
       0      .1       0   80.17    .045       0  107.73      .1       0
     460     .06       0     560      .1       0
#XS Ineff= 2 , 0
                          307.61         3028.91
Permanent Ineff=
       F       F
Bank Sta=80.17,107.73
XS Rating Curve= 0 ,0
Exp/Cntr=0.3,0.1

Type RM Length L Ch R = 1 ,13534   ,152,158.6,159.7
XS GIS Cut Line= 3
2331997.09443884558813.4980640062332266.92504977558660.402681923
 2332539.6261991558626.913067092
#Sta/Elev= 30
       0 3079.65    31.8 3064.38    49.5 3054.31    58.7 3050.73    67.9 3044.91
    81.7 3033.56    90.9 3028.79   100.1 3021.15   104.7 3019.51  124.91 3016.19
   136.9 3014.81   166.8 3016.18   178.3 3018.53   187.3 3018.37   196.2 3016.47
   205.9 3015.92   238.1 3018.51   254.8 3017.91   310.2 3019.83   323.6 3019.24
   339.7 3020.39   371.7 3020.23   412.2 3021.88   428.4 3020.46   488.8 3023.39
     513 3022.57   521.1 3021.09   549.3 3022.42   573.4 3029.41     585 3031.53
#Mann= 5 ,-1,0
       0      .1       0  124.91    .045       0   166.8      .1       0
  480.24     .06       0  580.24      .1       0
#XS Ineff= 2 , 0
                           309.3         3025.48
Permanent Ineff=
       F       F
Bank Sta=124.91,166.8
XS Rating Curve= 0 ,0
Exp/Cntr(USF)=0,0
Exp/Cntr=0.3,0.1

Type RM Length L Ch R = 1 ,13376   ,198.4,192.5,186.1
XS GIS Cut Line= 3
2332019.45322637558910.5354632322332135.85376972558896.609845109
2332574.76023172558737.215383935
#Sta/Elev= 30
       0 3073.37    52.2 3047.23    93.4 3018.52   101.4 3017.29   143.1 3017.14
  155.02  3013.2   160.7 3012.25  184.51  3013.2     192 3015.73   198.4 3016.22
   219.7 3015.28   232.3 3013.27   249.5 3011.99   253.8 3013.07     258 3015.66
   262.3 3016.42   279.3 3015.78   301.2 3017.02   326.1  3015.9   381.4 3018.05
   411.2 3016.98   420.2  3018.9   445.3 3018.62   466.5 3021.09   487.8 3020.49
     501 3018.94   517.6  3018.9   555.9 3027.25   564.4 3028.31   584.2  3033.5
#Mann= 5 ,-1,0
       0      .1       0  155.02    .045       0  184.51      .1       0
  437.23     .06       0  537.23      .1       0
#XS Ineff= 2 , 0
                           306.5         3018.26
Permanent Ineff=
       F       F
Bank Sta=155.02,184.51
XS Rating Curve= 0 ,0
Exp/Cntr=0.3,0.1

Type RM Length L Ch R = 1 ,13183   ,154.5,154.6,155.3
XS GIS Cut Line= 4
2332073.64212989559123.5162127252332188.46366645559107.249828379
 2332423.8478164558948.4133694672332619.04442856558900.571062566
#Sta/Elev= 30
       0    3044    10.6 3040.23      43 3033.64    63.2 3027.98    99.5 3021.61
   134.9    3014   144.6 3013.37   154.2 3010.53   183.2 3010.59   202.5 3012.79
   231.4  3009.9   240.8    3009   260.4 3009.96   265.2 3011.97   284.4 3010.32
   291.3 3013.29   307.4  3012.2   313.5  3013.9   339.1 3014.06   361.7 3015.62
   385.8 3014.85   404.4 3016.34   433.2 3014.29   449.7 3017.74     462 3018.81
     495 3017.01   523.8 3016.65   536.2 3018.84     565 3026.12   600.9 3037.12
#Mann= 4 ,-1,0
       0      .1       0   231.4    .045       0   260.4      .1       0
  509.93     .06       0
#XS Ineff= 2 , 0
           203.1 3016.61
Permanent Ineff=
       F       F
Bank Sta=231.4,260.4
XS Rating Curve= 0 ,0
Exp/Cntr(USF)=0,0
Exp/Cntr=0.3,0.1

Type RM Length L Ch R = 1 ,13028   ,245.3,253.3,256.1
XS GIS Cut Line= 3
2332125.31182134559342.6339783322332503.26604586559075.673905824
2332661.14565863559035.486368027
#Sta/Elev= 30
       0 3059.59    13.3 3052.03    23.2 3049.42    64.9 3031.53    96.6 3012.77
   106.4  3010.4   165.1 3010.42   174.9  3008.2   189.7 3007.09   221.2 3008.44
   233.7 3010.42   284.4  3011.1   287.5 3010.94  294.98 3007.25   307.1 3006.24
   313.1 3007.26   327.4 3008.25   351.2 3006.47   363.1 3007.62   370.5 3011.12
   405.1 3010.32   419.8 3013.34   439.4 3011.41     454 3015.36   462.7 3016.05
   509.1 3014.85   571.3 3017.07   583.4 3020.29     604 3033.28   625.6 3039.25
#Mann= 5 ,-1,0
       0      .1       0  294.98    .045       0   313.1      .1       0
  492.73     .06       0  592.73      .1       0
#XS Ineff= 2 , 0
          235.83 3016.06  419.35         3017.35
Permanent Ineff=
       F       F
Bank Sta=294.98,313.1
XS Rating Curve= 0 ,0
Exp/Cntr(USF)=0,0
Exp/Cntr=0.3,0.1