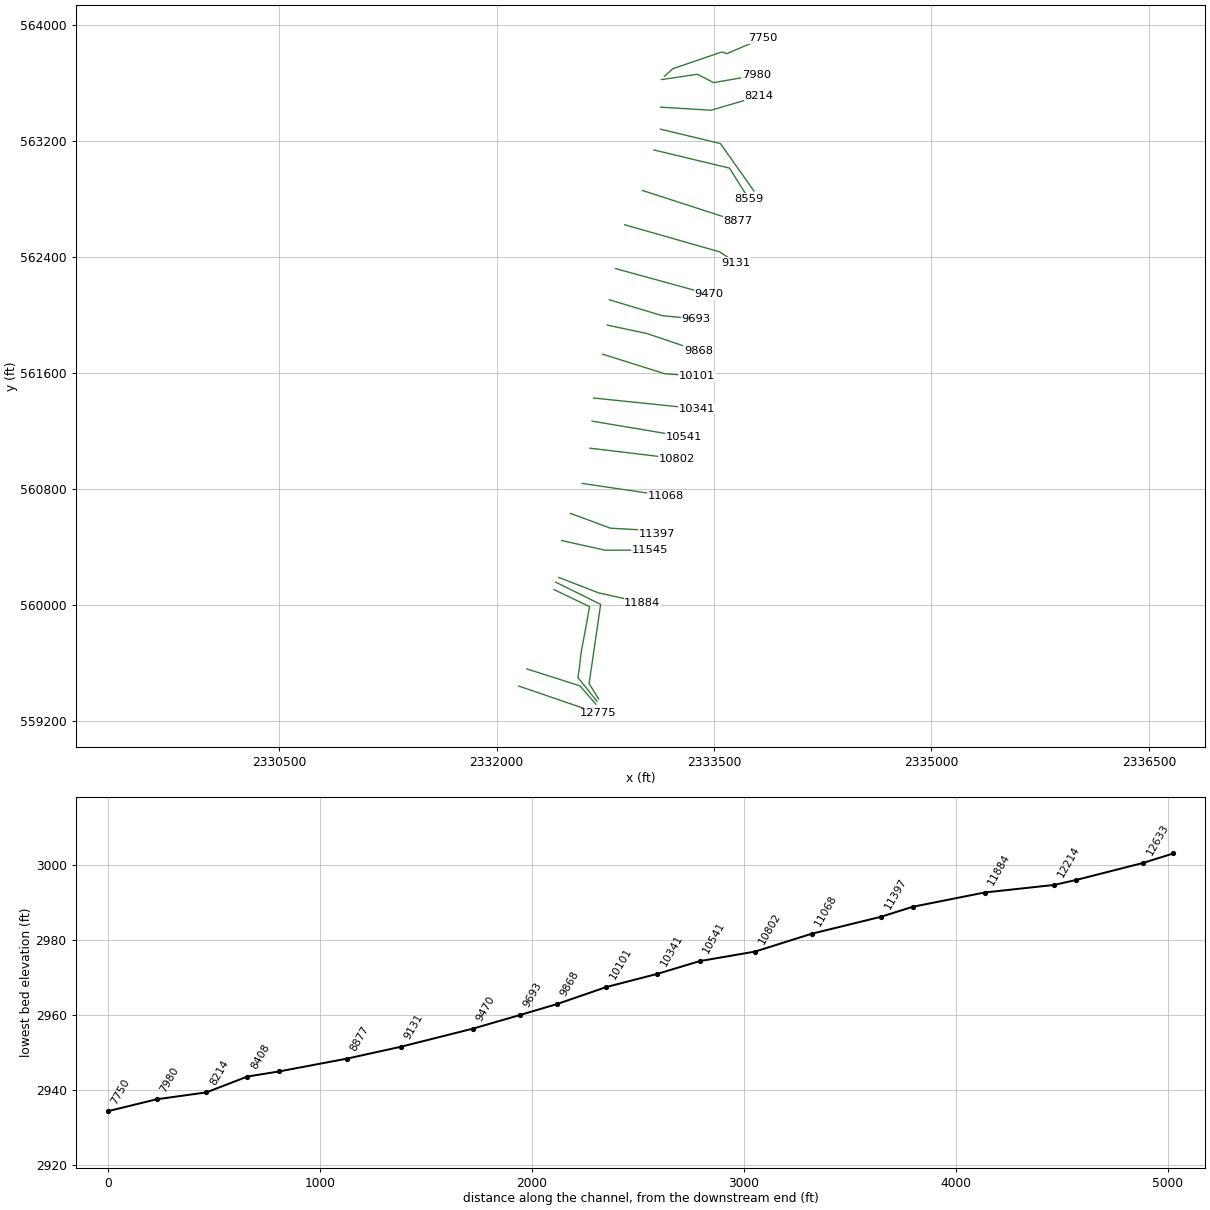
HEC-RAS study LTTLRV2.prj: LTTLRV2

--- LTTLRV2.g01 (geometry) --- (continued)

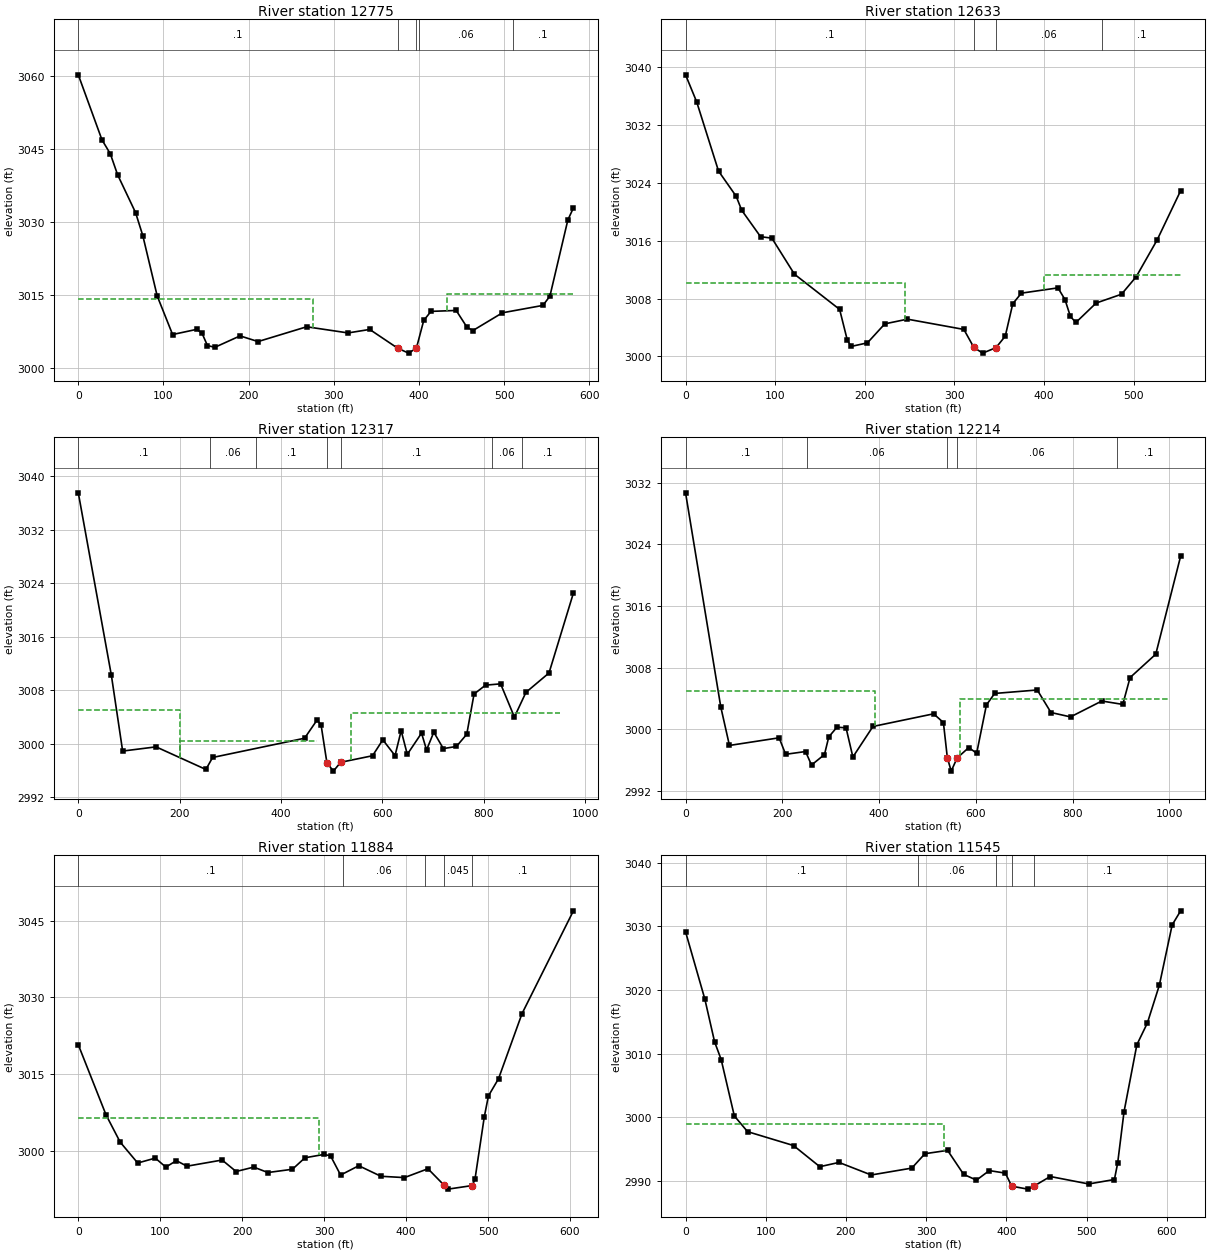
Type RM Length L Ch R = 1 ,12775   ,142.4,142.1,142.5
XS GIS Cut Line= 2
2332152.59699856559438.2145394432332702.29145768559249.559383524
#Sta/Elev= 30
       0 3060.31    27.8 3046.91    37.6 3044.04    46.1 3039.74    67.2 3031.94
    75.7  3027.2    92.6 3014.77   110.7 3006.81   139.1 3007.88   145.3 3007.05
   151.6 3004.54   160.3 3004.18   189.9 3006.53     211 3005.36   268.1 3008.41
   316.7 3007.14   342.1 3007.86  374.86    3004   387.7 3002.98   396.9    3004
   405.5 3009.71     414 3011.58   443.6 3011.77   456.3 3008.31   463.3 3007.64
   497.9 3011.29   545.4 3012.81   553.6 3014.71   574.7 3030.42   581.2 3032.89
#Mann= 5 ,-1,0
       0      .1       0  374.86    .045       0   396.9      .1       0
     400     .06       0     510      .1       0
#XS Ineff= 2 , 0
          275.83 3014.16  432.68         3015.21
Permanent Ineff=
       F       F
Bank Sta=374.86,396.9
XS Rating Curve= 0 ,0
Exp/Cntr=0.3,0.1

Type RM Length L Ch R = 1 ,12633   ,316.4,316.4,316.4
BEGIN DESCRIPTION:
structure xs 4
END DESCRIPTION:
XS GIS Cut Line= 3
2332208.40244053559556.3804492492332575.02950621559439.275438272
2332684.61708546559312.612857825
#Sta/Elev= 30
       0 3038.97    12.4 3035.23    36.8 3025.65    56.5 3022.16    62.7 3020.22
    83.7 3016.57    96.3 3016.37   121.5 3011.38   171.9 3006.51   180.3 3002.34
   184.5 3001.38   202.9 3001.88   222.3 3004.51   247.5 3005.16   310.5 3003.74
   321.7 3001.24   331.5 3000.46   346.4 3001.22   356.7 3002.81   365.1  3007.3
   374.7 3008.76   415.5 3009.49   423.3 3007.88   429.4 3005.53   435.5  3004.7
   458.1 3007.39   486.4 3008.61   502.8 3011.03   526.1 3016.11   552.4 3022.94
#Mann= 4 ,-1,0
       0      .1       0   321.7    .045       0   346.4     .06       0
  464.88      .1       0
#XS Ineff= 2 , 0
          244.73  3010.2  399.89         3011.21
Permanent Ineff=
       F       F
Bank Sta=321.7,346.4
XS Rating Curve= 0 ,0
Exp/Cntr(USF)=0,0
Exp/Cntr=0.5,0.3

Type RM Length L Ch R = 1 ,12317   ,102.5,102.5,102.5
BEGIN DESCRIPTION:
structure xs 3
END DESCRIPTION:
XS GIS Cut Line= 6
2332397.30149334560103.0744151042332641.25113368559985.823720307
2332581.62637076559661.6888422292332569.14096231559547.689251381
2332559.76055822559497.4409945242332692.12881098559333.423027993
#Sta/Elev= 30
       0 3037.53    65.3 3010.22    87.5 2998.91   153.4 2999.54   251.7 2996.16
     265 2997.95   446.4 3000.83   470.9 3003.53   478.9 3002.86   490.5 2997.16
   503.3 2995.91  517.59 2997.23   580.5 2998.21   600.8 3000.59   624.9 2998.23
     637 3001.96   649.1 2998.42   677.2 3001.59   687.1 2999.08   701.4 3001.73
   720.2 2999.28     746  2999.6   766.4 3001.42   780.8 3007.44   803.5 3008.77
   833.2 3008.96   860.4    3004   883.2 3007.69   928.7 3010.59976.8182 3022.54
#Mann= 7 ,-1,0
       0      .1       0     260     .06       0  350.66      .1       0
   490.5    .045       0  517.59      .1       0  816.05     .06       0
  876.05      .1       0
#XS Ineff= 3 ,-1
       0     200    3005     200     470  3000.4     538     950  3004.6
Permanent Ineff=
       F       F       F
Bank Sta=490.5,517.59
XS Rating Curve= 0 ,0
Exp/Cntr(USF)=0,0
Exp/Cntr=0.5,0.3

Type RM Length L Ch R = 1 ,12214   ,296.1,329.8,360
BEGIN DESCRIPTION:
structure xs 2
END DESCRIPTION:
XS GIS Cut Line= 5
 2332406.9245036560155.3136136722332717.61026351560001.345449472
2332650.24919167559540.8156726222332637.56425143 559455.32221972
2332703.30011117559349.421411274
#Sta/Elev= 30
       0 3030.67    72.8 3002.91    90.7 2997.92   193.4 2998.91   206.8 2996.77
     248 2997.13   260.3 2995.38   287.1 2996.74     296 2999.03     313 3000.29
   331.7  3000.2   345.8 2996.42   387.3 3000.38   512.7 3002.02   532.9 3000.89
     541 2996.35     549 2994.59   561.2 2996.29   585.4 2997.65   601.6  2996.9
   621.8 3003.17   638.8 3004.66   726.9 3005.11   755.2 3002.19   795.6 3001.62
   860.3 3003.68   903.6 3003.24   918.7 3006.72   971.8 3009.751023.248 3022.47
#Mann= 5 ,-1,0
       0      .1       0     250     .06       0     541    .045       0
   561.2     .06       0  892.17      .1       0
#XS Ineff= 3 ,-1
       0     391    3005     391     535  2999.5     567    1000    3004
Permanent Ineff=
       F       F       F
Bank Sta=541,561.2
XS Rating Curve= 0 ,0
Exp/Cntr(USF)=0,0
Exp/Cntr=0.5,0.3

Type RM Length L Ch R = 1 ,11884   ,331.5,339.2,344.3
XS GIS Cut Line= 3
2332428.56870515560187.5320440172332701.41378773560081.708907073
2333005.39208135560013.281150982
#Sta/Elev= 30
       0 3020.75    33.9 3007.04    51.1 3001.74    72.5 2997.66      94 2998.62
   106.8 2996.86   119.7 2998.12   132.6 2997.04   175.5 2998.24   192.6    2996
   214.1 2996.86   231.3  2995.8   261.3 2996.44   276.6 2998.68   299.6 2999.33
   307.8 2999.07   320.1 2995.31   342.3 2997.13   369.3 2995.07     398 2994.81
   426.7 2996.54   446.52993.307   451.3 2992.56   480.8 2993.26   484.1 2994.49
   495.4 3006.62   500.5 3010.76   512.8 3014.11   541.5 3026.83   604.2  3046.9
#Mann= 5 ,-1,0
       0      .1       0  322.65     .06       0  422.65      .1       0
   446.5    .045       0   480.8      .1       0
#XS Ineff= 2 , 0
           294.2 3006.51
Permanent Ineff=
       F       F
Bank Sta=446.5,480.8
XS Rating Curve= 0 ,0
Exp/Cntr=0.3,0.1

Type RM Length L Ch R = 1 ,11545   ,149.3,148,146.5
XS GIS Cut Line= 3
2332448.79274585560442.081925238 2332748.8426426560375.283477717
2333058.77911458560376.263413625
#Sta/Elev= 30
       0 3029.13      24 3018.59    36.2 3011.86    44.4 3009.08    60.8 3000.24
    77.3 2997.77   134.6 2995.59   167.4 2992.27   191.3 2992.94   231.5 2990.97
   282.1 2992.05   298.5 2994.31   326.7 2994.83   346.7 2991.07   362.7 2990.16
   378.7 2991.66   398.7 2991.26   406.7 2989.21   426.7 2988.75   434.7 2989.25
   454.7 2990.73   502.7 2989.56   534.7 2990.26   538.7 2992.79   546.7  3000.9
   562.7 3011.41   575.8 3014.82   590.7 3020.74   606.7 3030.21   617.3 3032.42
#Mann= 5 ,-1,0
       0      .1       0     290     .06       0   387.4      .1       0
   406.7    .045       0   434.7      .1       0
#XS Ineff= 2 , 0
           321.8 2998.99
Permanent Ineff=
       F       F
Bank Sta=406.7,434.7
XS Rating Curve= 0 ,0
Exp/Cntr=0.3,0.1

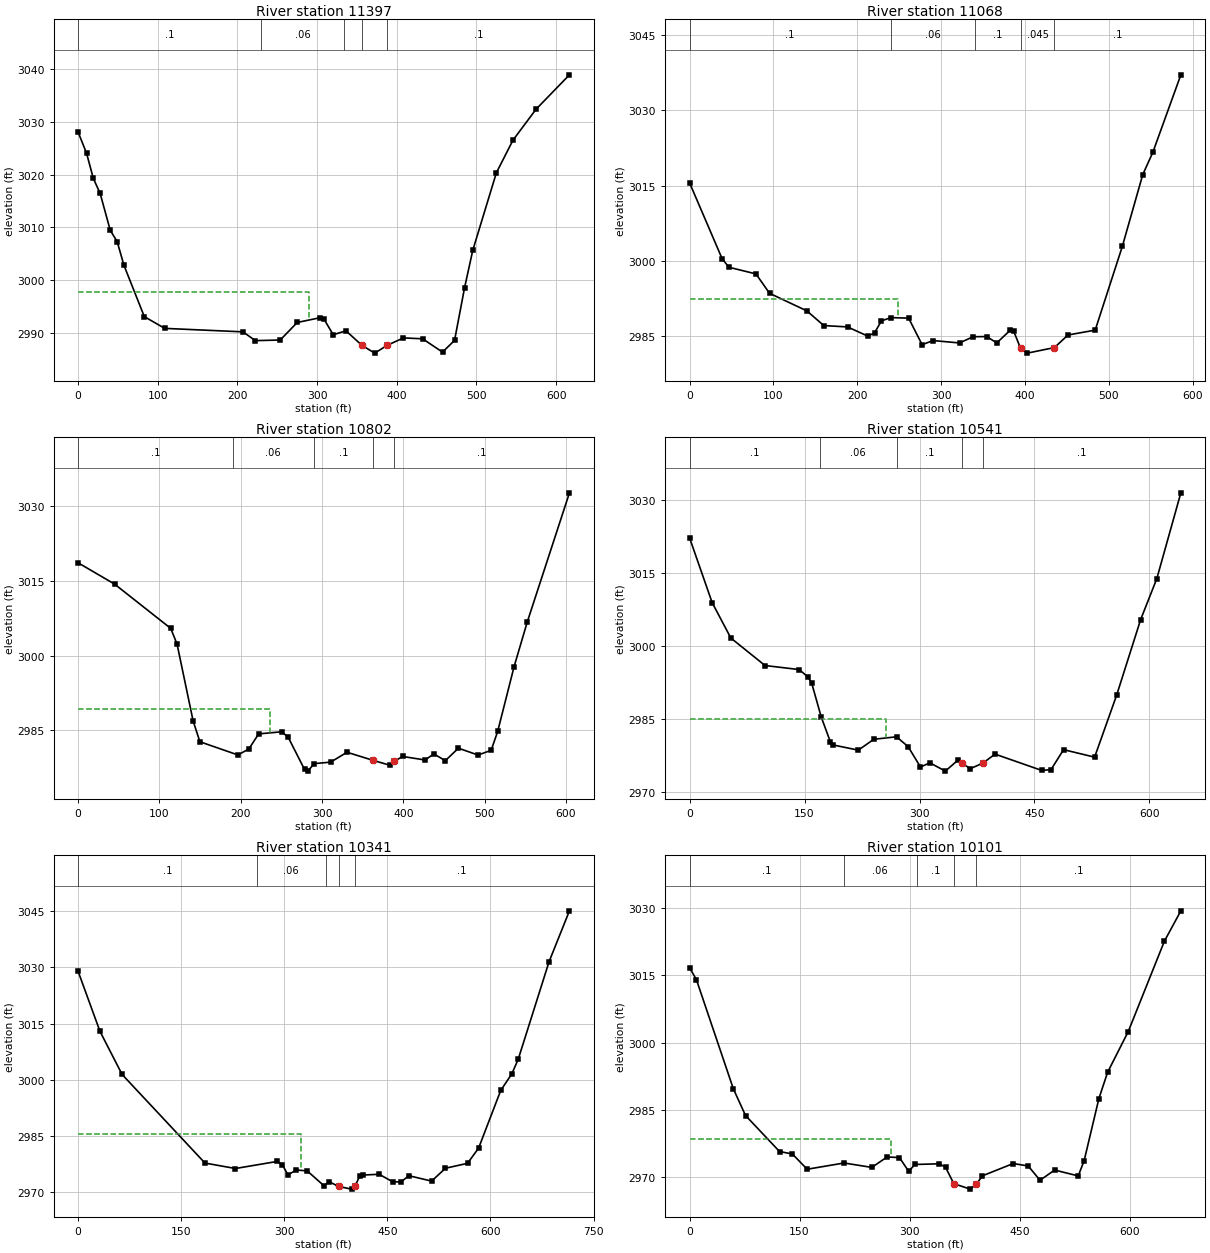
Type RM Length L Ch R = 1 ,11397   ,323.3,328.6,318.1
XS GIS Cut Line= 4
2332510.26603091560629.2115396242332785.42744868560527.298701094
2333002.01994438560515.2003032342333104.55490312560487.042433722
#Sta/Elev= 30
       0 3028.08    10.6 3024.06    19.1 3019.28    27.6 3016.46    40.4  3009.4
      49  3007.3    57.5  3002.8    83.1 2993.04   108.7 2990.81   206.9 2990.15
   222.5 2988.48   253.7  2988.6     275 2991.93   304.2 2992.85   308.2 2992.67
   320.2  2989.6   336.2 2990.35   356.3 2987.58   372.3 2986.11   388.3 2987.62
   408.4    2989   432.4 2988.83   457.4  2986.3   472.5 2988.53     485 2998.48
   495.3  3005.6     525 3020.36   545.8 3026.54   574.8 3032.42   616.7 3038.95
#Mann= 5 ,-1,0
       0      .1       0     230     .06       0  333.43      .1       0
   356.3    .045       0   388.3      .1       0
#XS Ineff= 2 , 0
          289.65 2997.71
Permanent Ineff=
       F       F
Bank Sta=356.3,388.3
XS Rating Curve= 0 ,0
Exp/Cntr(USF)=0,0
Exp/Cntr=0.3,0.1

Type RM Length L Ch R = 1 ,11068   ,262.9,266.9,265.2
XS GIS Cut Line= 2
2332589.81441363560836.2646029642333169.25682637560750.649348817
#Sta/Elev= 30
       0 3015.58    38.8 3000.43    46.9  2998.7    79.2 2997.37    95.4  2993.5
   139.9 2989.99   160.1 2987.06   188.4 2986.79   212.7 2984.94   220.7 2985.65
   228.8 2987.99     240 2988.65   261.2 2988.54   277.3 2983.24   290.2 2984.07
   321.9 2983.59     338 2984.83   354.2 2984.87   366.3  2983.6   382.5 2986.16
   386.5 2985.89   394.6 2982.56   402.7 2981.56     435 2982.67   451.2 2985.18
   483.6 2986.15   515.9 3002.84   540.3 3017.19   552.3 3021.63   585.7  3037.1
#Mann= 5 ,-1,0
       0      .1       0     240     .06       0     340      .1       0
   394.6    .045       0     435      .1       0
#XS Ineff= 2 , 0
          248.79 2992.44
Permanent Ineff=
       F       F
Bank Sta=394.6,435
XS Rating Curve= 0 ,0
Exp/Cntr=0.3,0.1

Type RM Length L Ch R = 1 ,10802   ,244.1,260.3,233.9
XS GIS Cut Line= 2
2332643.70769657561079.333228656  2333243.803793561007.274445422
#Sta/Elev= 30
       0 3018.66    44.8 3014.39   113.9 3005.49   121.7 3002.34   141.5 2986.88
   149.8 2982.71   196.6 2980.06     210 2981.25   222.1 2984.29   250.3 2984.71
   258.3 2983.66   278.5 2977.15   282.5 2976.81   290.5 2978.32   310.7 2978.62
   330.8  2980.6   363.1 2978.96   383.2 2978.01  388.98 2978.81   399.3 2979.75
   426.8 2979.05   437.6 2980.27   451.7 2978.91   467.8 2981.42     492 2980.04
   508.1    2981   516.1 2984.78   536.3  2997.8   552.4 3006.72   604.4 3032.72
#Mann= 5 ,-1,0
       0      .1       0     190     .06       0     290      .1       0
   363.1    .045       0  388.98      .1       0
#XS Ineff= 2 , 0
          236.23 2989.26
Permanent Ineff=
       F       F
Bank Sta=363.1,388.98
XS Rating Curve= 0 ,0
Exp/Cntr(USF)=0,0
Exp/Cntr=0.3,0.1

Type RM Length L Ch R = 1 ,10541   ,196.2,199.8,203
XS GIS Cut Line= 2
2332659.06448643561265.9772901472333291.05545414561159.661052589
#Sta/Elev= 30
       0 3022.23    29.5  3008.9    53.9 3001.62    98.5 2995.97   143.1 2995.14
   154.4 2993.62   159.3  2992.4   171.8  2985.4   183.7 2980.31   187.7 2979.64
   220.2 2978.59   240.4 2980.82     270 2981.33   285.1 2979.32   301.3 2975.12
   313.5 2975.99   333.7 2974.28     350 2976.52   355.8 2975.88   366.2 2974.78
   382.4 2975.91   398.6 2977.77   459.5 2974.42   471.6  2974.6   487.9 2978.69
   528.4 2977.15   557.2  2989.9   588.4 3005.38   609.6 3013.84   640.9 3031.44
#Mann= 5 ,-1,0
       0      .1       0     170     .06       0     270      .1       0
   355.8    .045       0   382.4      .1       0
#XS Ineff= 2 , 0
          255.94 2985.04
Permanent Ineff=
       F       F
Bank Sta=355.8,382.4
XS Rating Curve= 0 ,0
Exp/Cntr(USF)=0,0
Exp/Cntr=0.3,0.1

Type RM Length L Ch R = 1 ,10341   ,244.3,240.7,234.7
XS GIS Cut Line= 2
2332668.51481866561425.4516464842333379.65231877561352.211571722
#Sta/Elev= 30
       0 3028.96    31.8 3012.96      64 3001.46   184.6 2977.83   228.9 2976.38
   289.2 2978.25   297.2 2977.42   305.3 2974.64   317.3    2976   333.4 2975.73
   357.5 2971.82   365.6 2972.83   379.1 2971.59   397.8 2970.88   402.8 2971.61
   409.8  2974.4   413.8 2974.63     438 2974.84   458.1  2972.8   470.1 2972.84
   481.2 2974.46   514.4 2973.02   534.5 2976.45   566.6 2977.76   582.7 2981.81
   614.9 2997.19     631 3001.61   640.4 3005.54   685.3 3031.56   714.9  3045.1
#Mann= 5 ,-1,0
       0      .1       0     260     .06       0     360      .1       0
   379.1    .045       0   402.8      .1       0
#XS Ineff= 2 , 0
          324.42 2985.62
Permanent Ineff=
       F       F
Bank Sta=379.1,402.8
XS Rating Curve= 0 ,0
Exp/Cntr(USF)=0,0
Exp/Cntr=0.3,0.1

Type RM Length L Ch R = 1 ,10101   ,233.3,233.1,232.3
XS GIS Cut Line= 3
2332731.12326967 561727.862277762333159.93209449561593.195043519
2333379.65231877561576.656962122
#Sta/Elev= 30
       0 3016.71     9.4 3014.03    59.8 2989.69    76.4 2983.76   122.7 2975.75
   140.2  2975.2   160.4  2971.8   210.7 2973.19   248.5 2972.21   269.4 2974.53
   286.2  2974.4   298.8 2971.32   307.2 2972.86   340.7 2973.01   349.1 2972.22
   360.3 2968.59   382.6 2967.37     391 2968.46   399.4 2970.34   441.3 2973.07
   461.7 2972.53   477.8 2969.35   497.8 2971.62   529.9 2970.31     538 2973.73
   558.1 2987.55     570 2993.41   598.1 3002.47   647.4  3022.6   669.8 3029.35
#Mann= 5 ,-1,0
       0      .1       0     210     .06       0     310      .1       0
   360.3    .045       0     391      .1       0
#XS Ineff= 2 , 0
          275.27 2978.47
Permanent Ineff=
       F       F
Bank Sta=360.3,391
XS Rating Curve= 0 ,0
Exp/Cntr(USF)=0,0
Exp/Cntr=0.3,0.1

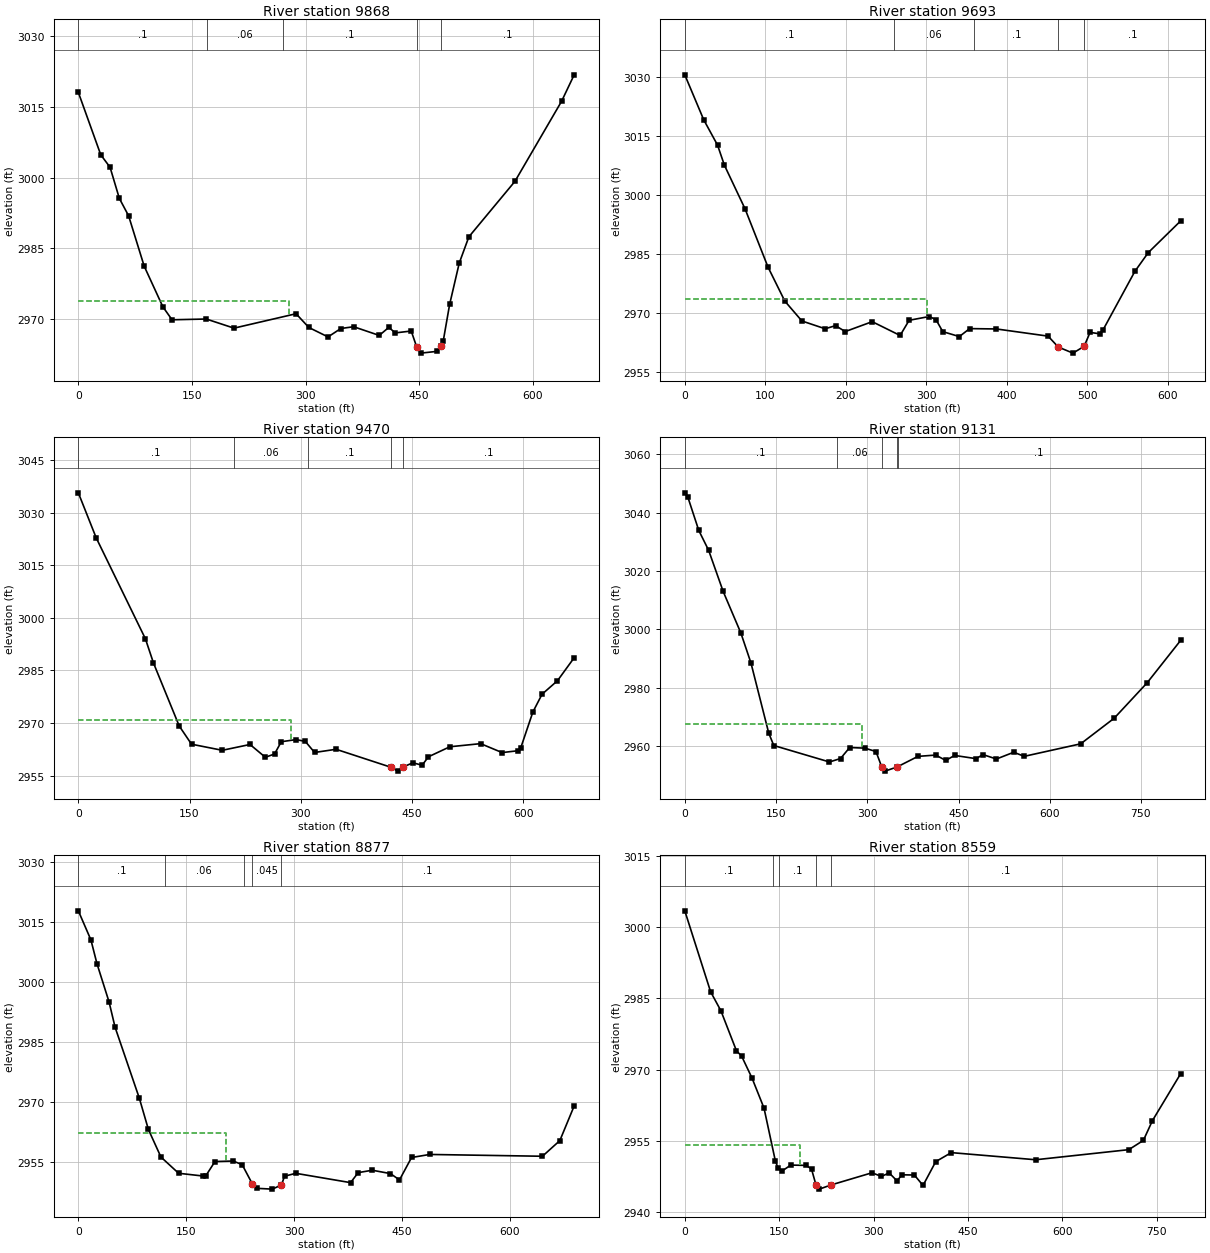
Type RM Length L Ch R = 1 ,9868    ,169.2,174.3,181.2
XS GIS Cut Line= 3
2332763.23550166561928.7249659372333039.85910462561869.697918602
2333391.91436541561750.481379562
#Sta/Elev= 30
       0 3018.03    29.6 3004.81    41.9 3002.16    54.1 2995.59    66.4 2991.88
    86.9 2981.24   111.6 2972.62   123.7 2969.88   168.9 2970.04   205.5 2968.11
   287.4 2971.16   304.3 2968.25   329.6 2966.25   346.5 2968.03   363.4 2968.41
   397.2 2966.57   409.9 2968.28   418.3  2967.1   439.4  2967.5   446.6 2964.16
   452.1 2962.82   473.2 2963.19   479.1  2964.3   481.7  2965.4   490.1 2973.12
   502.8 2981.88   515.5 2987.44   576.3 2999.18   637.9 3016.14   654.5 3021.74
#Mann= 5 ,-1,0
       0      .1       0     170     .06       0     270      .1       0
   446.6    .045       0   479.1      .1       0
#XS Ineff= 2 , 0
          278.03 2973.81
Permanent Ineff=
       F       F
Bank Sta=446.6,479.1
XS Rating Curve= 0 ,0
Exp/Cntr=0.3,0.1

Type RM Length L Ch R = 1 ,9693    ,224.7,223,220.8
XS GIS Cut Line= 3
2332777.19363928562103.5129837982333142.21272156561993.652871655
2333376.10844419561971.208332615
#Sta/Elev= 30
       0 3030.51    23.5 3019.11    40.7 3012.68    49.2 3007.59    74.9  2996.5
   103.4 2981.74   124.3 2973.11   145.5 2968.07   174.4 2966.09   187.3 2966.88
   199.4 2965.38   232.9 2967.89   267.6 2964.39   278.8 2968.24   303.9  2969.2
   312.2 2968.39   320.6 2965.36   341.2 2964.11     354 2966.13   387.3 2966.04
   451.5 2964.22   464.1 2961.46   482.4 2959.91   496.22961.624   503.7 2965.17
   515.4 2964.82   519.8 2965.81   559.4 2980.67     576 2985.41   616.2 2993.44
#Mann= 5 ,-1,0
       0      .1       0     260     .06       0     360      .1       0
   464.1    .045       0   496.2      .1       0
#XS Ineff= 2 , 0
          300.51 2973.52
Permanent Ineff=
       F       F
Bank Sta=464.1,496.2
XS Rating Curve= 0 ,0
Exp/Cntr(USF)=0,0
Exp/Cntr=0.3,0.1

Type RM Length L Ch R = 1 ,9470    ,340.6,339.6,335.8
XS GIS Cut Line= 2
2332820.90142583562318.5080419712333465.88660035562141.314312707
#Sta/Elev= 30
       0 3035.65    24.1 3022.81    90.5 2994.01   101.4  2987.1   136.1 2969.14
   152.7 2963.95   194.2 2962.21   231.6 2963.87   252.3 2960.22   264.7 2961.16
   273.8 2964.66   293.8 2965.26   306.2 2964.75   318.7 2961.59   347.7  2962.5
   422.4 2957.33   430.7 2956.27   437.5  2957.4   451.4 2958.65   463.8 2957.95
   472.3 2960.36   501.2 2963.22   542.7 2964.11   571.7 2961.56   592.8 2962.08
   596.6 2962.75   613.2 2973.13   625.6 2978.21   646.4 2982.06   668.9 2988.61
#Mann= 5 ,-1,0
       0      .1       0     210     .06       0     310      .1       0
   422.4    .045       0   437.5      .1       0
#XS Ineff= 2 , 0
           286.7  2970.9
Permanent Ineff=
       F       F
Bank Sta=422.4,437.5
XS Rating Curve= 0 ,0
Exp/Cntr(USF)=0,0
Exp/Cntr=0.3,0.1

Type RM Length L Ch R = 1 ,9131    ,256,254.3,252.6
XS GIS Cut Line= 3
2332883.50987683562620.9186732472333537.94538358562434.274611756
2333650.16807878562359.853245465
#Sta/Elev= 30
       0 3046.83     4.9 3045.43      23 3033.93    39.2 3027.12    63.1 3013.02
    92.2 2998.77   108.8 2988.49     138 2964.47   146.3 2960.22   237.8 2954.58
     256 2955.76   271.1 2959.53     296 2959.32   314.3 2958.16     324 2952.77
   329.3 2951.44   349.1 2952.88   383.4  2956.5   412.5 2956.94   429.1 2955.11
   443.6 2956.82     479 2955.71   490.2 2957.11   512.3 2955.59   540.8 2957.91
   558.1 2956.51   650.9  2960.8     706 2969.58     760 2981.68   815.2 2996.24
#Mann= 5 ,-1,0
       0      .1       0     250     .06       0     324    .045       0
   349.1     .06       0     350      .1       0
#XS Ineff= 2 , 0
           290.7 2967.74
Permanent Ineff=
       F       F
Bank Sta=324,349.1
XS Rating Curve= 0 ,0
Exp/Cntr(USF)=0,0
Exp/Cntr=0.3,0.1

Type RM Length L Ch R = 1 ,8877    ,312.4,317.6,318.9
XS GIS Cut Line= 2
2333007.54548732562857.1769789312333663.16228559562644.544503815
#Sta/Elev= 30
       0 3017.79    17.5 3010.52    25.9 3004.59    42.7 2995.04    51.1  2988.7
    84.8 2970.98    97.4 2963.18   114.8  2956.3   139.4 2952.24   173.1 2951.56
   177.3 2951.64   189.9 2955.17   215.1  2955.3   227.7  2954.4   241.8 2949.61
   248.8 2948.47   269.8 2948.28   282.4 2949.34   286.6  2951.5   302.2 2952.23
   378.4  2949.9     389  2952.4   408.6    2953   433.8 2952.16   446.4 2950.58
   463.2 2956.18   488.5 2956.94   645.1 2956.49   669.3  2960.4   689.2 2969.05
#Mann= 5 ,-1,0
       0      .1       0     120     .06       0     230      .1       0
   241.8    .045       0   282.4      .1       0
#XS Ineff= 2 , 0
          204.68 2962.21
Permanent Ineff=
       F       F
Bank Sta=241.8,282.4
XS Rating Curve= 0 ,0
Exp/Cntr(USF)=0,0
Exp/Cntr=0.3,0.1

Type RM Length L Ch R = 1 ,8559    ,150.5,150.5,150.8
XS GIS Cut Line= 3
2333084.32943667563137.1430711672333606.46029223563011.926169154
2333739.94623494562799.293694038
#Sta/Elev= 30
       0 3003.43      41 2986.41    57.4  2982.4    82.1 2973.99    90.3 2972.87
   106.8 2968.26   125.9 2961.93   143.8 2950.89   147.9 2949.42   154.2 2948.67
   168.5 2949.95   193.2 2949.88   201.4  2949.1   208.4 2945.82   213.7 2944.89
  232.95 2945.79   297.5 2948.33   312.5 2947.56   324.8  2948.3   337.1 2946.65
   345.4  2947.9   364.8 2947.86   378.6 2945.67   398.8 2950.67   423.5 2952.57
   557.6 2951.07   705.6 2953.19   728.8 2955.14   743.2  2959.3     788 2969.16
#Mann= 5 ,-1,0
       0      .1       0     140     .06       0     150      .1       0
   208.4    .045       0  232.95      .1       0
#XS Ineff= 2 , 0
          183.44 2954.07
Permanent Ineff=
       F       F
Bank Sta=208.4,232.95
XS Rating Curve= 0 ,0
Exp/Cntr(USF)=0,0
Exp/Cntr=0.3,0.1

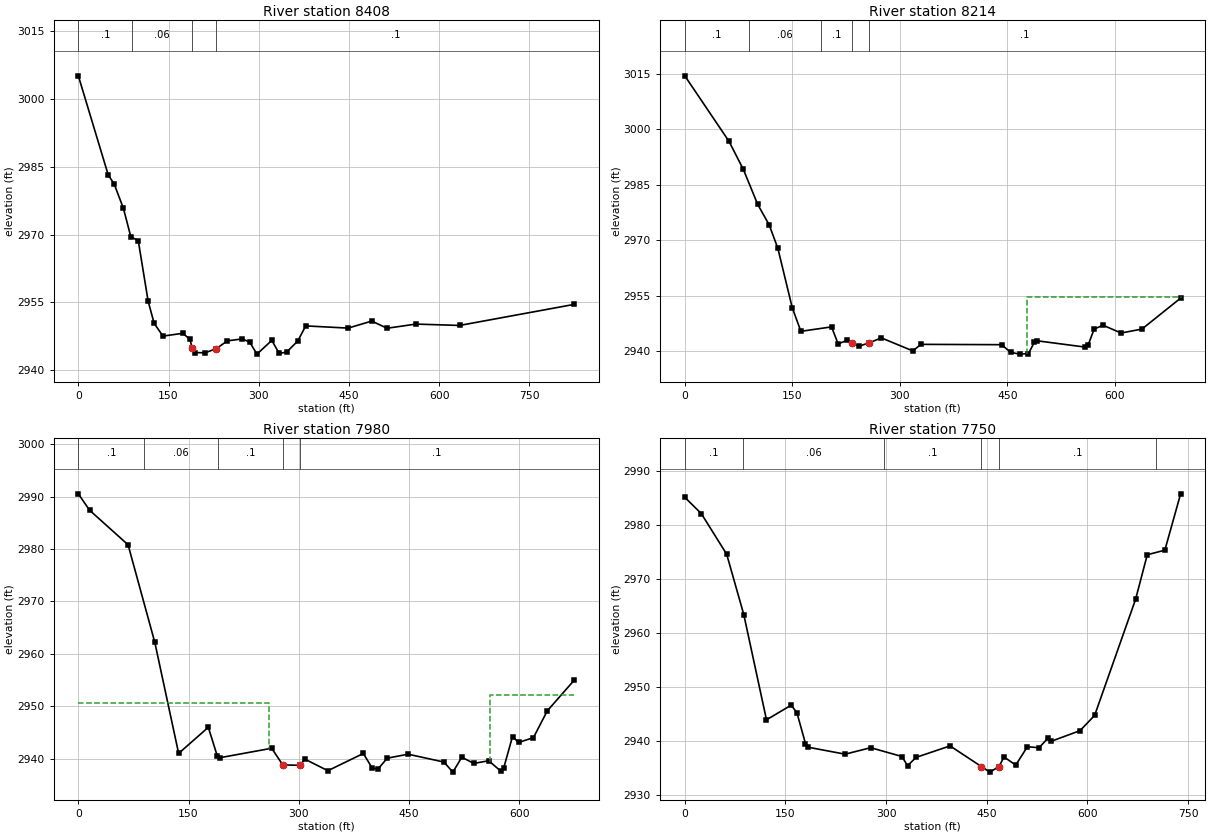
Type RM Length L Ch R = 1 ,8408    ,190.1,194,198.3
XS GIS Cut Line= 3
2333131.24259966563280.2197956082333543.71021791563181.294635135
2333775.09449155562854.338596283
#Sta/Elev= 30
       0 3005.13    49.7  2983.2    59.7 2981.16      75 2975.78    87.3  2969.5
    99.7 2968.63   116.1 2955.24   126.1 2950.33   140.8 2947.51   173.7 2948.13
   185.8  2946.8   189.1 2944.87   194.3 2943.87   210.7  2943.8   229.8 2944.76
   247.8 2946.46   272.4 2946.88   284.8 2946.22   297.1 2943.52   321.8 2946.56
   334.1 2943.68   346.5 2943.97   364.9 2946.41   378.2 2949.77   448.8 2949.28
     488 2950.84   513.5 2949.25   561.5 2950.17   634.1 2949.87   824.7 2954.53
#Mann= 4 ,-1,0
       0      .1       0      90     .06       0   189.1    .045       0
   229.8      .1       0
Bank Sta=189.1,229.8
XS Rating Curve= 0 ,0
Exp/Cntr(USF)=0,0
Exp/Cntr=0.3,0.1

Type RM Length L Ch R = 1 ,8214    ,242.7,234.1,224.2
XS GIS Cut Line= 3
2333130.61872401563432.3215751972333478.44345182563411.320836914
2333807.89253363563507.136705331
#Sta/Elev= 30
       0 3014.47    61.7 2996.76    81.7 2989.17   101.7 2979.73   117.8 2974.17
   129.8 2967.86   149.8 2951.88   161.9 2945.45   204.7 2946.65   213.9 2942.05
     226 2942.99   232.9 2942.35   242.5  2941.4   257.6 2942.37   274.1 2943.68
   318.1 2940.16   329.4 2941.93   441.9 2941.84   454.4 2939.79   466.9 2939.29
   479.4 2939.44   487.7 2942.57   491.9 2942.88   558.5 2941.19   562.7 2941.79
     571 2946.07   583.5 2947.09   608.5 2944.99   637.7 2946.06   691.6 2954.42
#Mann= 5 ,-1,0
       0      .1       0      90     .06       0     190      .1       0
   232.9    .045       0   257.6      .1       0
#XS Ineff= 2 , 0
                          476.74         2954.63
Permanent Ineff=
       F       F
Bank Sta=232.9,257.6
XS Rating Curve= 0 ,0
Exp/Cntr(USF)=0,0
Exp/Cntr=0.3,0.1

Type RM Length L Ch R = 1 ,7980    ,225.7,230.8,240.7
XS GIS Cut Line= 4
2333137.18145472563622.6407658872333385.25267569563659.392057883
2333496.81909782563601.6400276042333790.82943378563652.829327169
#Sta/Elev= 30
       0 2990.53    15.2 2987.42    67.7 2980.81   104.1 2962.19   136.5 2941.03
   176.9 2946.01     189 2940.58   193.1 2940.22   263.1 2942.01   278.3 2938.83
   302.1 2938.76   308.1 2939.95   339.6 2937.73   387.9 2941.02   400.1 2938.18
   408.2 2938.11   420.4 2940.12   448.8 2940.88   497.6 2939.38   509.7 2937.46
   521.9  2940.3   538.2 2939.12   558.5 2939.63   574.7 2937.68   578.8 2938.19
   590.9 2944.25   599.1 2943.11   619.4 2944.04   638.3 2949.16   674.8 2954.98
#Mann= 5 ,-1,0
       0      .1       0      90     .06       0     190      .1       0
   278.3    .045       0   302.1      .1       0
#XS Ineff= 2 , 0
           259.3 2950.66  560.22         2952.17
Permanent Ineff=
       F       F
Bank Sta=278.3,302.1
XS Rating Curve= 0 ,0
Exp/Cntr(USF)=0,0
Exp/Cntr=0.3,0.1

Type RM Length L Ch R = 1 ,7750    ,91.6,107,118.6
XS GIS Cut Line= 5
2333158.06976182563645.7398800672333215.07748142563697.717506756
2333553.77040372563813.4096435812333588.98105405563801.672760135
2333833.77890878563907.304711148
#Sta/Elev= 30
       0  2985.1    24.5 2982.11    62.4 2974.58    87.9 2963.41   121.7 2943.95
   158.6 2946.66   167.1 2945.24   179.8 2939.56     184 2938.87   238.9 2937.59
     277 2938.79   323.5 2937.16   331.9 2935.45   344.6    2937   395.3 2939.12
   441.8 2935.31   454.5 2934.27   468.3 2935.31   475.6 2937.08   493.1 2935.57
   510.5 2938.97   527.9 2938.78     541 2940.55   545.4 2939.95   588.9 2941.94
   610.7 2944.77   671.7 2966.24   689.1 2974.48   715.3 2975.33   738.8 2985.75
#Mann= 6 ,-1,0
       0      .1       0   87.15     .06       0  297.15      .1       0
   441.8    .045       0   468.3      .1       0  702.17     .06       0
Bank Sta=441.8,468.3
XS Rating Curve= 0 ,0
Exp/Cntr(USF)=0,0
Exp/Cntr=0.3,0.1