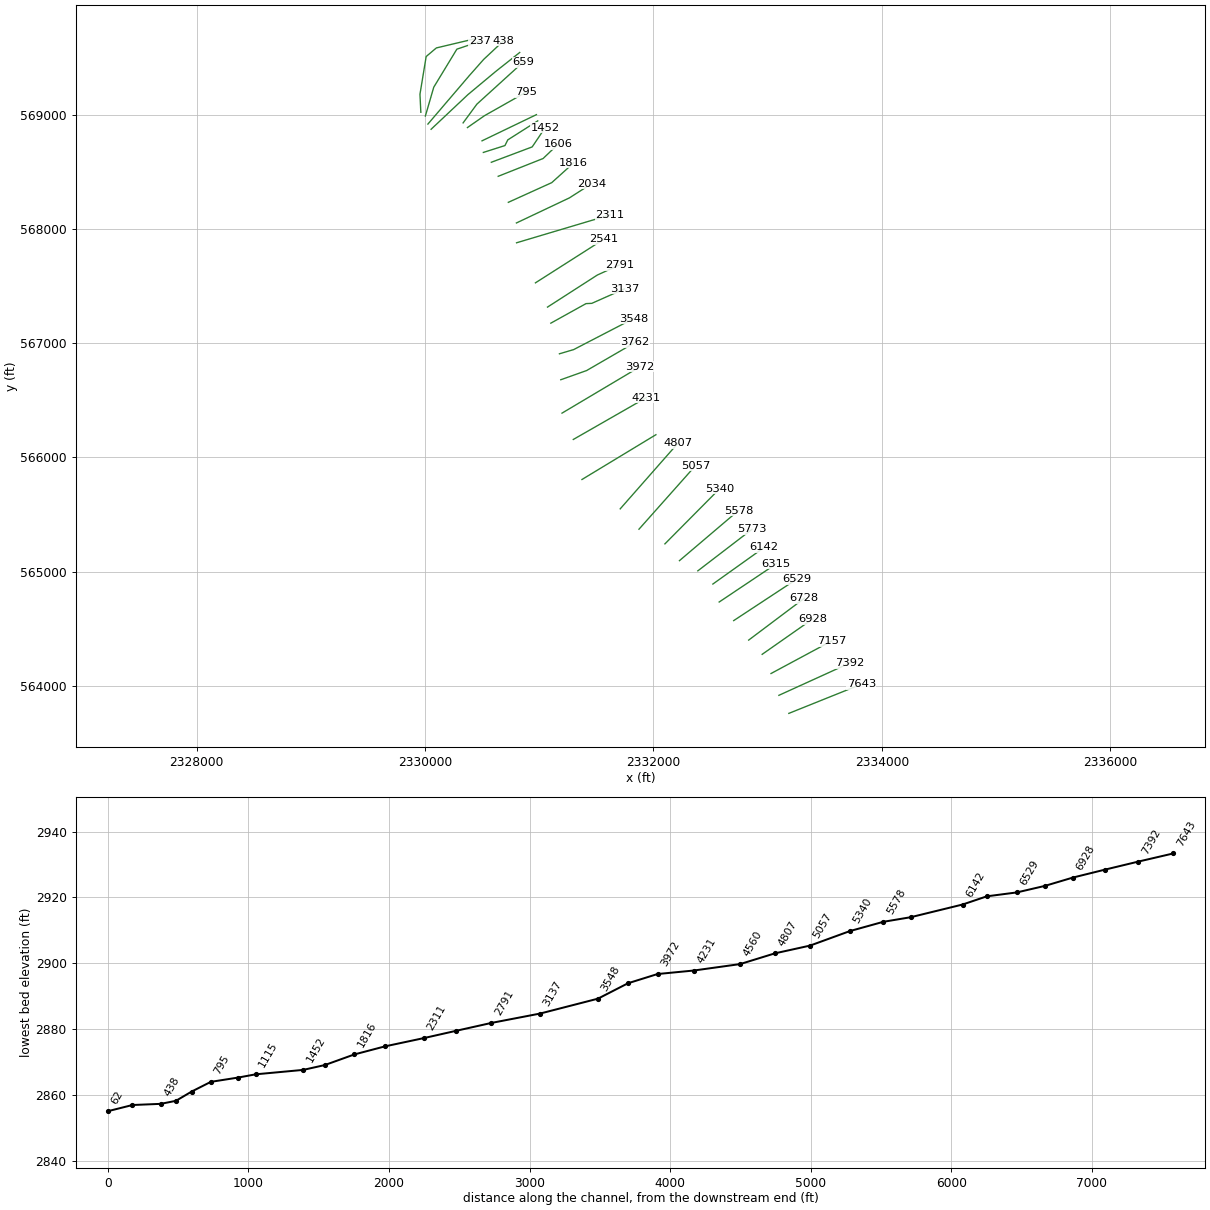
HEC-RAS study LTTLRV2.prj: LTTLRV2

--- LTTLRV2.g01 (geometry) --- (continued)

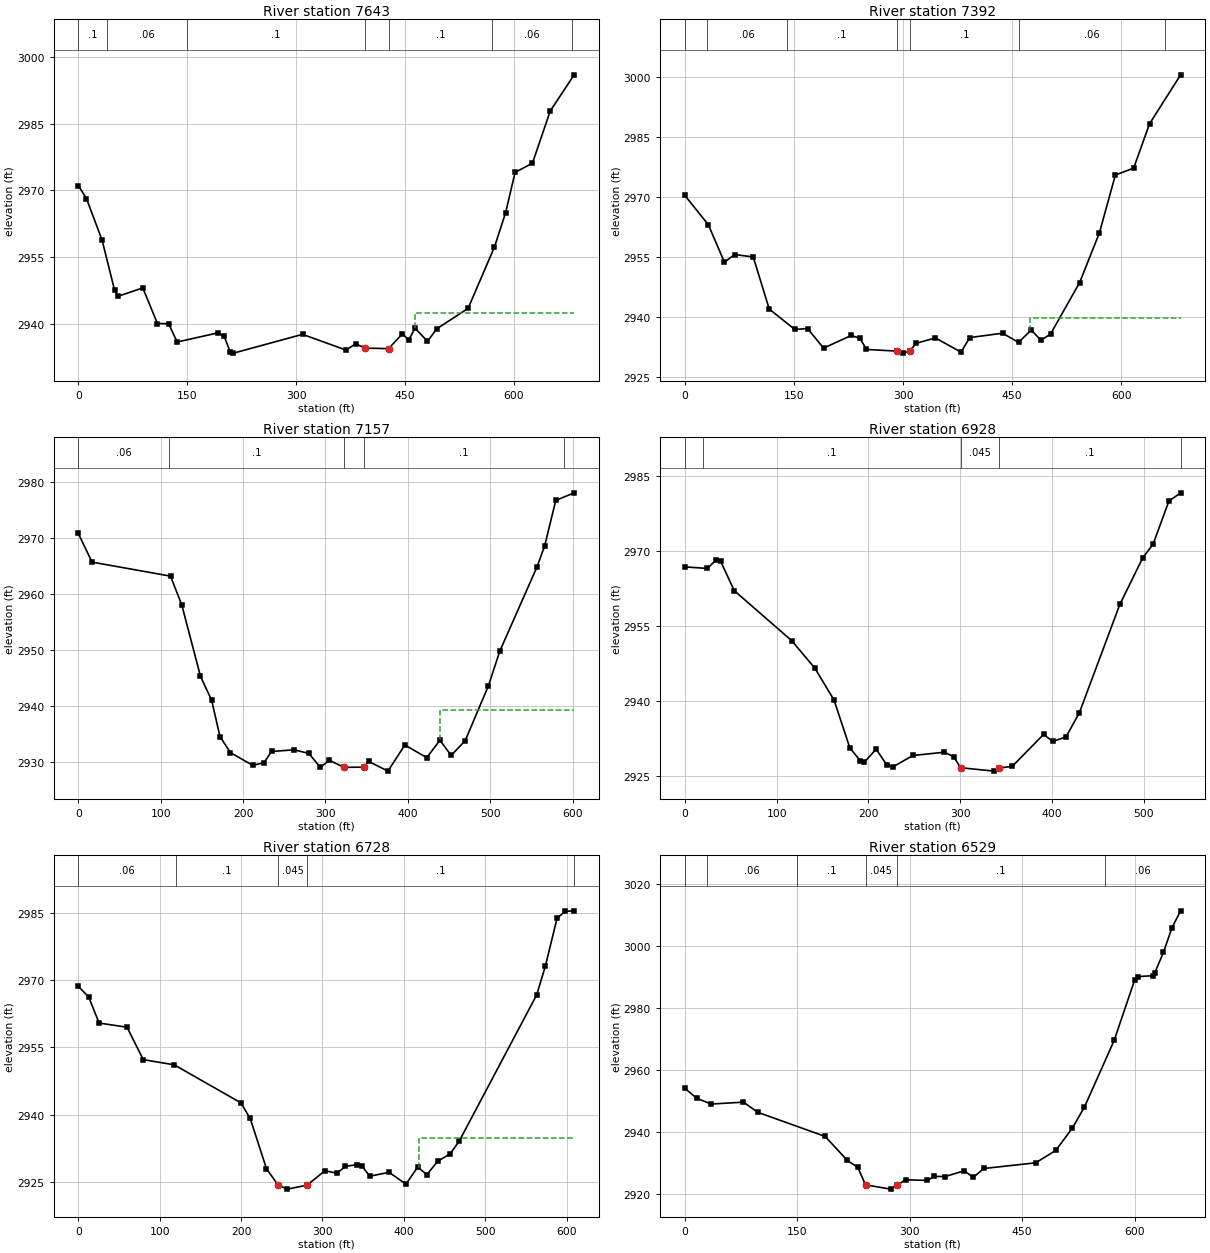
Type RM Length L Ch R = 1 ,7643    ,241.1,250.3,253.4
XS GIS Cut Line= 2
  2333185.745662563757.8330185852333819.70544892564012.466970267
#Sta/Elev= 30
       0 2971.09    11.2 2968.18    32.8 2958.77      50 2947.51    54.3 2946.14
    88.8 2948.06     109 2940.04   124.4 2939.99   136.2 2935.87   192.3 2937.93
   200.9 2937.18   209.5 2933.55   213.8 2933.37   308.9  2937.6     369 2934.05
     382 2935.48     395  2934.5   427.5 2934.38   446.6 2937.73   455.2 2936.31
   463.9    2939   481.1 2936.03     494 2938.85   537.1 2943.46   573.4 2957.27
   588.8 2965.01   601.8 2974.07   625.7 2976.13   650.3 2987.91   683.2 2996.03
#Mann= 7 ,-1,0
       0      .1       0      40     .06       0     150      .1       0
     395    .045       0   427.5      .1       0     570     .06       0
     680      .1       0
#XS Ineff= 2 , 0
                          464.17         2942.49
Permanent Ineff=
       F       F
Bank Sta=395,427.5
XS Rating Curve= 0 ,0
Exp/Cntr(USF)=0,0
Exp/Cntr=0.3,0.1

Type RM Length L Ch R = 1 ,7392    ,231.3,235.3,236.1
XS GIS Cut Line= 2
2333098.54500612563915.9535703022333719.05506201564198.341824449
#Sta/Elev= 30
       0 2970.33    32.4 2962.98    54.5 2953.62    68.6 2955.54    94.1 2954.93
   116.1  2941.9   151.2 2936.81   168.8 2937.02   190.8 2932.13   228.7 2935.29
   240.8 2934.59   249.8  2931.8   291.2 2931.39   300.6 2930.88   309.4 2931.42
   318.2 2933.35   344.6 2934.68   379.7 2931.13   391.8 2934.77   436.9 2935.86
   458.8 2933.57   476.4 2936.66   489.6  2934.1   502.8 2935.63   542.8 2948.52
     570 2960.93     592 2975.43   617.1 2977.14     639 2988.25   681.7 3000.48
#Mann= 7 ,-1,0
       0      .1       0      30     .06       0     140      .1       0
   291.2    .045       0   309.4      .1       0     460     .06       0
     660      .1       0
#XS Ineff= 2 , 0
                          475.21         2939.75
Permanent Ineff=
       F       F
Bank Sta=291.2,309.4
XS Rating Curve= 0 ,0
Exp/Cntr=0.3,0.1

Type RM Length L Ch R = 1 ,7157    ,223.7,228.5,230.6
XS GIS Cut Line= 2
2333029.55267102 564106.970292542333559.82131267564391.792805504
#Sta/Elev= 30
       0 2970.82    16.6 2965.72   111.9 2963.22   125.6 2958.07   148.3 2945.35
   161.9 2941.07   171.9 2934.63   184.6 2931.77   211.8 2929.48   225.5 2929.98
   234.5 2931.96   261.8 2932.26   279.9 2931.62   293.6 2929.14   304.9 2930.37
   322.6 2929.14   346.2 2929.17   352.6 2930.18   375.8 2928.46   396.4 2933.12
     423 2930.86   438.9 2933.97   452.6 2931.26   469.6 2933.89   497.9 2943.69
   511.5  2949.8   556.9  2964.9     566 2968.57   579.6 2976.72   601.9 2978.07
#Mann= 5 ,-1,0
       0     .06       0     110      .1       0   322.6    .045       0
   346.2      .1       0     590     .06       0
#XS Ineff= 2 , 0
                          438.71         2939.34
Permanent Ineff=
       F       F
Bank Sta=322.6,346.2
XS Rating Curve= 0 ,0
Exp/Cntr(USF)=0,0
Exp/Cntr=0.3,0.1

Type RM Length L Ch R = 1 ,6928    ,196.6,200.2,202
XS GIS Cut Line= 2
 2332952.1124486564274.9761988052333394.44049869 564584.73708848
#Sta/Elev= 30
       0 2966.81    24.6  2966.5    34.3 2968.23      39 2967.96    53.8 2962.08
   116.5 2952.07   141.7 2946.58   162.5 2940.25   179.7 2930.72   191.2 2928.09
   195.4 2927.82   208.4 2930.43   219.8 2927.33     227 2926.94   248.6 2929.18
   282.8 2929.82   293.1 2928.89   300.3 2926.73     337 2926.05   341.9 2926.67
   356.6    2927   390.7 2933.36   400.8 2931.99   415.2 2932.87   429.8 2937.74
   473.8 2959.32   498.9 2968.68     510 2971.33   527.2 2979.93     540 2981.59
#Mann= 5 ,-1,0
       0     .06       0      20      .1       0   300.3    .045       0
   341.9      .1       0     540     .06       0
Bank Sta=300.3,341.9
XS Rating Curve= 0 ,0
Exp/Cntr(USF)=0,0
Exp/Cntr=0.3,0.1

Type RM Length L Ch R = 1 ,6728    ,201.1,199.3,197.4
XS GIS Cut Line= 2
2332833.98329576 564399.66808236 2333320.9379147564765.868456171
#Sta/Elev= 30
       0 2968.61    12.8 2966.21    25.5 2960.43    59.8 2959.51    79.8  2952.3
   117.9 2951.14   199.8 2942.69   211.2 2939.22   231.2 2928.05   245.5 2924.41
   256.9 2923.51  281.17  2924.4     303 2927.59     318 2927.06   328.3 2928.58
   342.6 2928.95   348.3 2928.71   358.1 2926.38   381.9 2927.25   402.6 2924.61
   416.9 2928.37   428.4 2926.76   441.8 2929.74   456.8 2931.32   468.3 2934.26
   563.3 2966.71     574 2973.15   588.3 2983.74   598.3 2985.27   609.3 2985.38
#Mann= 5 ,-1,0
       0     .06       0     120      .1       0   245.5    .045       0
  281.17      .1       0  609.28     .06       0
#XS Ineff= 2 , 0
                          418.28         2934.82
Permanent Ineff=
       F       F
Bank Sta=245.5,281.17
XS Rating Curve= 0 ,0
Exp/Cntr(USF)=0,0
Exp/Cntr=0.3,0.1

Type RM Length L Ch R = 1 ,6529    ,212.7,214,213.5
XS GIS Cut Line= 2
2332702.72868149 564570.299080912333255.31060756564933.874362436
#Sta/Elev= 30
       0 2954.05    16.1 2950.78    35.2 2948.95    78.2 2949.56    97.5 2946.28
   187.2 2938.52   216.8 2930.79   230.8 2928.54   241.1 2922.91   274.6 2921.53
   283.3 2922.86   294.8 2924.54   323.7 2924.33   332.7 2925.64   347.3 2925.58
   372.8 2927.45   384.8 2925.31   399.1 2928.18   468.1 2930.01   494.9 2933.99
   517.2 2941.26   533.2 2947.98   572.9  2969.5   600.3 2989.02     605 2990.03
     624  2990.3   626.9 2991.14   638.6 2997.85     650 3005.79   661.5 3011.22
#Mann= 6 ,-1,0
       0      .1       0      30     .06       0     150      .1       0
   241.1    .045       0   283.3      .1       0     560     .06       0
Bank Sta=241.1,283.3
XS Rating Curve= 0 ,0
Exp/Cntr(USF)=0,0
Exp/Cntr=0.3,0.1

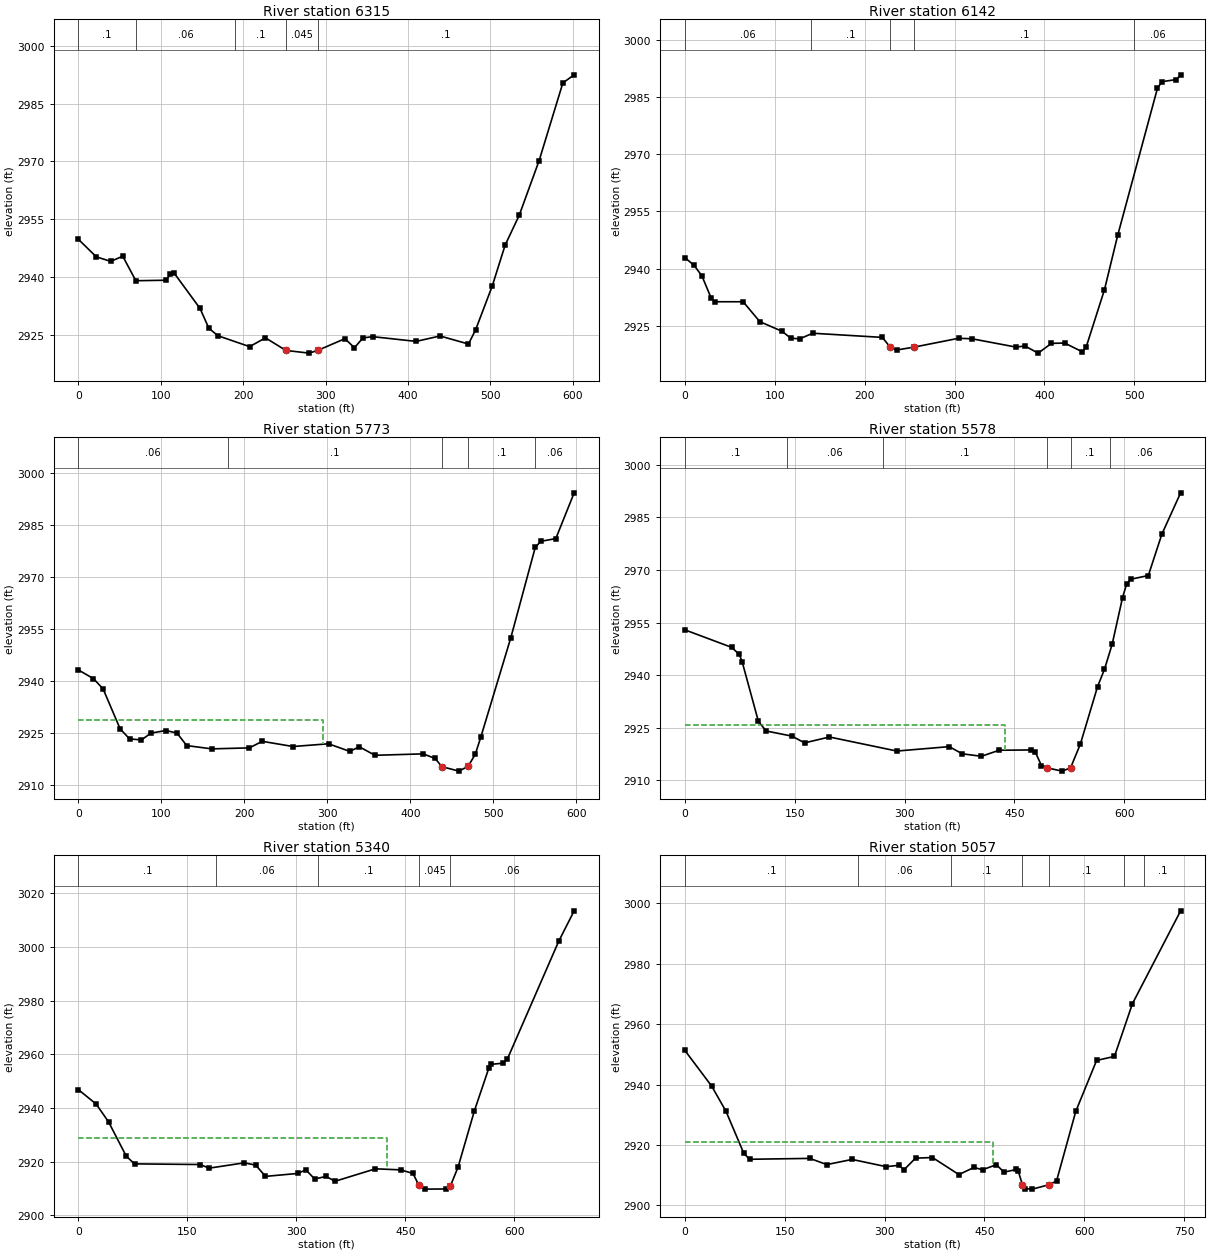
Type RM Length L Ch R = 1 ,6315    ,171.6,172.5,171.3
XS GIS Cut Line= 2
2332575.41170565564733.0548026042333075.49178601 565067.75406899
#Sta/Elev= 30
       0 2949.84    21.8 2945.29    39.4 2944.11    53.9 2945.46    69.8  2939.1
   106.8 2939.23   111.6 2940.95   116.4 2941.05   147.7 2931.92   158.4 2926.79
   169.4 2924.85   207.9 2922.02   227.1  2924.3   251.9 2921.04   280.1 2920.34
  290.51 2921.04   323.6 2924.09   335.1 2921.73   345.4 2924.27   357.1 2924.61
     410 2923.38     439 2924.78   473.5  2922.7   482.1 2926.33   502.4 2937.74
     518 2948.32   535.2  2956.1   559.3 2970.24   588.1 2990.36   601.8 2992.45
#Mann= 5 ,-1,0
       0      .1       0      70     .06       0     190      .1       0
   251.9    .045       0  290.51      .1       0
Bank Sta=251.9,290.51
XS Rating Curve= 0 ,0
Exp/Cntr(USF)=0,0
Exp/Cntr=0.3,0.1

Type RM Length L Ch R = 1 ,6142    ,357.9,369,365.5
XS GIS Cut Line= 2
2332520.28476765564890.5603397272332969.17554846565210.821598543
#Sta/Elev= 30
       0 2942.88    10.4 2940.84      19 2938.09    29.3 2932.29    33.3 2931.31
    64.9 2931.31    83.4  2926.1     108 2923.59   117.8 2921.78   127.6 2921.58
   142.3 2923.06   219.7 2921.97   228.3 2919.45   235.7 2918.67  255.35 2919.44
   304.5 2921.74   319.3 2921.61   368.4 2919.43   378.2 2919.72     393 2917.85
   407.7  2920.4   422.4  2920.5   442.1 2918.19   446.3  2919.4   466.7 2934.46
   481.4  2948.7   525.6 2987.21   530.5 2988.96   546.7 2989.52   551.4 2990.76
#Mann= 5 ,-1,0
       0     .06       0     140      .1       0   228.3    .045       0
  255.35      .1       0     500     .06       0
Bank Sta=228.3,255.35
XS Rating Curve= 0 ,0
Exp/Cntr(USF)=0,0
Exp/Cntr=0.3,0.1

Type RM Length L Ch R = 1 ,5773    ,193.9,195.2,196.5
XS GIS Cut Line= 2
2332388.54743727565006.1155703022332862.69653245565369.713786601
#Sta/Elev= 30
       0  2943.2    18.2 2940.69    29.8 2937.74    50.4 2926.18    61.8 2923.29
    76.1 2923.01    87.5 2924.96   105.4 2925.72   118.9 2924.98   130.6 2921.37
   160.8 2920.42   206.2 2920.71   221.6  2922.6   258.7  2921.1   301.5 2921.89
   327.1 2919.69   338.6 2921.03   357.4 2918.57   415.6 2918.98   429.9 2917.66
   438.1 2915.29   458.6    2914   469.8  2915.4   478.4  2918.9   484.9 2923.73
   521.2 2952.51   550.6 2978.54   557.2 2980.29   575.4 2981.09   597.5 2994.29
#Mann= 5 ,-1,0
       0     .06       0     180      .1       0   438.1    .045       0
   469.8      .1       0     550     .06       0
#XS Ineff= 2 , 0
          294.42 2928.77
Permanent Ineff=
       F       F
Bank Sta=438.1,469.8
XS Rating Curve= 0 ,0
Exp/Cntr=0.3,0.1

Type RM Length L Ch R = 1 ,5578    ,235.6,238.1,239.8
XS GIS Cut Line= 2
2332227.58697783565095.3175379872332743.41761191565533.707949645
#Sta/Elev= 30
       0 2952.92    63.8 2947.93    74.3 2945.95    78.4 2943.73   100.5 2926.79
     111 2924.06   146.5 2922.58   163.5 2920.66   197.5 2922.34   289.5 2918.33
   361.1 2919.59   378.7 2917.55     405 2916.83   429.1 2918.56   472.3 2918.64
   478.5 2918.06     487 2914.18   494.2 2913.55   515.2  2912.6   526.7 2913.53
   540.2 2920.37   563.6 2936.73     573 2941.64   583.5 2948.78   597.7 2962.12
   603.3 2966.02     609 2967.36   632.9 2968.41   651.4 2980.23     677 2992.01
#Mann= 6 ,-1,0
       0      .1       0     140     .06       0     270      .1       0
   494.2    .045       0   526.7      .1       0     580     .06       0
#XS Ineff= 2 , 0
          436.56 2925.63
Permanent Ineff=
       F       F
Bank Sta=494.2,526.7
XS Rating Curve= 0 ,0
Exp/Cntr(USF)=0,0
Exp/Cntr=0.3,0.1

Type RM Length L Ch R = 1 ,5340    ,280.9,282.8,284.7
XS GIS Cut Line= 2
2332100.27000199565242.3227059682332580.66189022565726.652232621
#Sta/Elev= 30
       0 2946.87    24.6 2941.46    41.6 2934.83      66 2922.03    77.3 2919.19
   167.4 2918.95   180.1  2917.6   228.2 2919.57   244.1 2918.73   257.5 2914.53
   301.8 2915.62   313.1 2916.96   325.2 2913.55   340.7 2914.51   353.3 2912.72
   408.8 2917.35   443.5 2916.96   460.4 2915.63   468.6  2911.2   477.1 2909.78
   505.4 2909.84  511.97 2910.99   522.4 2917.93     545 2939.02   564.8 2954.88
   567.9 2956.28   584.6 2956.72   590.3 2958.26     661 3002.18   682.2 3013.49
#Mann= 5 ,-1,0
       0      .1       0     190     .06       0     330      .1       0
   468.6    .045       0  511.97     .06       0
#XS Ineff= 2 , 0
          424.73 2928.79
Permanent Ineff=
       F       F
Bank Sta=468.6,511.97
XS Rating Curve= 0 ,0
Exp/Cntr(USF)=0,0
Exp/Cntr=0.3,0.1

Type RM Length L Ch R = 1 ,5057    ,249.3,249.8,248.6
XS GIS Cut Line= 2
2331873.19951931565370.952227952 2332368.0294151565927.471792453
#Sta/Elev= 30
       0 2951.31    40.4 2939.46    61.9 2931.12    88.6 2917.24    97.2 2915.26
   187.8 2915.55   213.3  2913.5   251.3 2915.21   302.7  2912.8     321 2913.27
   329.5 2911.84   346.5 2915.63     372 2915.84   411.7 2910.19   434.3 2912.56
   447.2 2911.79     468 2913.47   479.4 2910.99   498.1 2911.89   500.8  2911.4
  507.12 2906.81   510.8 2905.53   522.1 2905.38   546.3  2906.8   558.3 2908.05
   587.3 2931.16   618.5 2947.97   645.3  2949.3   672.3 2966.74   744.7 2997.48
#Mann= 7 ,-1,0
       0      .1       0     260     .06       0     400      .1       0
  507.12    .045       0   546.3      .1       0     660     .06       0
     690      .1       0
#XS Ineff= 2 , 0
          462.87 2920.85
Permanent Ineff=
       F       F
Bank Sta=507.12,546.3
XS Rating Curve= 0 ,0
Exp/Cntr(USF)=0,0
Exp/Cntr=0.3,0.1

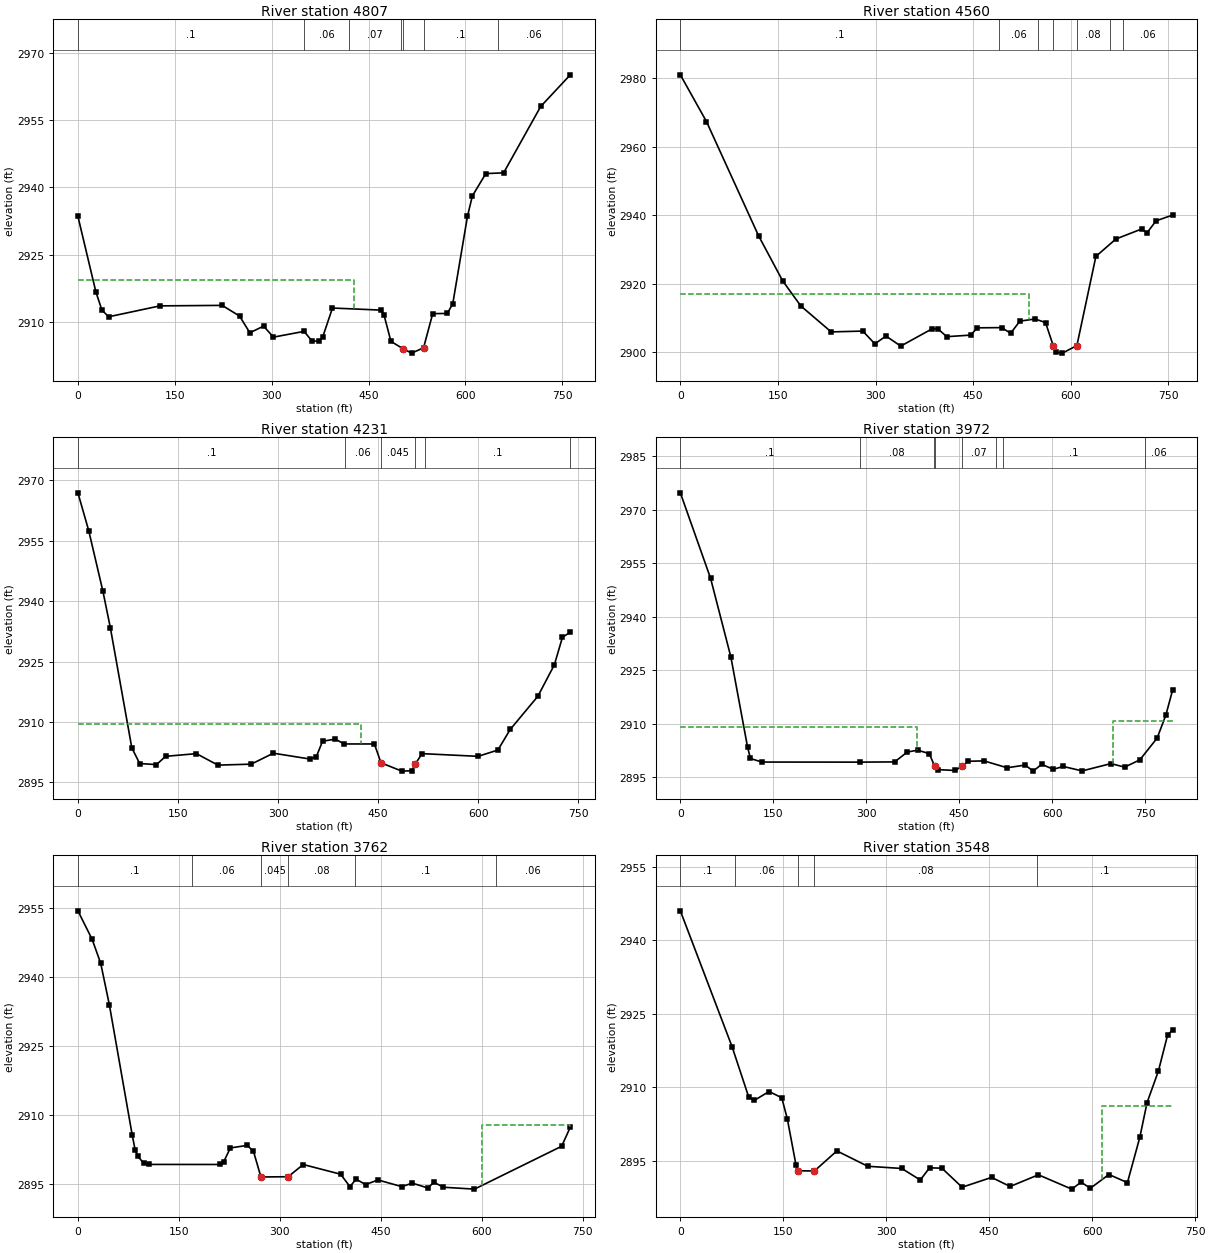
Type RM Length L Ch R = 1 ,4807    ,254.9,247.7,238
XS GIS Cut Line= 2
2331708.84801514565549.2935854412332212.35613915566121.687078596
#Sta/Elev= 30
       0 2933.51    27.8 2916.69    37.1 2912.64    47.6 2911.13     127 2913.56
   223.3 2913.67   250.2  2911.3   266.2 2907.57   287.5 2909.05   302.7 2906.59
   350.2 2907.88   362.2 2905.76   372.8 2905.66   379.2 2906.71   394.1 2913.08
   468.7 2912.62     474 2911.48   484.6 2905.65   503.9 2903.96   516.6 2903.03
   535.1 2904.21   549.3 2911.83     572 2911.87   580.4 2914.08   603.1 2933.53
   610.7 2938.06   631.5 2943.04   659.1 2943.21   716.5    2958   762.3 2965.05
#Mann= 7 ,-1,0
       0      .1       0     350     .06       0     420     .07       0
     500      .1       0   503.9    .045       0   535.1      .1       0
     650     .06       0
#XS Ineff= 2 , 0
          427.27 2919.35
Permanent Ineff=
       F       F
Bank Sta=503.9,535.1
XS Rating Curve= 0 ,0
Exp/Cntr=0.3,0.1

Type RM Length L Ch R = 1 ,4560    ,328.7,328.6,327.3
XS GIS Cut Line= 2
2331373.83180681565806.2596065582332021.17956438566198.448393994
#Sta/Elev= 30
       0 2980.94    40.2  2967.3   120.3 2933.98   157.1 2920.91   185.1 2913.55
   231.9 2905.96   280.5  2906.2     299 2902.46   316.1 2904.76   338.8 2901.82
   386.2 2906.78   395.6 2906.89   409.6 2904.57   446.5 2905.03   456.4 2907.15
   493.8 2907.21   507.8 2905.57   521.9  2909.1   545.3 2909.73   561.4 2908.67
   573.3  2901.9     578 2900.03   587.3 2899.77   609.6 2901.99   638.8 2927.99
   669.5 2933.05   708.9 2935.96   717.4 2934.86   731.3 2938.35   756.9 2940.06
#Mann= 7 ,-1,0
       0      .1       0     490     .06       0     550     .08       0
   573.3    .045       0   609.6     .08       0     660      .1       0
     680     .06       0
#XS Ineff= 2 , 0
          535.89 2917.09
Permanent Ineff=
       F       F
Bank Sta=573.3,609.6
XS Rating Curve= 0 ,0
Exp/Cntr(USF)=0,0
Exp/Cntr=0.3,0.1

Type RM Length L Ch R = 1 ,4231    ,256.6,258.8,258.3
XS GIS Cut Line= 2
2331298.02197729566156.9130151392331938.31973973566523.602116444
#Sta/Elev= 30
       0 2966.87    16.3 2957.42    37.5 2942.43    48.7 2933.32    80.8 2903.59
    92.6  2899.7   117.7 2899.44   131.5 2901.49   177.6 2902.16   209.8 2899.31
   259.7 2899.55   292.9 2902.27   348.2 2900.81   357.4 2901.44   366.6 2905.23
   385.7 2905.77   398.9 2904.56   444.3 2904.56   454.2 2899.89   485.4 2897.82
   500.3 2897.91   505.9 2899.66   515.7 2902.16   599.7 2901.49   629.4 2903.05
   647.8 2908.15   689.3  2916.4     714 2924.19   726.2 2931.06   737.9 2932.26
#Mann= 6 ,-1,0
       0      .1       0     400     .06       0   454.2    .045       0
   505.9     .06       0     520      .1       0  737.86     .06       0
#XS Ineff= 2 , 0
          424.11  2909.4
Permanent Ineff=
       F       F
Bank Sta=454.2,505.9
XS Rating Curve= 0 ,0
Exp/Cntr=0.3,0.1

Type RM Length L Ch R = 1 ,3972    ,210,210,209.4
XS GIS Cut Line= 2
 2331199.0006606566387.4550385412331881.78716403566793.819324319
#Sta/Elev= 30
       0 2974.67    48.8 2950.73    81.6 2928.66   108.4 2903.55   113.1 2900.29
   131.7 2899.29     290 2899.27   345.8 2899.33   366.3  2902.1   383.1 2902.61
   401.7 2901.65   410.6 2898.05   416.5 2897.16   443.6 2896.93  454.27  2898.1
   464.8 2899.51   490.1 2899.62   527.3 2897.69   556.6 2898.45   569.3 2896.75
   583.2 2898.66   601.8 2897.26   617.8 2898.06   648.4 2896.81   694.9 2898.86
     717 2897.87   741.5  2899.9   769.4 2905.99   783.4 2912.37   794.6 2919.57
#Mann= 8 ,-1,0
       0      .1       0     290     .08       0     410     .07       0
   410.6    .045       0  454.27     .07       0     510     .08       0
     520      .1       0     750     .06       0
#XS Ineff= 2 , 0
           382.2 2909.15  698.14          2910.9
Permanent Ineff=
       F       F
Bank Sta=410.6,454.27
XS Rating Curve= 0 ,0
Exp/Cntr(USF)=0,0
Exp/Cntr=0.3,0.1

Type RM Length L Ch R = 1 ,3762    ,214.7,213.8,212.8
XS GIS Cut Line= 3
2331188.22944105566679.831613802 2331415.1770103566760.743161523
 2331839.2779186567006.743915284
#Sta/Elev= 30
       0 2954.36    21.2 2948.14    33.9 2942.95    46.7 2933.96    80.6 2905.73
    84.9 2902.52    89.1 2901.06    97.6 2899.59   106.1 2899.31   210.8  2899.3
   216.5 2899.88   226.4 2902.89   251.3 2903.44   260.6  2902.2  271.79 2896.59
   312.2 2896.64   334.6 2899.29   390.1 2897.19   403.9 2894.51   413.2 2896.11
   427.1 2894.94   445.6 2895.94     481 2894.49   496.6 2895.26   519.5  2894.2
   528.8 2895.44   542.7 2894.36   588.9 2893.95   718.4 2903.26   731.2  2907.4
#Mann= 6 ,-1,0
       0      .1       0     170     .06       0  271.79    .045       0
   312.2     .08       0  410.94      .1       0  620.94     .06       0
#XS Ineff= 2 , 0
                          599.34         2907.93
Permanent Ineff=
       F       F
Bank Sta=271.79,312.2
XS Rating Curve= 0 ,0
Exp/Cntr=0.3,0.1

Type RM Length L Ch R = 1 ,3548    ,422.4,411.6,404.2
XS GIS Cut Line= 3
2331176.55612156566907.2233110472331300.59173205566943.843348428
2331822.72258761567214.359108437
#Sta/Elev= 30
       0    2946    75.3 2918.33    99.7 2908.01   107.5 2907.34   129.3 2909.17
   147.8 2907.89   155.9 2903.56   168.6 2894.13     172 2893.01   195.3 2892.97
   228.1 2897.06     273 2893.93   322.6 2893.48   349.6 2891.13   363.1 2893.61
   381.1 2893.54   410.5 2889.66   453.5 2891.66   480.5 2889.81   521.7 2892.19
   570.3 2889.27   583.9 2890.69   597.4 2889.45   624.4 2892.25   651.4  2890.6
   669.5 2899.85     680  2906.9   696.5 2913.33     710 2920.73   717.4  2921.7
#Mann= 5 ,-1,0
       0      .1       0      80     .06       0     172    .045       0
   195.3     .08       0  519.33      .1       0
#XS Ineff= 2 , 0
                          613.95         2906.12
Permanent Ineff=
       F       F
Bank Sta=172,195.3
XS Rating Curve= 0 ,0
Exp/Cntr(USF)=0,0
Exp/Cntr=0.3,0.1

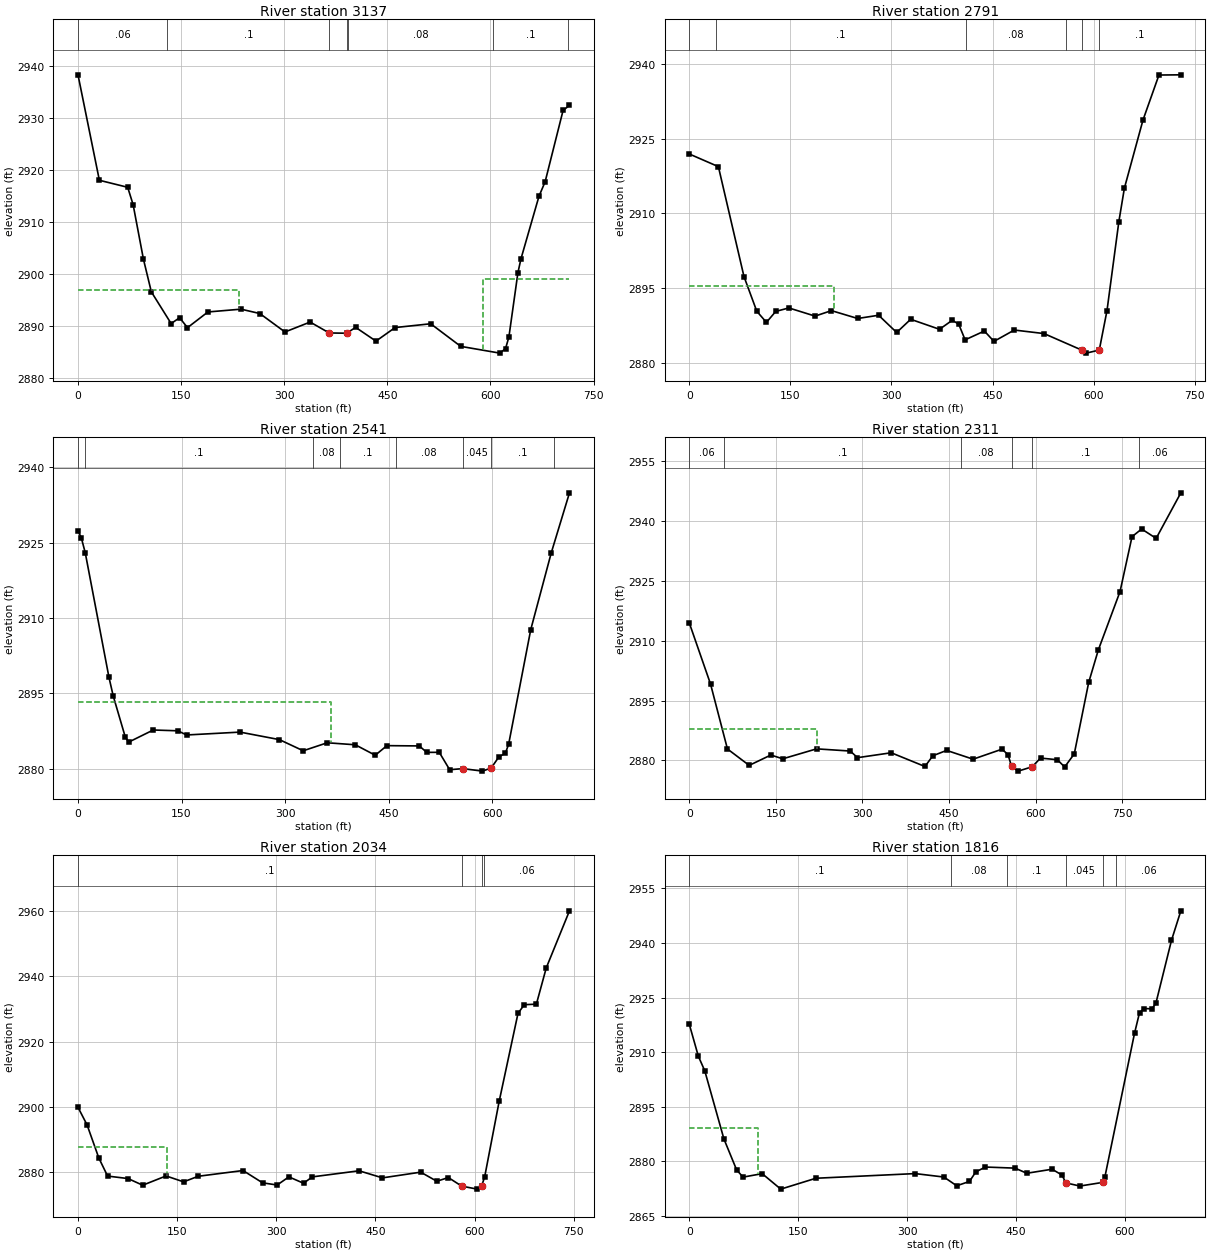
Type RM Length L Ch R = 1 ,3137    ,330.5,346,347
XS GIS Cut Line= 4
2331100.95346374567175.3764879992331409.27055266 567346.66375962
2331460.06608838567349.0263426772331744.75734673567475.424536218
#Sta/Elev= 30
       0  2938.3    31.1 2918.01    72.3 2916.66    80.2 2913.32    95.2 2902.83
   106.7 2896.54   135.5 2890.44   147.8 2891.56   159.3 2889.65     189 2892.67
   237.1 2893.21   264.5 2892.37   301.1 2888.82   337.7 2890.73   365.5 2888.63
   390.9 2888.58   403.9 2889.71   433.5 2887.06   461.3 2889.67   513.1  2890.4
   556.8 2886.05   613.7 2884.75     622 2885.62   626.9 2887.88     640 2900.23
   644.4 2902.88   670.6 2914.92   679.6 2917.73   705.7 2931.46     715 2932.42
#Mann= 7 ,-1,0
       0     .06       0     130      .1       0   365.5    .045       0
   390.9      .1       0   392.7     .08       0  603.55      .1       0
  713.55     .06       0
#XS Ineff= 2 , 0
          234.37 2896.96  589.86         2899.01
Permanent Ineff=
       F       F
Bank Sta=365.5,390.9
XS Rating Curve= 0 ,0
Exp/Cntr(USF)=0,0
Exp/Cntr=0.3,0.1

Type RM Length L Ch R = 1 ,2791    ,245,249.6,251.7
XS GIS Cut Line= 3
2331071.95528489567316.1977482862331508.49904105567597.097563646
2331699.86826865567684.513136749
#Sta/Elev= 30
       0 2921.92    43.1 2919.38    81.1 2897.29   100.1 2890.32   114.4 2888.09
   128.2 2890.29   147.7 2890.99   186.6 2889.35   210.9 2890.45   249.8 2888.87
   280.9 2889.52   307.7 2886.06   328.5 2888.71   371.3  2886.7   390.3 2888.52
   399.8 2887.73   409.3 2884.58   437.9 2886.35   452.1 2884.27   482.3 2886.55
   526.4 2885.84   583.1 2882.48   589.1 2881.91  608.43 2882.53   619.9 2890.46
   637.5 2908.34   645.7 2915.05   673.3 2928.74     697 2937.79   729.5 2937.83
#Mann= 6 ,-1,0
       0     .06       0      40      .1       0     410     .08       0
  559.11      .1       0   583.1    .045       0  608.43      .1       0
#XS Ineff= 2 , 0
          214.54 2895.45
Permanent Ineff=
       F       F
Bank Sta=583.1,608.43
XS Rating Curve= 0 ,0
Exp/Cntr=0.3,0.1

Type RM Length L Ch R = 1 ,2541    ,236.9,230.3,220.8
XS GIS Cut Line= 2
 2330966.2862295567528.5826549972331566.38232594567911.321110206
#Sta/Elev= 30
       0 2927.33     4.7 2925.98    10.5 2922.97    44.9 2898.16      51 2894.49
    68.4 2886.35    73.4  2885.3     109 2887.71   144.6 2887.55   157.3 2886.72
   234.7 2887.29   291.6  2885.8   326.2 2883.58     361 2885.17   401.6 2884.77
   430.5 2882.69   447.4  2884.6   494.3 2884.54   505.1 2883.26   523.2 2883.27
   538.3 2879.81   557.3 2880.03   585.8 2879.53   598.5 2880.16   609.5 2882.35
     619 2883.11   623.7 2884.88   655.7 2907.67   685.4 2922.94   711.8 2934.88
#Mann= 8 ,-1,0
       0     .06       0      10      .1       0     340     .08       0
     380      .1       0     460     .08       0   557.3    .045       0
   598.5      .1       0     690     .06       0
#XS Ineff= 2 , 0
          366.21 2893.33
Permanent Ineff=
       F       F
Bank Sta=557.3,598.5
XS Rating Curve= 0 ,0
Exp/Cntr(USF)=0,0
Exp/Cntr=0.3,0.1

Type RM Length L Ch R = 1 ,2311    ,270.1,277.4,282.5
XS GIS Cut Line= 2
2330800.90541552567879.4262389382331617.17786166568122.772293793
#Sta/Elev= 30
       0 2914.39    36.8 2899.08      66 2882.86   103.7 2878.75   141.2 2881.34
     162  2880.4   220.5 2882.89   278.9 2882.34   291.4 2880.68   349.9 2881.91
   408.3 2878.47     422 2881.16   445.9  2882.5   491.8  2880.3   541.9 2882.81
   552.2 2881.45   558.5 2878.48   569.9 2877.31   594.2  2878.4   608.6 2880.58
   637.9 2880.16   650.4 2878.34   667.1 2881.63   692.1 2899.53   708.8 2907.67
   746.4 2922.28   767.2 2936.04   783.9 2937.96     809 2935.61   851.8 2947.02
#Mann= 6 ,-1,0
       0     .06       0      60      .1       0     470     .08       0
   558.5    .045       0   594.2      .1       0     780     .06       0
#XS Ineff= 2 , 0
           221.2 2887.83
Permanent Ineff=
       F       F
Bank Sta=558.5,594.2
XS Rating Curve= 0 ,0
Exp/Cntr(USF)=0,0
Exp/Cntr=0.3,0.1

Type RM Length L Ch R = 1 ,2034    ,212.5,217.9,222.4
XS GIS Cut Line= 3
2330799.72412399568053.0760936162331263.97169466568272.796317903
2331457.70350533568396.831928387
#Sta/Elev= 30
       0 2899.86    13.8 2894.44    31.5 2884.34    44.8 2878.79    75.7 2878.03
    97.9 2875.99   133.3 2878.83   159.8 2877.02   181.9 2878.73   249.7 2880.49
   279.3 2876.72   301.4 2876.05   319.1 2878.55   341.3 2876.59   354.5 2878.54
   425.3 2880.41   460.7 2878.24   518.6 2879.99     543  2877.2   560.4 2878.34
   580.6 2875.71   604.1 2874.79   610.8 2875.75   615.4 2878.57   637.3 2901.68
   665.8 2928.63   675.3  2931.3   693.6 2931.46   708.6  2942.6   743.7 2960.06
#Mann= 4 ,-1,0
       0      .1       0   580.6    .045       0   610.8      .1       0
  613.62     .06       0
#XS Ineff= 2 , 0
          135.18 2887.62
Permanent Ineff=
       F       F
Bank Sta=580.6,610.8
XS Rating Curve= 0 ,0
Exp/Cntr(USF)=0,0
Exp/Cntr=0.3,0.1

Type RM Length L Ch R = 1 ,1816    ,210.2,209.9,210.6
XS GIS Cut Line= 3
2330728.84663229568233.8136974652331109.22250444568406.282260615
2331301.77302357568579.932115293
#Sta/Elev= 30
       0 2917.59    12.4 2908.85    21.2 2904.87    47.6 2886.13    65.1 2877.63
    73.9 2875.64   100.3 2876.59   125.9 2872.34   174.3 2875.33   311.1 2876.61
   350.6 2875.66   368.2 2873.26   385.8 2874.46   394.5 2877.07   407.7 2878.41
   448.6 2878.11   464.7  2876.7   499.6 2877.81   513.2 2876.21   518.6 2874.05
   537.9 2873.19   569.1 2874.18   572.4  2875.8   613.1 2915.16     620 2920.84
   626.3 2921.96   637.1  2921.9   642.5 2923.39     664  2940.7   676.9 2948.82
#Mann= 6 ,-1,0
       0      .1       0     360     .08       0  437.65      .1       0
   518.6    .045       0   569.1      .1       0  587.65     .06       0
#XS Ineff= 2 , 0
           94.62  2889.1
Permanent Ineff=
       F       F
Bank Sta=518.6,569.1
XS Rating Curve= 0 ,0
Exp/Cntr(USF)=0,0
Exp/Cntr=0.3,0.1

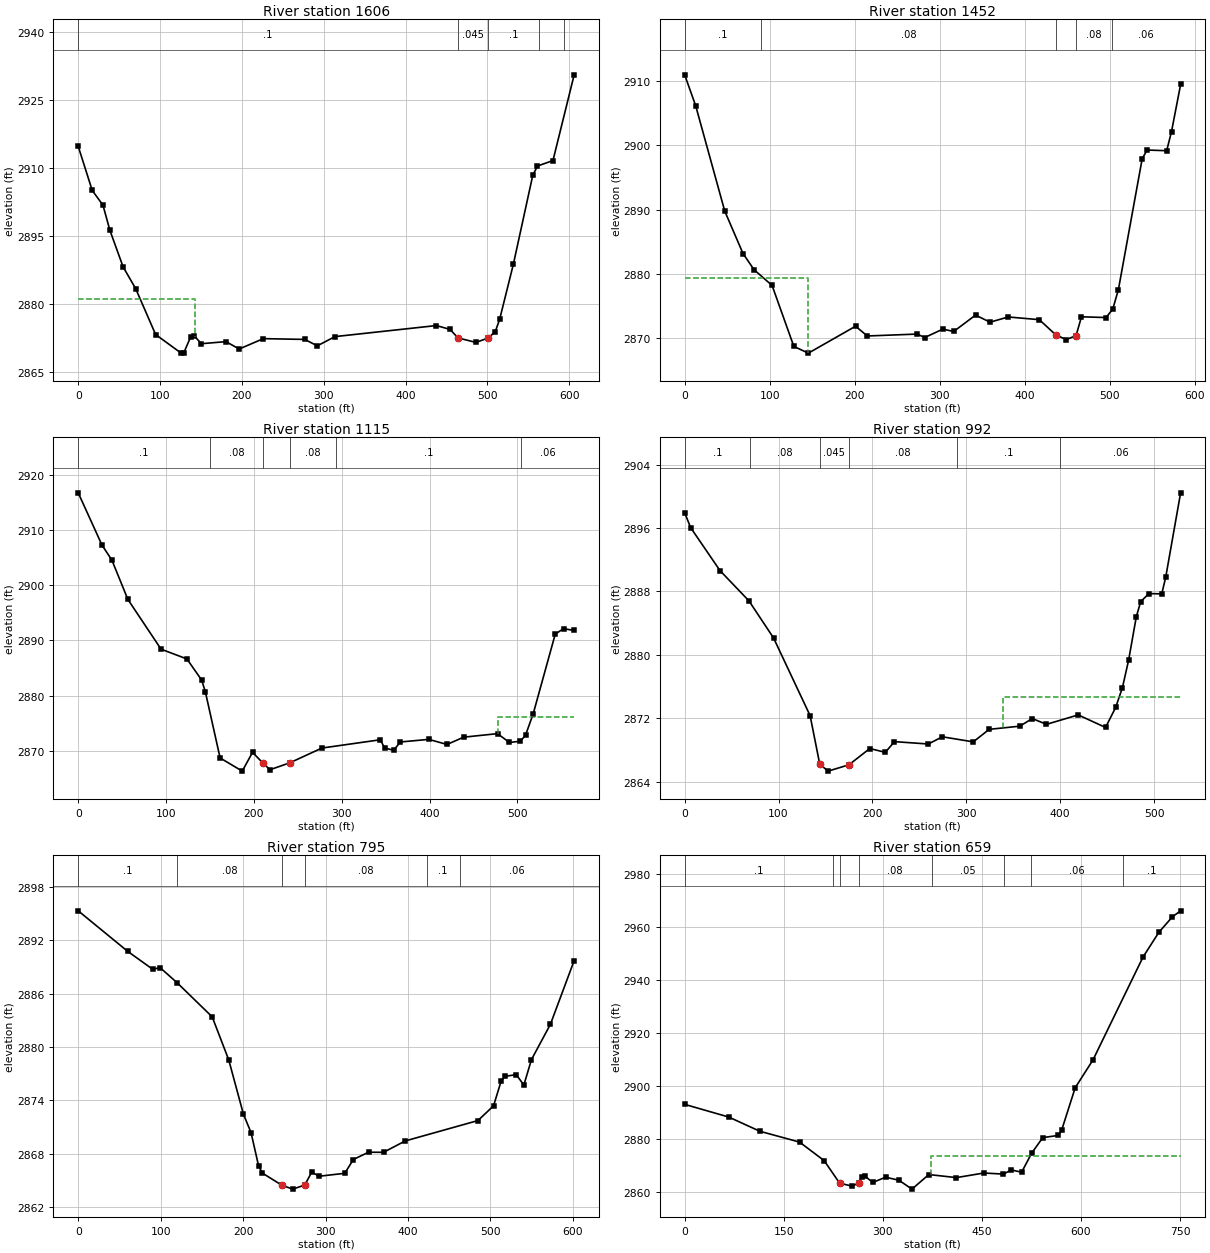
Type RM Length L Ch R = 1 ,1606    ,149.5,153.8,158.6
XS GIS Cut Line= 3
2330640.24976766 568461.802962452331033.61984662568617.733444202
2331165.92449781568744.131637743
#Sta/Elev= 30
       0 2914.79    17.1 2905.07    30.3 2901.78    38.6 2896.31    54.9 2888.15
    70.3 2883.34    94.6 2873.23   125.8 2869.12     129 2869.17   137.6 2872.78
   141.9 2872.95   150.4  2871.2   180.6 2871.66   196.7 2870.03   226.3 2872.32
   276.8 2872.15   292.2 2870.73   313.8 2872.77   437.7 2875.21   454.3 2874.37
   464.2 2872.48     486 2871.49     501 2872.45   509.7 2873.86   515.1 2876.62
   531.8 2888.75   555.5 2908.38   561.3 2910.45   580.2 2911.65   606.1 2930.59
#Mann= 5 ,-1,0
       0      .1       0   464.2    .045       0     501      .1       0
  563.15     .06       0  593.15      .1       0
#XS Ineff= 2 , 0
          143.01 2881.07
Permanent Ineff=
       F       F
Bank Sta=464.2,501
XS Rating Curve= 0 ,0
Exp/Cntr(USF)=0,0
Exp/Cntr=0.3,0.1

Type RM Length L Ch R = 1 ,1452    ,337.4,337.4,337.4
XS GIS Cut Line= 3
2330580.00389971568584.6572814062330937.93523282568719.324515646
2331050.15792802568885.886621154
#Sta/Elev= 30
       0 2910.99      13 2906.15    47.1 2889.78    68.6 2883.16    81.6 2880.64
   102.8 2878.19   128.4 2868.69   145.5 2867.65     201 2871.84   214.8 2870.32
   273.7 2870.62   282.2 2870.07   303.6 2871.39   316.4 2871.02   342.1 2873.57
   359.2 2872.47   380.5 2873.28   417.1 2872.86   436.5 2870.49   448.8 2869.76
   460.3 2870.37   466.7 2873.31   495.6 2873.19   503.5 2874.51   510.1 2877.53
   538.1 2897.92   543.9 2899.28   566.9 2899.17   572.6 2902.16   583.3 2909.49
#Mann= 5 ,-1,0
       0      .1       0      90     .08       0   436.5    .045       0
   460.3     .08       0  502.43     .06       0
#XS Ineff= 2 , 0
           144.7 2879.34
Permanent Ineff=
       F       F
Bank Sta=436.5,460.3
XS Rating Curve= 0 ,0
Exp/Cntr(USF)=0,0
Exp/Cntr=0.3,0.1

Type RM Length L Ch R = 1 ,1115    ,122.9,122.9,122.9
XS GIS Cut Line= 4
2330510.30769953568670.8915629812330699.31434408568731.137430931
2330724.12146618568780.7516751242330986.36818549568947.313780632
#Sta/Elev= 30
       0 2916.72    27.1 2907.24    38.3 2904.54    56.5 2897.42    94.3  2888.4
   123.7 2886.63   140.5 2882.81   144.7 2880.69   161.5  2868.7   186.7 2866.31
   198.4 2869.71     210 2867.82   218.2 2866.56   240.9 2867.82   277.4 2870.49
   343.9 2871.99   348.7 2870.51   359.1 2870.08   366.6 2871.59   399.1 2872.06
   419.8 2871.14   438.7 2872.46   477.3  2873.1   490.8  2871.5   503.4 2871.73
   509.2 2872.84   517.9  2876.7     543 2891.14   552.4 2892.11   564.5  2891.8
#Mann= 6 ,-1,0
       0      .1       0     150     .08       0     210    .045       0
   240.9     .08       0  293.85      .1       0  503.85     .06       0
#XS Ineff= 2 , 0
                           477.3         2876.06
Permanent Ineff=
       F       F
Bank Sta=210,240.9
XS Rating Curve= 0 ,0
Exp/Cntr(USF)=0,0
Exp/Cntr=0.3,0.1

Type RM Length L Ch R = 1 ,992     ,196.9,196.8,199.3
XS GIS Cut Line= 2
2330498.49478425568772.482634425 2330974.5552702569001.653190939
#Sta/Elev= 30
       0 2897.93     6.3 2896.06    37.7 2890.62    68.5 2886.81    94.7 2882.13
   133.6 2872.34   143.9 2866.21   152.8 2865.34     175 2866.14   197.2 2868.19
   213.7 2867.71   223.5 2869.06   259.5 2868.76   274.5 2869.67   307.4 2869.03
   324.4 2870.61     357 2871.01   370.3 2871.97   385.4 2871.24   419.2 2872.43
   448.3 2870.85   459.1 2873.37   466.3 2875.87   472.9 2879.33   481.1 2884.81
   485.8 2886.73   494.6 2887.73   508.2  2887.7   512.4 2889.78   528.3 2900.44
#Mann= 6 ,-1,0
       0      .1       0      70     .08       0   143.9    .045       0
     175     .08       0     290      .1       0     400     .06       0
#XS Ineff= 2 , 0
                          339.17         2874.65
Permanent Ineff=
       F       F
Bank Sta=143.9,175
XS Rating Curve= 0 ,0
Exp/Cntr(USF)=0,0
Exp/Cntr=0.3,0.1

Type RM Length L Ch R = 1 ,795     ,133.5,136.1,143.9
XS GIS Cut Line= 3
 2330370.7075784568888.7104678552330520.61347335568992.900380661
2330885.27816818569199.153881524
#Sta/Elev= 30
       0 2895.31    60.2 2890.74    90.5 2888.73    99.2 2888.93     120 2887.22
   162.5 2883.39   182.6 2878.54   200.4 2872.44   209.6 2870.38   218.8 2866.62
   223.4 2865.82     247 2864.46   260.2 2864.02  274.81 2864.48   283.2 2865.93
   292.3 2865.47   323.3  2865.8   333.7 2867.35   352.1 2868.17   370.3 2868.16
   396.7 2869.44   484.8 2871.73   503.7 2873.38   512.9 2876.15   517.5  2876.7
   531.3 2876.89   540.5 2875.72   549.7 2878.58   572.7 2882.55   601.5 2889.71
#Mann= 6 ,-1,0
       0      .1       0     120     .08       0     247    .045       0
  274.81     .08       0  422.56      .1       0  462.56     .06       0
Bank Sta=247,274.81
XS Rating Curve= 0 ,0
Exp/Cntr(USF)=0,0
Exp/Cntr=0.3,0.1

Type RM Length L Ch R = 1 ,659     ,113.6,112.2,124.2
BEGIN DESCRIPTION:
structure xs 4
END DESCRIPTION:
XS GIS Cut Line= 3
2330332.67532583568929.4969987282330453.63424369569093.900806342
2330858.32491943569461.487447023
#Sta/Elev= 30
       0  2893.1    66.7 2888.31   113.9 2882.93   173.9 2878.85   211.1 2871.86
   234.6 2863.33   253.5 2862.21  263.28 2863.38   267.7 2865.51   272.4 2866.12
   284.7 2863.59   304.2 2865.59   324.3 2864.44   344.1 2861.08   369.6 2866.59
   411.3 2865.43   452.9 2867.17   482.6 2866.76   494.5 2868.32   510.1 2867.47
   525.4  2874.7   542.1 2880.54   565.9 2881.38   570.7 2883.35   591.2 2899.38
   618.2 2909.93   693.9 2948.76   717.9 2958.11   738.5 2963.98   750.8 2966.21
#Mann= 8 ,-1,0
       0      .1       0  224.11     .08       0   234.6    .045       0
  263.28     .08       0  374.11     .05       0  484.11      .1       0
  524.11     .06       0  664.11      .1       0
#XS Ineff= 2 , 0
                          373.18         2873.42
Permanent Ineff=
       F       F
Bank Sta=234.6,263.28
XS Rating Curve= 0 ,0
Exp/Cntr(USF)=0,0
Exp/Cntr=0.5,0.3

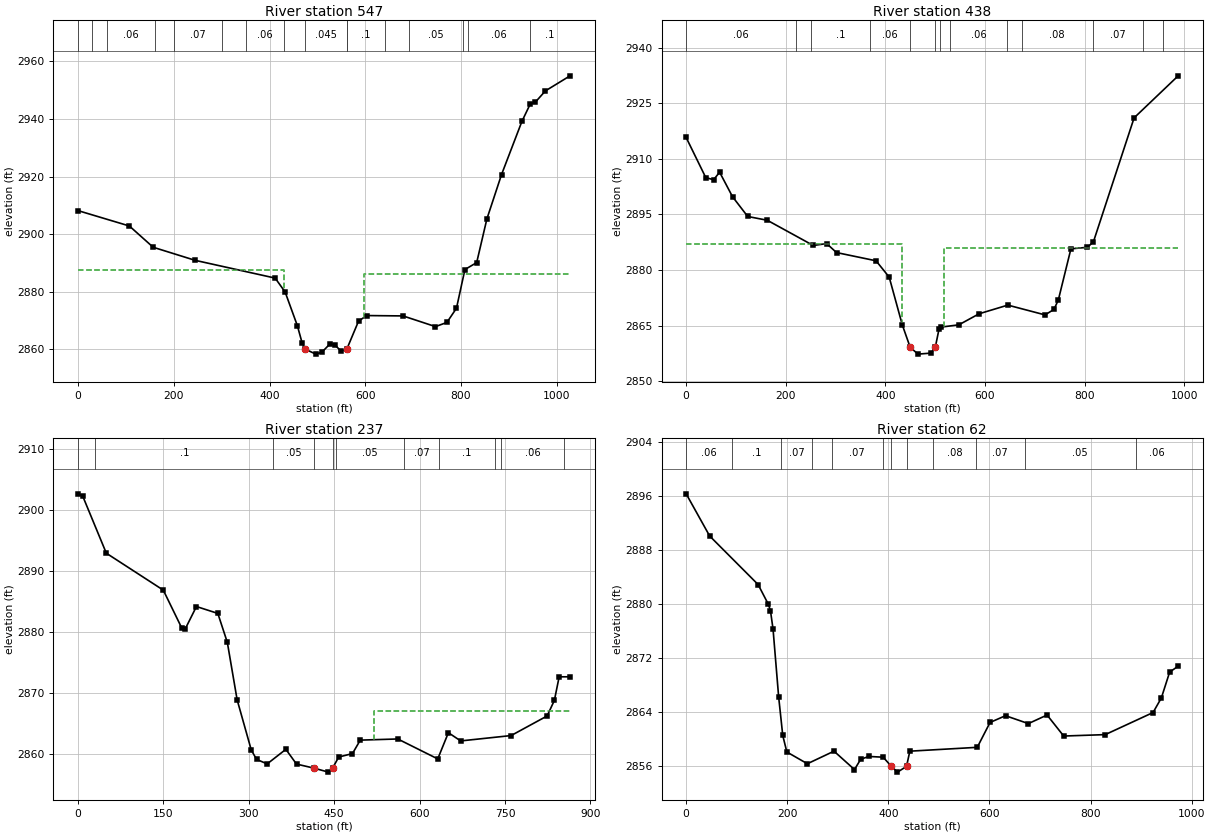
Type RM Length L Ch R = 1 ,547     ,102.8,108.3,128.3
BEGIN DESCRIPTION:
structure xs 3
END DESCRIPTION:
XS GIS Cut Line= 4
 2330052.3345823568873.5434572842330374.14179264569176.420831718
2330621.34317913569382.4219871242330828.45785429 569546.10939169
#Sta/Elev= 30
       0 2908.15   107.2 2902.81     157 2895.41   244.6 2890.87   411.8 2884.69
   432.6 2879.85   458.1 2868.17   468.1 2862.15   474.3 2860.02   496.6 2858.26
   509.2 2858.91   526.3 2861.81   536.8 2861.49   549.3 2859.24   561.8 2860.14
   585.9 2869.71   602.9 2871.67   678.9 2871.54   746.6 2867.83   770.5 2869.28
   790.5 2874.22   808.1 2887.67   832.7 2890.08     854 2905.25   884.6 2920.68
   927.2 2939.18   944.2 2945.09   955.2 2945.86   976.3 2949.78  1027.7 2955.01
#Mann= 16 ,-1,0
       0     .06       0      30      .1       0      60     .06       0
     160      .1       0     200     .07       0     300      .1       0
     350     .06       0     430      .1       0   474.3    .045       0
   561.8     .07       0  561.92      .1       0  641.92     .07       0
  691.92     .05       0  803.71     .07       0  813.71     .06       0
  943.71      .1       0
#XS Ineff= 2 , 0
             430 2887.43     597         2886.26
Permanent Ineff=
       F       F
Bank Sta=474.3,561.8
XS Rating Curve= 0 ,0
Exp/Cntr(USF)=0,0
Exp/Cntr=0.5,0.3

Type RM Length L Ch R = 1 ,438     ,194.8,201,206.4
BEGIN DESCRIPTION:
structure xs 2
END DESCRIPTION:
XS GIS Cut Line= 4
2330024.49658833568919.1977674012330384.16347047569340.108236284
2330512.21824275569484.8658049472330688.15436467569649.666729272
#Sta/Elev= 30
       0 2915.76    39.4 2904.94    55.1 2904.37    67.2  2906.4    93.1 2899.79
   123.6 2894.46   162.9 2893.44   255.2 2886.64   282.1 2887.15   301.9 2884.73
   381.3 2882.51   407.7 2878.11     434 2865.23   449.8 2859.19   465.6 2857.34
   491.9 2857.62   500.5 2859.35   507.7 2864.05   511.9 2864.63   547.5 2865.24
   588.4 2868.23   645.9 2870.56   720.6 2867.92   738.6  2869.4   747.4 2871.98
   772.6 2885.73   805.9 2886.15   817.9 2887.67   899.5 2921.06     988 2932.39
#Mann= 13 ,-1,0
       0     .06       0     220     .07       0     250      .1       0
     370     .06       0   449.8    .045       0   500.5     .06       0
     510      .1       0     530     .06       0  643.65      .1       0
  673.65     .08       0  816.92     .07       0  916.92      .1       0
  956.92     .07       0
#XS Ineff= 2 , 0
             433    2887     517            2886
Permanent Ineff=
       F       F
Bank Sta=449.8,500.5
XS Rating Curve= 0 ,0
Exp/Cntr(USF)=0,0
Exp/Cntr=0.5,0.3

Type RM Length L Ch R = 1 ,237     ,165.1,175.5,185
XS GIS Cut Line= 4
2330002.22619315568989.3495122152330075.71849724569242.118497496
2330278.21245172569575.513362479 2330478.2751322 569642.47582102
#Sta/Elev= 30
       0 2902.65     8.2 2902.29    49.7 2892.91   149.8 2886.85   182.2 2880.64
   188.6 2880.53     208 2884.16   245.6 2883.03   262.3 2878.27   279.5 2868.86
   304.3 2860.63   313.6 2859.08   332.3 2858.34   365.1 2860.73   383.8 2858.31
414.09742857.654     440 2856.99447.29682857.668     458 2859.47   482.1 2860.03
   495.8 2862.24   561.7 2862.43   631.9 2859.16   650.6 2863.46   672.2 2862.11
   760.8 2862.99   824.1 2866.21   836.8 2868.77   845.2 2872.63   864.3 2872.63
#Mann= 11 ,-1,0
       0     .06       0      30      .1       0  343.24     .05       0
414.0974    .045       0447.2968      .1       0  453.24     .05       0
  573.24     .07       0  633.24      .1       0  733.31     .05       0
  743.31     .06       0  853.31     .05       0
#XS Ineff= 2 , 0
                          519.44         2866.96
Permanent Ineff=
       F       F
Bank Sta=414.0974,447.2968
XS Rating Curve= 0 ,0
Exp/Cntr(USF)=0,0
Exp/Cntr=0.3,0.1

Type RM Length L Ch R = 1 ,62      ,,,
XS GIS Cut Line= 5
2329962.45322618569022.6689271782329955.01108955569181.080121139
 2330009.2323707569510.6604575692330098.53801025569586.144986235
2330452.57108132569670.134813906
#Sta/Elev= 30
       0 2896.28    46.5 2890.04   142.3 2882.86   162.7 2879.92   166.8 2878.97
   171.9 2876.26     183 2866.22   191.1 2860.52   199.2 2858.08   239.8 2856.34
   292.5  2858.2     333 2855.48   345.2 2856.99   361.1 2857.42   389.8 2857.31
     406 2855.95   418.1  2855.1  435.96 2855.95   442.5  2858.2   575.9 2858.77
   601.2 2862.45   631.8 2863.45     677 2862.28     714 2863.55   746.9 2860.44
   829.1 2860.65   923.7 2863.92   940.1 2866.08   956.5  2869.9973.3894 2870.78
#Mann= 12 ,-1,0
       0     .06       0      90      .1       0  188.59     .07       0
  248.59      .1       0  288.59     .07       0  388.59     .05       0
     406    .045       0  435.96     .05       0  488.59     .08       0
   572.6     .07       0  669.53     .05       0  889.53     .06       0
Bank Sta=406,435.96
XS Rating Curve= 0 ,0
Exp/Cntr(USF)=0,0
Exp/Cntr=0.3,0.1
LCMann Table=0